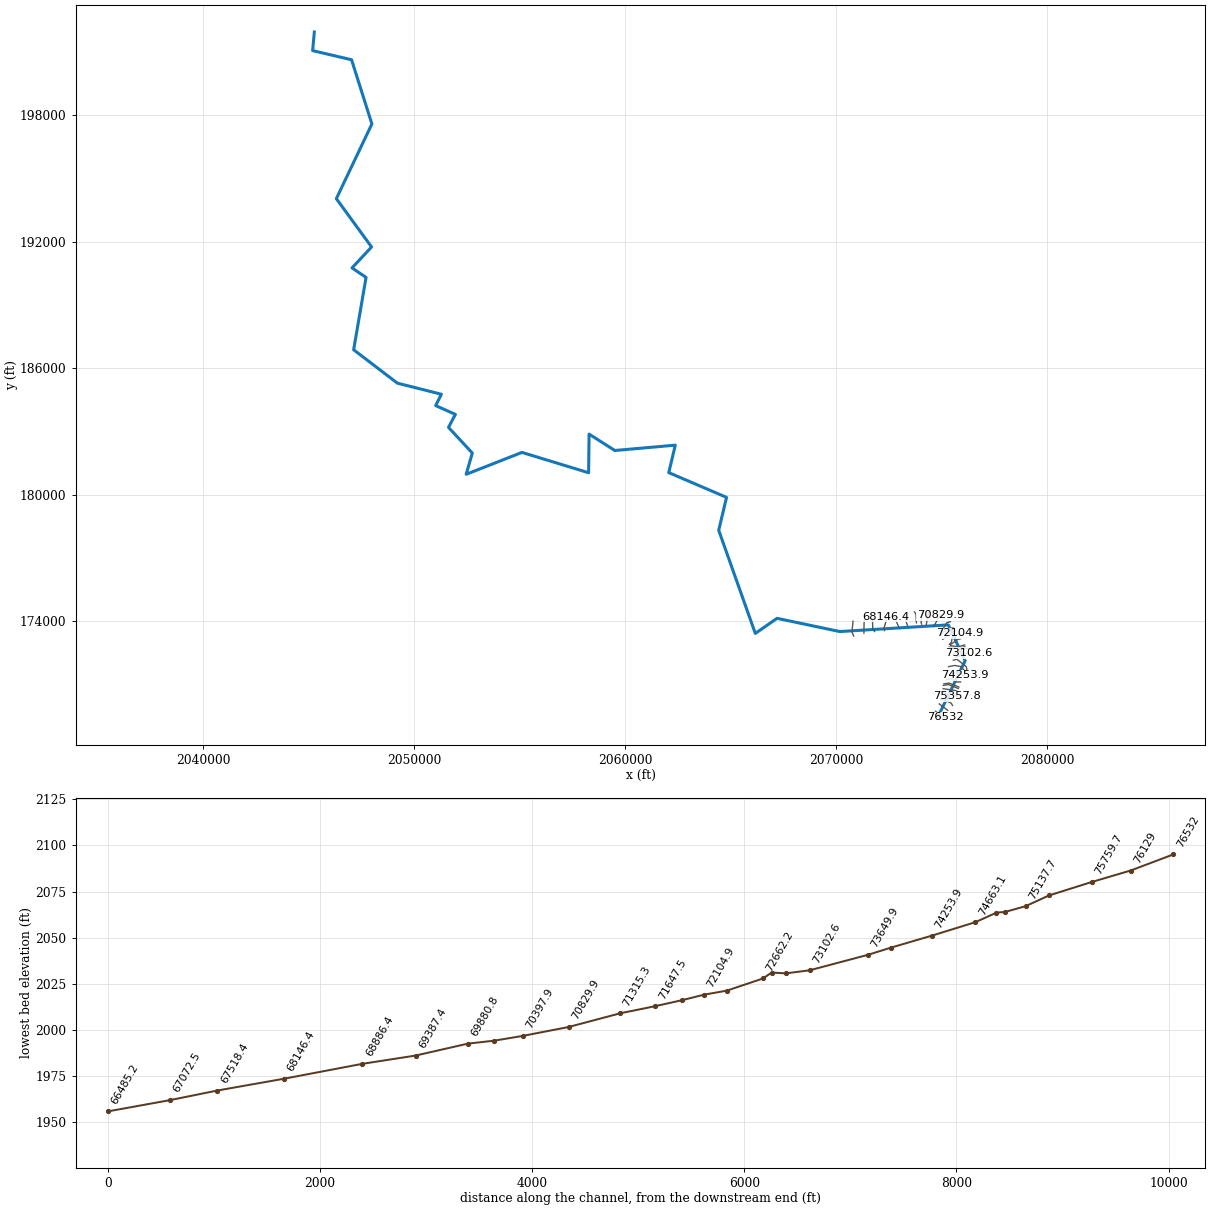
--- HNSCK.prj (project) ---

Proj Title=HNSCK
Current Plan=p01
Default Exp/Contr=0,0
English Units
Geom File=g01
Flow File=f01
Plan File=p01
BEGIN DESCRIPTION:
END DESCRIPTION:
DSS Export Rating Curves= 0
DSS Export Rating Curve Sorted= 0
DSS Export Volume Flow Curves= 0
DXF OffsetX= 0
DXF OffsetY= 0
DXF ScaleX= 0
DXF ScaleY= 0

--- HNSCK.p01 (plan) ---

Plan Title=Floodplain
Program Version=4.00
Geom File=g01
Flow File=f01
K Sum by GR=0
Std Step Tol=0.01
Critical Tol=0.01
Num of Std Step Trials=20
Max Error Tol=0.3
Flow Tol Ratio=0.001
Split Flow NTrial=30
Split Flow Tol=0.02
Split Flow Ratio=0.02
Log Output Level=0
Friction Slope Method=1
Unsteady Friction Slope Method=2
Unsteady Bridges Friction Slope Method=1
Global Log Level=0
CheckData=False
Run HTab=0
Run UNet=0
Run PostProcess=0
UNET Theta=0
UNET Theta Warmup=0
UNET ZTol=0
UNET ZSATol=0
UNET MxIter=0
UNET MaxInSteps=0
UNET DtIC=0
UNET DtMin=0
UNET MaxCRTS=0
UNET WFStab=0
UNET SFStab=0
UNET WFX=0
UNET SFX=0
UNET DSS MLevel=0
UNET DZMax Abort=0
UNET Convert EG Bridges=0
UNET Use Existing IB Tables=0
UNET Froude Limit=0
UNET Froude Power=0
Write IC File=0
Echo Input=False
Echo Output=False
Write Detailed=0

--- HNSCK.f01 (steady flow) ---

Flow Title=NFF Regression Equation
Program Version=4.00
Number of Profiles=1
Profile Names=P100yr
River Rch & RM=HNSCK,Main      ,76532
627.9011
River Rch & RM=HNSCK,Main      ,73102.6
841.0389
River Rch & RM=HNSCK,Main      ,73102.6
659.0217
River Rch & RM=HNSCK,Main      ,69387.4
910.3101
River Rch & RM=HNSCK,Main      ,64575.6
1001.499
River Rch & RM=HNSCK,Main      ,61111.9
1108.472
River Rch & RM=HNSCK,Main      ,60651.4
1419.261
River Rch & RM=HNSCK,Main      ,59383.6
1521.878
River Rch & RM=HNSCK,Main      ,52417.4
1634.098
River Rch & RM=HNSCK,Main      ,52067.4
1996.775
River Rch & RM=HNSCK,Main      ,50193.4
2017.707
River Rch & RM=HNSCK,Main      ,49118.4
2256.989
River Rch & RM=HNSCK,Main      ,45620.9
2375.871
River Rch & RM=HNSCK,Main      ,32612.2
2589.805
River Rch & RM=HNSCK,Main      ,32136.9
3370.990
River Rch & RM=HNSCK,Main      ,29205.6
3493.947
River Rch & RM=HNSCK,Main      ,20618.7
3852.640
River Rch & RM=HNSCK,Main      ,15239.5
4126.569
River Rch & RM=HNSCK,Main      ,423.9
4516.796
River Rch & RM=HNSCK,Main      ,64.8
4518.306
Boundary for River Rch & Prof#=HNSCK,Main      ,1
Up Type=0
Dn Type=3
Dn Slope=0.002216

--- HNSCK.g01 (geometry) ---

Geom Title=USGS 10m DEM
Program Version=4.10

River Reach=HNSCK           ,Main
Reach XY= 30
     2074850.954      169507.473     2076118.617      172122.377
     2075318.617      173823.071      2070175.33      173507.273
     2067201.719      174133.662     2066169.774      173419.078
     2064435.371      178309.078     2064805.946      179868.796
     2062067.278      181042.331     2062376.436      182344.197
     2059508.858      182091.159     2058288.187      182869.794
     2058266.974      181036.201      2055106.59      182000.871
     2052460.826      180962.602     2052753.169      181970.312
     2051623.153      183188.297     2051949.542      183803.054
     2051015.872      184219.945     2051285.696      184758.826
     2049201.211      185283.213     2047126.365      186867.442
     2047715.167       190299.56     2047049.368      190747.355
     2047975.757      191741.105     2046306.009       194031.73
     2047991.773      197573.397     2047027.231      200617.569
     2045182.613      201050.512     2045262.316      201931.329

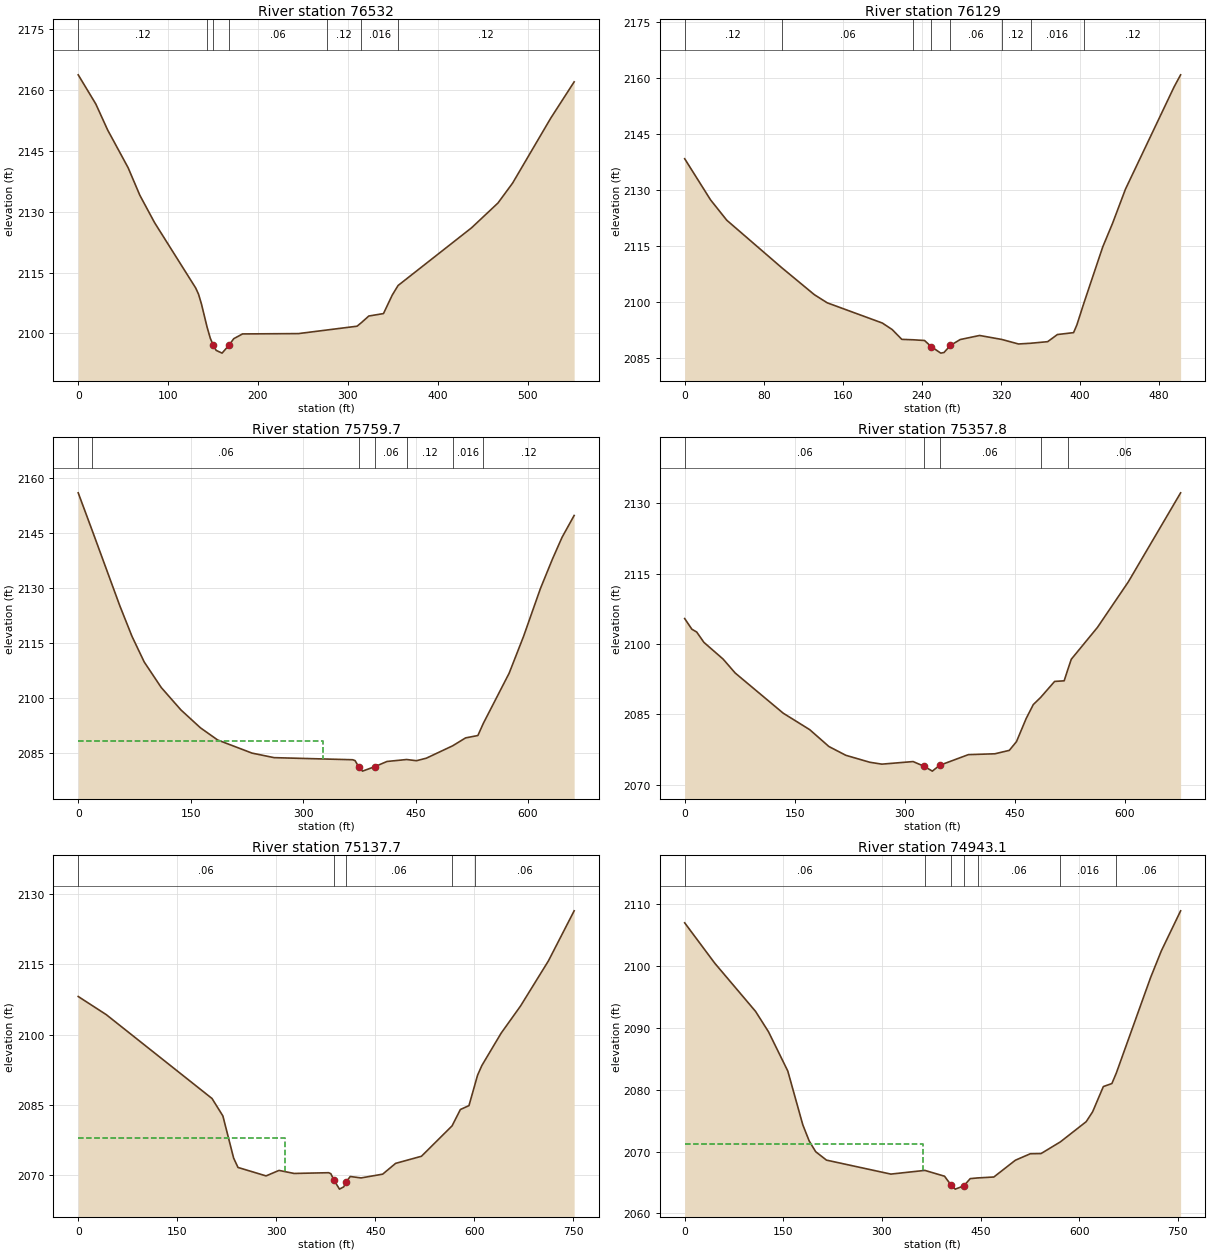
Type RM Length L Ch R = 1 ,76532   ,401.4,403,403
XS GIS Cut Line= 3
     2074715.619      169727.308       2075036.8      169464.722
     2075171.349       169438.68
#Sta/Elev= 30
       0 2163.71    19.6 2156.52    32.7 2150.15    55.5 2140.85    68.6 2134.04
    84.9 2127.33   130.7 2111.22   133.9 2109.68   137.2 2107.22  143.412101.574
     147 2098.82   150.3  2097.1   153.5 2095.84   160.1 2095.16   167.9 2097.14
   173.1 2098.72   182.9 2099.89     245 2099.97  277.012100.863   310.3 2101.79
  315.172102.678   323.4  2104.3   339.7  2104.9   349.5 2109.47  355.962111.818
   437.7 2126.02   467.1 2132.13   483.4 2137.04   525.8 2153.02   551.9 2161.98
#Mann= 7 ,-1 , 0
       0     .12       0  143.41     .06       0   150.3    .045       0
   167.9     .06       0  277.01     .12       0  315.17    .016       0
  355.96     .12       0
Bank Sta=150.3,167.9
XS Rating Curve= 0 ,0
Exp/Cntr=0.3,0.1

Type RM Length L Ch R = 1 ,76129   ,365.7,369.3,367.9
XS GIS Cut Line= 2
     2074893.571      170076.701     2075292.876      169772.881
#Sta/Elev= 30
       0 2138.48    26.2 2127.46    42.6 2122.01   97.992109.346   131.2 2102.07
   144.3 2099.88     200 2094.47   209.9 2092.74   219.7  2090.1  231.432089.981
   242.7 2089.79   249.3 2088.18   259.1 2086.41   262.4 2086.58   268.9 2088.48
   278.8 2090.05   298.4 2091.14  320.882090.073   337.8 2088.86  350.072089.055
   367.3 2089.48   377.1 2091.39   393.5  2091.9   396.8 2093.95  404.222100.044
     423 2114.86   432.9 2121.16     446 2130.34   495.2 2157.73   501.8 2160.96
#Mann= 8 ,-1 , 0
       0     .12       0   97.99     .06       0  231.43     .12       0
   249.3    .045       0   268.9     .06       0  320.88     .12       0
  350.07    .016       0  404.22     .12       0
Bank Sta=249.3,268.9
XS Rating Curve= 0 ,0
Exp/Cntr=0.3,0.1

Type RM Length L Ch R = 1 ,75759.7 ,394.4,401.9,412.2
XS GIS Cut Line= 4
     2074960.845      170285.034     2075117.095      170276.354
     2075455.637      170111.423     2075520.741      170000.746
#Sta/Elev= 30
       0 2155.94   18.982145.508    55.4 2125.23    71.7 2116.87      88 2109.89
   110.8 2102.91   136.9 2096.84     163 2091.95     186 2088.63   231.8 2085.06
   261.3 2083.82   366.1 2083.25   369.3 2083.01   374.3 2081.27   379.2 2080.15
   395.5 2081.36   411.9 2082.78  438.052083.311   451.2 2082.99   464.3 2083.67
  499.492087.052   516.7  2089.2   533.1 2089.85  540.342093.148   574.8 2106.82
   594.1 2116.89   616.5 2129.87   632.6 2137.92   645.4 2143.84   661.5 2149.77
#Mann= 7 ,-1 , 0
       0     .12       0   18.98     .06       0   374.3    .045       0
   395.5     .06       0  438.05     .12       0  499.49    .016       0
  540.34     .12       0
#XS Ineff= 2 , 0
          326.85 2088.29
Permanent Ineff=
       F       F
Bank Sta=374.3,395.5
XS Rating Curve= 0 ,0
Exp/Cntr=0.3,0.1

Type RM Length L Ch R = 1 ,75357.8 ,218.1,220.1,220.7
XS GIS Cut Line= 3
     2075095.394      170604.045     2075551.123      170508.558
     2075750.776      170441.284
#Sta/Elev= 30
       0 2105.41     9.8 2103.14    16.4 2102.54    26.2 2100.34    52.5 2096.75
    68.9 2093.79   134.4 2085.22   170.5 2081.71   196.7 2078.11   219.7 2076.24
   252.5 2074.75   268.9 2074.35   311.5  2074.9   326.9 2073.86   337.7 2072.86
   347.6 2074.09   386.9 2076.38     423 2076.56   442.7 2077.29   452.5 2079.16
   465.6 2084.06   475.4 2087.06  485.382088.577   504.5    2092   517.5 2092.13
  522.312094.456   527.2 2096.73   562.9 2103.53     605 2113.25   676.3 2132.24
#Mann= 5 ,-1 , 0
       0     .06       0   326.9    .045       0   347.6     .06       0
  485.38    .016       0  522.31     .06       0
Bank Sta=326.9,347.6
XS Rating Curve= 0 ,0
Exp/Cntr=0.3,0.1

Type RM Length L Ch R = 1 ,75137.7 ,199.8,194.6,188.9
XS GIS Cut Line= 3
     2075075.428      170798.272     2075644.873      170714.939
     2075804.595      170642.022
#Sta/Elev= 30
       0 2108.11    42.5 2104.24   202.7 2086.36   219.1 2082.65   235.4 2073.66
     242 2071.67   284.5 2069.87   304.1 2071.04     327 2070.39   379.3 2070.55
   382.6 2070.34   387.6 2068.91   395.7 2067.05   402.2 2067.54   405.5 2068.55
     412 2069.74   428.4 2069.44   461.1 2070.24   480.7 2072.54   519.9 2074.06
   566.22080.533   578.8 2084.02   591.8 2084.85  600.912089.385   604.8 2091.33
   611.3 2093.39   640.5 2100.29   669.8 2106.06   712.1 2115.69   751.1 2126.37
#Mann= 5 ,-1 , 0
       0     .06       0   387.6    .045       0   405.5     .06       0
   566.2    .016       0  600.91     .06       0
#XS Ineff= 2 , 0
          312.49    2078
Permanent Ineff=
       F       F
Bank Sta=387.6,405.5
XS Rating Curve= 0 ,0
Exp/Cntr=0.3,0.1

Type RM Length L Ch R = 1 ,74943.1 ,78.5,79.3,79.9
XS GIS Cut Line= 3
     2075082.373      170954.739     2075334.109      170993.802
     2075796.349      170804.999
#Sta/Elev= 30
       0 2106.97    45.7 2100.45   107.8 2092.65   127.4 2089.37   156.8 2083.01
   179.6 2074.32   189.4 2071.69   199.2 2069.97   215.6 2068.61   313.5 2066.35
  365.182066.948   395.1 2066.01   404.9  2064.6   411.4 2063.92   424.4 2064.44
   434.2 2065.62  445.342065.728   470.1 2065.88   502.8 2068.59   525.6 2069.64
   541.9 2069.67  571.29 2071.56   610.5 2074.82   620.3 2076.42   636.6  2080.5
   649.6 2080.99  656.312082.681   708.4 2098.11   724.7 2102.42   754.1 2108.91
#Mann= 7 ,-1 , 0
       0     .06       0  365.18     .08       0   404.9    .045       0
   424.4     .08       0  445.34     .06       0  571.29    .016       0
  656.31     .06       0
#XS Ineff= 2 , 0
          362.69 2071.25
Permanent Ineff=
       F       F
Bank Sta=404.9,424.4
XS Rating Curve= 0 ,0
Exp/Cntr=0.3,0.1

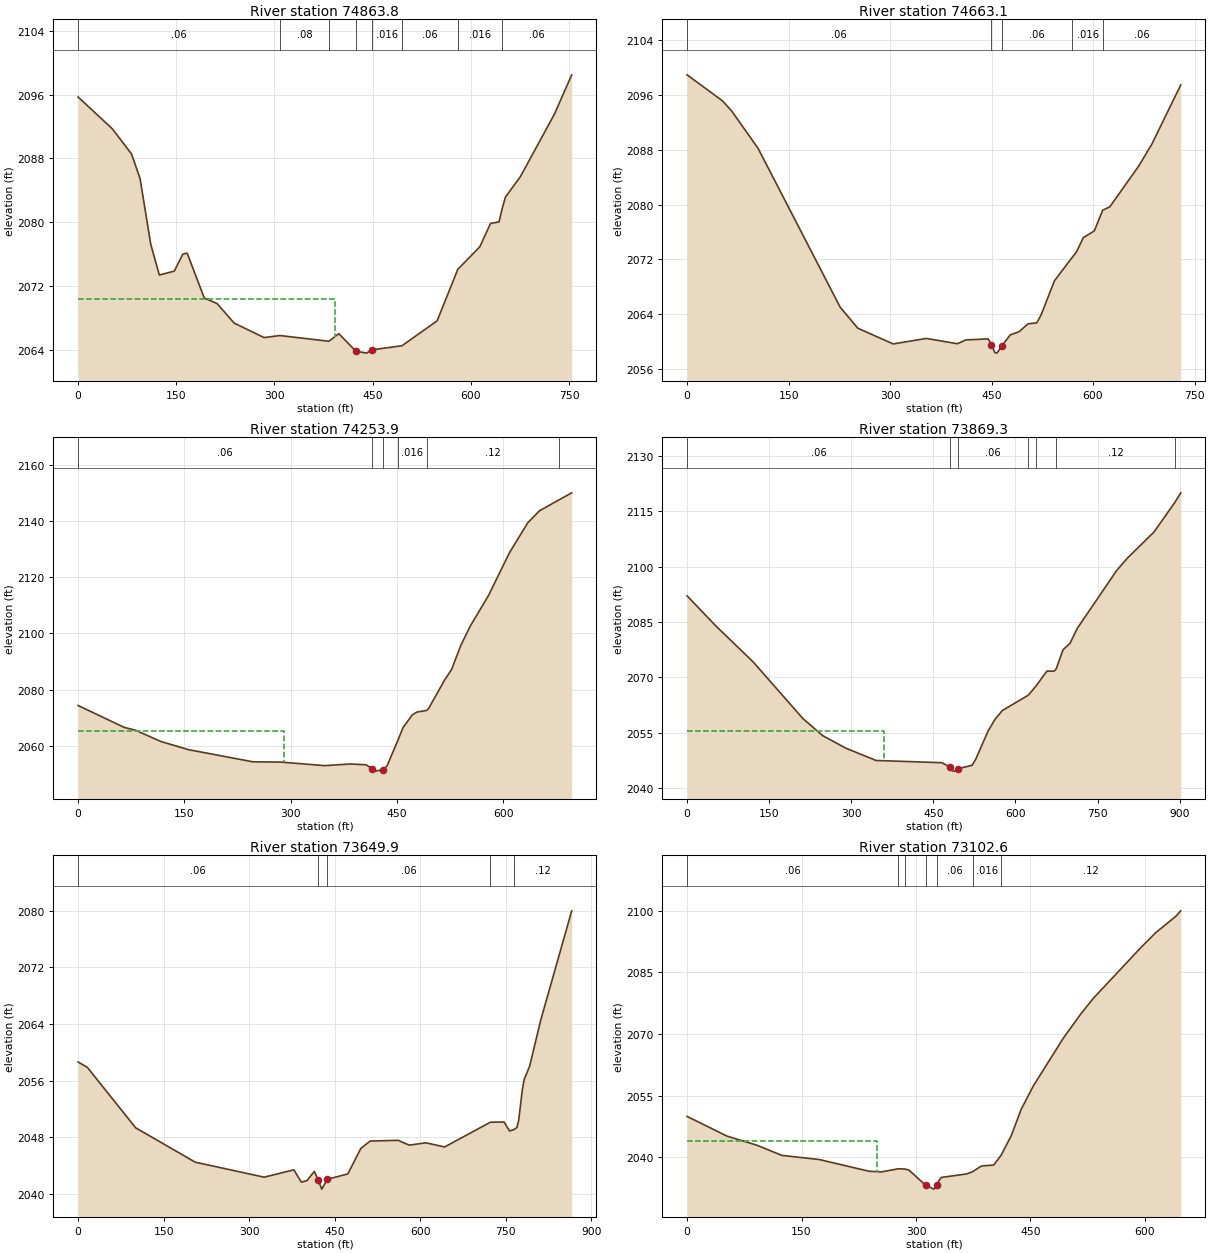
Type RM Length L Ch R = 1 ,74863.8 ,204.2,200.7,197.1
XS GIS Cut Line= 3
     2075110.151      171024.183     2075361.887      171063.246
     2075824.126      170874.444
#Sta/Elev= 30
       0 2095.69    52.3  2091.7    81.6 2088.55    94.7 2085.45     111 2077.21
   124.1 2073.36     147 2073.85     160 2075.98   166.6 2076.11   192.7 2070.48
   212.3 2069.78   238.4 2067.33   284.1 2065.51  308.182065.767  383.042065.049
   398.3    2066   424.4  2063.8   440.8 2063.56   448.6 2063.97  494.86 2064.49
   548.5 2067.61  580.082074.075   613.7  2076.9     630 2079.82   643.1 2080.02
  647.912081.706   652.9 2083.14   675.7  2085.7     728 2093.59   754.1 2098.47
#Mann= 8 ,-1 , 0
       0     .06       0  308.18     .08       0  383.04    .016       0
   424.4    .045       0   448.6    .016       0  494.86     .06       0
  580.08    .016       0  647.91     .06       0
#XS Ineff= 2 , 0
          392.09 2070.38
Permanent Ineff=
       F       F
Bank Sta=424.4,448.6
XS Rating Curve= 0 ,0
Exp/Cntr=0.3,0.1

Type RM Length L Ch R = 1 ,74663.1 ,403.8,409.2,413.1
XS GIS Cut Line= 4
     2075224.734      171218.194     2075433.067      171276.788
     2075717.356      171116.197     2075903.988      171118.368
#Sta/Elev= 30
       0 2098.89    52.5 2095.08    65.6 2093.66   104.9 2088.18   226.2 2065.05
   252.3 2061.98   304.6 2059.69   353.6 2060.49   399.3 2059.72   412.3 2060.28
     445 2060.42   449.8 2059.57   454.8 2058.44     458 2058.35   464.8 2059.34
   477.6 2061.01   490.7 2061.47   503.8 2062.61   516.8 2062.76   523.3 2063.93
   542.9 2068.88  569.512072.335   575.7 2073.12   585.5 2075.16   601.9 2076.16
  614.172079.162   624.8 2079.66   667.4 2085.59     687 2088.81   729.6 2097.42
#Mann= 5 ,-1 , 0
       0     .06       0   449.8    .045       0   464.8     .06       0
  569.51    .016       0  614.17     .06       0
Bank Sta=449.8,464.8
XS Rating Curve= 0 ,0
Exp/Cntr=0.3,0.1

Type RM Length L Ch R = 1 ,74253.9 ,379.8,384.6,387.8
XS GIS Cut Line= 3
     2075415.706      171485.772     2075660.604      171562.264
     2076078.684      171424.555
#Sta/Elev= 30
       0  2074.4      65 2066.63    81.2  2065.6   116.9  2061.6   155.9  2058.7
   246.8 2054.38   285.9 2054.29   347.9 2053.02   383.7 2053.61   406.6 2053.32
   414.7 2051.97   419.6 2051.07   429.7 2051.55   435.9 2052.84  451.412062.076
   458.7 2066.57   471.8  2071.1   478.3 2072.08  491.772072.628   494.6 2073.28
   517.4  2083.5   527.2 2087.22   540.2 2095.79   553.3 2102.54   579.4 2113.57
   608.7 2128.65   634.8  2139.4   651.1 2143.59  678.432147.463   696.7    2150
#Mann= 6 ,-1 , 0
       0     .06       0   414.7    .045       0   429.7     .06       0
  451.41    .016       0  491.77     .12       0  678.43     .06       0
#XS Ineff= 2 , 0
          290.45 2065.29
Permanent Ineff=
       F       F
Bank Sta=414.7,429.7
XS Rating Curve= 0 ,0
Exp/Cntr=0.3,0.1

Type RM Length L Ch R = 1 ,73869.3 ,230.2,219.4,208.3
XS GIS Cut Line= 4
     2075332.373      171843.411     2075617.095      171898.966
     2075908.762      171850.355     2076122.635      171617.362
#Sta/Elev= 30
       0 2092.09    52.2 2083.98   120.6  2074.2   211.9 2058.79   247.7 2054.21
   290.1 2050.81   345.3 2047.48   465.6 2046.87     480 2045.71     485 2044.61
   488.3 2044.59     495 2045.25   520.8 2046.17   527.3  2047.8     550 2055.45
     563 2058.69     576 2061.01  623.492065.168  637.412067.625   657.5 2071.69
   670.6 2071.67   674.42072.287   686.9 2077.47   699.9 2079.28   712.9 2083.26
   784.7  2098.9   804.2 2102.26   853.2 2109.39  890.792117.307     902    2120
#Mann= 7 ,-1 , 0
       0     .06       0     480    .045       0     495     .06       0
  623.49     .12       0  637.41    .016       0   674.4     .12       0
  890.79     .06       0
#XS Ineff= 2 , 0
          359.53 2055.33
Permanent Ineff=
       F       F
Bank Sta=480,495
XS Rating Curve= 0 ,0
Exp/Cntr=0.3,0.1

Type RM Length L Ch R = 1 ,73649.9 ,519.8,547.3,568
XS GIS Cut Line= 4
      2075561.54      172148.966     2075724.698      172195.388
     2076176.179      171840.458     2076196.313      171720.311
#Sta/Elev= 30
       0 2058.63    16.3 2057.86   101.1 2049.31   205.5 2044.46   326.3 2042.34
   378.5 2043.38   391.5 2041.64   401.3 2041.85   414.4 2043.16   420.9 2041.95
   427.4 2040.65   437.2 2042.04   473.1  2042.8   495.9  2046.4   512.2 2047.45
   561.2 2047.55   580.8 2046.87   610.1  2047.2   642.8 2046.61  723.122050.109
   747.1 2050.14   756.8 2048.87  763.842049.046   769.6 2049.35   772.8 2050.39
   779.2 2054.74   782.4 2056.15     792 2058.03   811.2 2064.48   865.8    2080
#Mann= 5 ,-1 , 0
       0     .06       0   420.9    .045       0   437.2     .06       0
  723.12    .016       0  763.84     .12       0
Bank Sta=420.9,437.2
XS Rating Curve= 0 ,0
Exp/Cntr=0.3,0.1

Type RM Length L Ch R = 1 ,73102.6 ,222.4,226.3,228.7
XS GIS Cut Line= 2
     2075665.706      172291.328     2076280.983       172491.47
#Sta/Elev= 30
       0 2049.98    52.3 2045.19    91.5 2042.97   124.2  2040.5   173.2 2039.49
   238.5 2036.64   254.9 2036.49  276.662037.233  285.192037.194   290.8 2036.92
   312.5 2033.26   323.5 2032.29   327.5 2033.32     330 2034.36   333.3 2035.14
     366 2035.97  374.352036.537   385.6 2037.91   401.9 2038.16  411.472040.509
   424.8 2045.26   437.9 2051.72   454.2 2057.53   493.4 2069.09   516.3 2074.98
   532.6 2078.74   594.7 2091.05   614.3 2094.69   640.5 2098.66     647    2100
#Mann= 7 ,-1 , 0
       0     .06       0  276.66     .12       0  285.19     .06       0
   312.5    .045       0   327.5     .06       0  374.35    .016       0
  411.47     .12       0
#XS Ineff= 2 , 0
           248.5 2043.92
Permanent Ineff=
       F       F
Bank Sta=312.5,327.5
XS Rating Curve= 0 ,0
Exp/Cntr=0.3,0.1

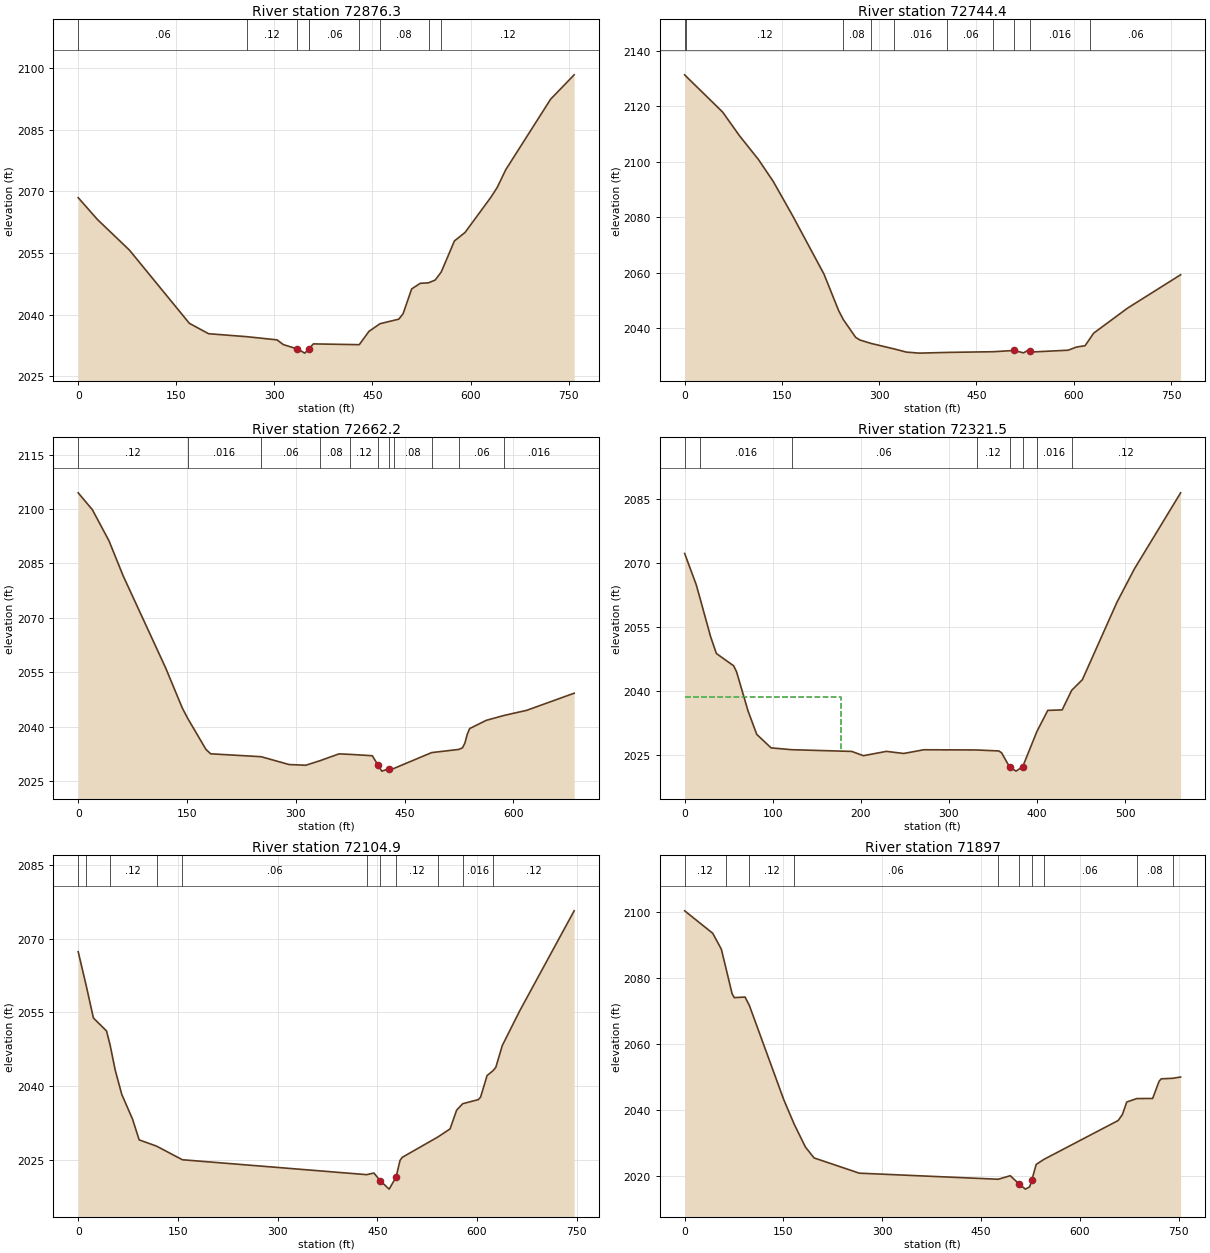
Type RM Length L Ch R = 1 ,72876.3 ,135.8,131.9,127.7
XS GIS Cut Line= 3
     2075578.901      172444.105     2076110.151      172704.522
     2076276.817      172707.994
#Sta/Elev= 30
       0 2068.49    29.4 2063.17    78.4  2055.7     170 2037.87   199.4 2035.34
  258.032034.614     304 2033.84   313.8 2032.68   334.7 2031.66   346.5 2030.61
     353 2031.65  353.632031.839   359.6 2032.86  429.782032.669   444.6 2035.91
  461.492037.777   490.3 2038.89   496.8 2040.21   509.9 2046.25     523 2047.62
  535.682047.739   545.9 2048.42  555.152050.375   575.3 2057.94   591.6 2060.02
   630.9 2068.55   640.7 2070.96   653.8  2075.3   722.4 2092.48   758.4 2098.42
#Mann= 9 ,-1 , 0
       0     .06       0  258.03     .12       0   334.7    .045       0
     353     .12       0  353.63     .06       0  429.78    .016       0
  461.49     .08       0  535.68     .06       0  555.15     .12       0
Bank Sta=334.7,353
XS Rating Curve= 0 ,0
Exp/Cntr=0.3,0.1

Type RM Length L Ch R = 1 ,72744.4 ,82.1,82.2,82.3
XS GIS Cut Line= 4
     2075367.095      172770.494     2075634.456        172732.3
     2075787.234      172694.105     2076110.151      172791.328
#Sta/Elev= 30
       0 2131.37    2.562130.746    58.6 2117.94    84.6  2109.4   113.9 2100.81
   136.7 2092.91     166  2080.8   214.8 2059.57   237.5 2046.38  244.642043.179
   263.6 2036.78   270.1 2035.82  287.772034.555  322.472032.629   342.2 2031.44
   361.9 2031.08  405.14 2031.34  475.922031.588   508.2 2032.04   522.5 2031.17
     529 2032.02   532.3 2031.83   538.9 2031.53   591.3 2032.13   604.4 2033.28
   617.4 2033.75  625.252036.394   630.6 2038.26   682.9 2047.28   764.8 2059.32
#Mann= 10 ,-1 , 0
       0     .06       0    2.56     .12       0  244.64     .08       0
  287.77     .12       0  322.47    .016       0  405.14     .06       0
  475.92    .016       0   508.2    .045       0   532.3    .016       0
  625.25     .06       0
Bank Sta=508.2,532.3
XS Rating Curve= 0 ,0
Exp/Cntr=0.3,0.1

Type RM Length L Ch R = 1 ,72662.2 ,333.1,340.6,346.9
XS GIS Cut Line= 4
     2075429.595      172836.466     2075617.095      172812.161
     2075769.873      172773.966      2076092.79      172871.189
#Sta/Elev= 30
       0 2104.45    19.6 2099.78    42.4 2091.26    61.9 2081.64   120.6 2056.24
   143.4 2045.27  150.732042.458     176 2033.86   182.6 2032.61  252.22 2031.81
   290.8 2029.65   313.7 2029.46  333.242030.701   359.6 2032.59  374.892032.453
   405.5 2032.08   412.9 2029.66   418.6 2027.84   427.9 2028.44  434.752028.536
  487.31 2032.94  524.662033.815   529.9 2034.27   533.2 2035.59   536.4 2037.97
   539.7 2039.55   562.6 2041.82  587.222043.171   618.3 2044.57   683.8 2049.29
#Mann= 11 ,-1 , 0
       0     .12       0  150.73    .016       0  252.22     .06       0
  333.24     .08       0  374.89     .12       0   412.9    .045       0
   427.9     .12       0  434.75     .08       0  487.31    .016       0
  524.66     .06       0  587.22    .016       0
Bank Sta=412.9,427.9
XS Rating Curve= 0 ,0
Exp/Cntr=0.3,0.1

Type RM Length L Ch R = 1 ,72321.5 ,216.7,216.6,214.4
XS GIS Cut Line= 3
     2075422.651      172885.078      2075780.29       173138.55
     2075901.817      173166.328
#Sta/Elev= 30
       0 2072.17    13.1 2064.88   17.732061.474    29.4 2052.74      36 2048.77
    55.6  2045.9    58.9  2044.5      72  2035.3    81.8 2029.86    98.1  2026.7
  121.632026.271   189.7 2025.87   202.8 2024.87     229 2025.88   248.6 2025.39
   271.5 2026.26   331.32026.209   356.6 2025.98   359.8 2025.55   368.8 2022.24
   376.2 2021.26   383.8 2022.33  399.852030.532   412.2 2035.47   428.5 2035.58
  439.32 2040.16   451.5 2042.66   490.8  2060.8   510.5 2068.56     563 2086.36
#Mann= 8 ,-1 , 0
       0     .12       0   17.73    .016       0  121.63     .06       0
   331.3     .12       0   368.8    .045       0   383.8     .12       0
  399.85    .016       0  439.32     .12       0
#XS Ineff= 2 , 0
          177.05  2038.5
Permanent Ineff=
       F       F
Bank Sta=368.8,383.8
XS Rating Curve= 0 ,0
Exp/Cntr=0.3,0.1

Type RM Length L Ch R = 1 ,72104.9 ,209,207.9,209
XS GIS Cut Line= 4
     2075367.095      172898.966     2075471.262      173003.133
      2075499.04      173190.633     2075835.845      173423.272
#Sta/Elev= 30
       0 2067.32   12.242060.301    22.9 2053.84    42.6 2051.21   47.892048.411
    55.6 2043.29    65.5 2038.32    81.8 2033.26    91.7 2029.06  117.812027.789
  156.762025.015  434.012021.984   444.9 2022.31   454.8  2020.7   467.8 2019.04
   478.2 2021.45   484.2 2024.88   487.5  2025.5  541.052029.634   559.5 2031.29
   569.4 2035.11  578.492036.412   602.1 2037.25   605.4 2037.75   615.2 2042.14
  623.912043.095   628.3  2043.8   638.1 2048.25   664.3  2055.3   746.2 2075.64
#Mann= 11 ,-1 , 0
       0     .12       0   12.24    .016       0   47.89     .12       0
  117.81    .016       0  156.76     .06       0  434.01     .12       0
   454.8    .045       0   478.2     .12       0  541.05     .08       0
  578.49    .016       0  623.91     .12       0
Bank Sta=454.8,478.2
XS Rating Curve= 0 ,0
Exp/Cntr=0.3,0.1

Type RM Length L Ch R = 1 ,71897   ,250,249.5,246.4
XS GIS Cut Line= 2
      2075055.62      173138.038     2075679.364      173560.121
#Sta/Elev= 30
       0 2100.43    42.6 2093.62    55.7 2088.79   62.492083.186      72  2075.3
    75.3 2074.11    91.7 2074.28   98.262071.719   150.6  2043.1  166.392035.694
   183.4 2028.79   196.5  2025.5   265.2 2020.88  476.282019.033   494.4 2020.11
   507.1 2017.73   517.4 2016.04   523.9 2016.74   527.2 2018.77   533.7 2023.51
  545.282025.037   658.2 2036.84   664.7 2038.66   671.3 2042.46  686.562043.506
   710.6 2043.52   720.4 2048.74   723.7 2049.49  740.892049.646   753.1 2050.04
#Mann= 10 ,-1 , 0
       0     .12       0   62.49    .016       0   98.26     .12       0
  166.39     .06       0  476.28     .12       0   507.1    .045       0
   527.2     .12       0  545.28     .06       0  686.56     .08       0
  740.89    .016       0
Bank Sta=507.1,527.2
XS Rating Curve= 0 ,0
Exp/Cntr=0.3,0.1

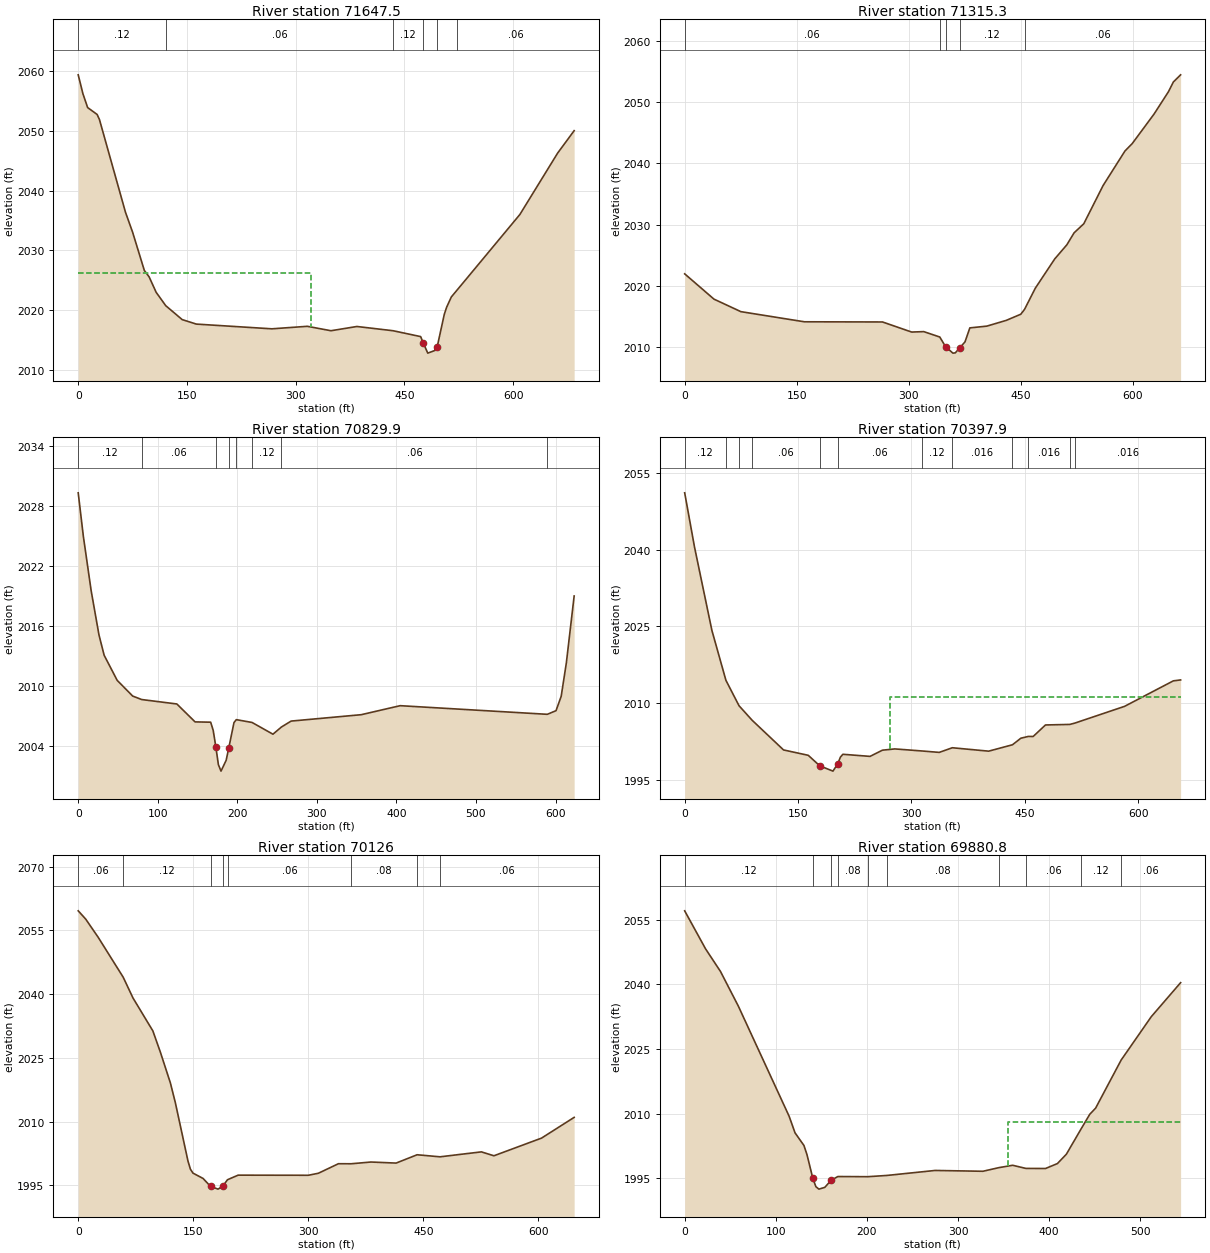
Type RM Length L Ch R = 1 ,71647.5 ,317.2,332.2,345.5
XS GIS Cut Line= 4
     2074997.724      173342.663     2075040.553      173462.321
     2075395.012      173655.845     2075546.279      173679.397
#Sta/Elev= 30
       0 2059.33     6.5 2056.17      13 2053.86    26.1 2052.71    29.3 2051.86
    65.2 2036.37      75 2033.05    91.2 2026.65    97.8 2025.58   107.5    2023
  120.752020.762   143.4 2018.44   162.9 2017.69   267.1  2016.9     316 2017.32
   348.6 2016.58   384.4 2017.29  434.452016.578   472.3  2015.6   476.2 2014.46
   482.1 2012.84   491.9 2013.28   495.1 2013.89   504.9 2019.32   508.1  2020.5
   514.6 2022.22  522.462023.363   609.1 2035.99   661.2 2046.25     684    2050
#Mann= 6 ,-1 , 0
       0     .12       0  120.75     .06       0  434.45     .12       0
   476.2    .045       0   495.1     .12       0  522.46     .06       0
#XS Ineff= 2 , 0
          320.92 2026.19
Permanent Ineff=
       F       F
Bank Sta=476.2,495.1
XS Rating Curve= 0 ,0
Exp/Cntr=0.3,0.1

Type RM Length L Ch R = 1 ,71315.3 ,486.1,485.4,484
XS GIS Cut Line= 4
      2074963.16      173541.183     2075147.852      173739.897
     2075238.522      173919.673     2075421.493      173975.211
#Sta/Elev= 30
       0 2021.93    39.2 2017.79    75.2 2015.74   160.2 2014.08   264.8 2014.05
   303.8  2012.4     320 2012.47  341.442011.588   349.2 2010.01     359 2008.95
   362.2 2008.99   368.4 2009.85   375.2 2010.79   381.7 2013.08   404.4 2013.37
   430.4 2014.31   449.9 2015.32  454.932016.122   469.4  2019.6   495.3 2024.37
   511.5 2026.68   521.2 2028.64   534.2 2030.13   560.1  2036.4   589.3 2042.04
     599 2043.25   628.2 2048.08   647.6 2051.76   654.1 2053.34   663.8 2054.51
#Mann= 5 ,-1 , 0
       0     .06       0  341.44     .12       0   349.2    .045       0
   368.4     .12       0  454.93     .06       0
Bank Sta=349.2,368.4
XS Rating Curve= 0 ,0
Exp/Cntr=0.3,0.1

Type RM Length L Ch R = 1 ,70829.9 ,423.8,432,439.4
XS GIS Cut Line= 2
     2074629.827      173751.252     2074935.382      174294.655
#Sta/Elev= 30
       0 2029.34     6.5 2024.97    16.3 2019.55    26.1 2015.14    32.6 2013.11
      49  2010.6    68.5 2009.03   79.772008.684     124 2008.24   146.9 2006.45
   166.5 2006.42   169.7  2005.6   173.1  2003.9   176.2 2002.18   179.5 2001.53
     186 2002.62   189.3 2003.86   195.8 2006.38  198.742006.674  218.532006.392
   244.8 2005.22  255.442005.938   267.6 2006.53   355.8 2007.17   404.7 2008.07
  589.662007.207   600.6 2007.57   607.1    2009   613.6 2012.35   623.4 2019.03
#Mann= 8 ,-1 , 0
       0     .12       0   79.77     .06       0   173.1    .045       0
   189.3     .12       0  198.74     .06       0  218.53     .12       0
  255.44     .06       0  589.66     .12       0
Bank Sta=173.1,189.3
XS Rating Curve= 0 ,0
Exp/Cntr=0.3,0.1

Type RM Length L Ch R = 1 ,70397.9 ,270.6,271.8,272.3
XS GIS Cut Line= 3
      2074275.66      173836.322     2074383.299      174428.336
     2074411.077      174475.211
#Sta/Elev= 30
       0 2051.08    13.1 2040.42      36 2024.21   54.552014.454   71.912009.478
   89.172006.653   130.8 2000.84   163.5 1999.79   178.8 1997.73   196.2  1996.7
   202.8 1998.19     206 1999.42   209.3 1999.99   245.3 1999.58   261.6 2000.79
     278 2001.04  314.552000.632   336.8 2000.36  354.122001.267   402.2  2000.6
  433.752001.852   444.8 2003.13  454.642003.479   461.1 2003.47   477.4 2005.72
   509.62005.825  516.132006.079   582.1 2009.36   646.6 2014.34   656.2 2014.52
#Mann= 12 ,-1 , 0
       0     .12       0   54.55     .06       0   71.91     .12       0
   89.17     .06       0   178.8    .045       0   202.8     .06       0
  314.55     .12       0  354.12    .016       0  433.75     .06       0
  454.64    .016       0   509.6     .08       0  516.13    .016       0
#XS Ineff= 2 , 0
                          271.06         2011.17
Permanent Ineff=
       F       F
Bank Sta=178.8,202.8
XS Rating Curve= 0 ,0
Exp/Cntr=0.3,0.1

Type RM Length L Ch R = 1 ,70126   ,240.2,245.3,249.5
XS GIS Cut Line= 3
     2074055.174      173858.891     2074029.132      173952.641
     2074108.993      174496.044
#Sta/Elev= 30
       0  2059.6     9.7 2057.67      26 2053.38   58.672043.966    71.4 2039.09
    97.3 2031.34   107.1 2026.34   120.2 2019.06   126.7 2014.38   143.1 2000.69
   146.3 1998.78   149.6 1997.86   162.7 1996.61   172.5 1994.74   182.3 1994.09
   188.6 1994.82  194.611996.303   208.5 1997.38     300 1997.35   313.1 1997.83
   339.2 2000.07  355.78 2000.06   381.7 2000.47   414.4 2000.22   441.82002.179
  471.652001.695   525.6 2002.86   541.9 2001.94     604  2006.1   646.5 2010.98
#Mann= 8 ,-1 , 0
       0     .06       0   58.67     .12       0   172.5    .045       0
   188.6     .12       0  194.61     .06       0  355.78     .08       0
   441.8    .016       0  471.65     .06       0
Bank Sta=172.5,188.6
XS Rating Curve= 0 ,0
Exp/Cntr=0.3,0.1

Type RM Length L Ch R = 1 ,69880.8 ,487.1,493.3,498.4
XS GIS Cut Line= 3
     2073808.646      173919.655     2073784.341      174334.586
     2073716.632      174443.961
#Sta/Elev= 30
       0 2057.05    22.9 2048.24    39.3 2042.99    58.9 2034.95   114.6 2009.43
   121.1 2005.57   130.9 2002.63   134.2 2000.53   140.7 1994.98     144 1993.08
   147.3 1992.51   153.8 1992.92   160.8 1994.58  168.141995.429  200.981995.393
  221.941995.682   274.9 1996.84   327.3 1996.65  344.851997.494     360 1998.04
  374.441997.314     396 1997.29   409.1 1998.44   418.9  2000.6  434.722006.345
   444.6 2009.87     451 2011.29  479.042022.443   512.1  2032.5   544.3 2040.39
#Mann= 10 ,-1 , 0
       0     .12       0   140.7    .045       0   160.8     .12       0
  168.14     .08       0  200.98     .12       0  221.94     .08       0
  344.85    .016       0  374.44     .06       0  434.72     .12       0
  479.04     .06       0
#XS Ineff= 2 , 0
                          354.78            2008
Permanent Ineff=
       F       F
Bank Sta=140.7,160.8
XS Rating Curve= 0 ,0
Exp/Cntr=0.3,0.1

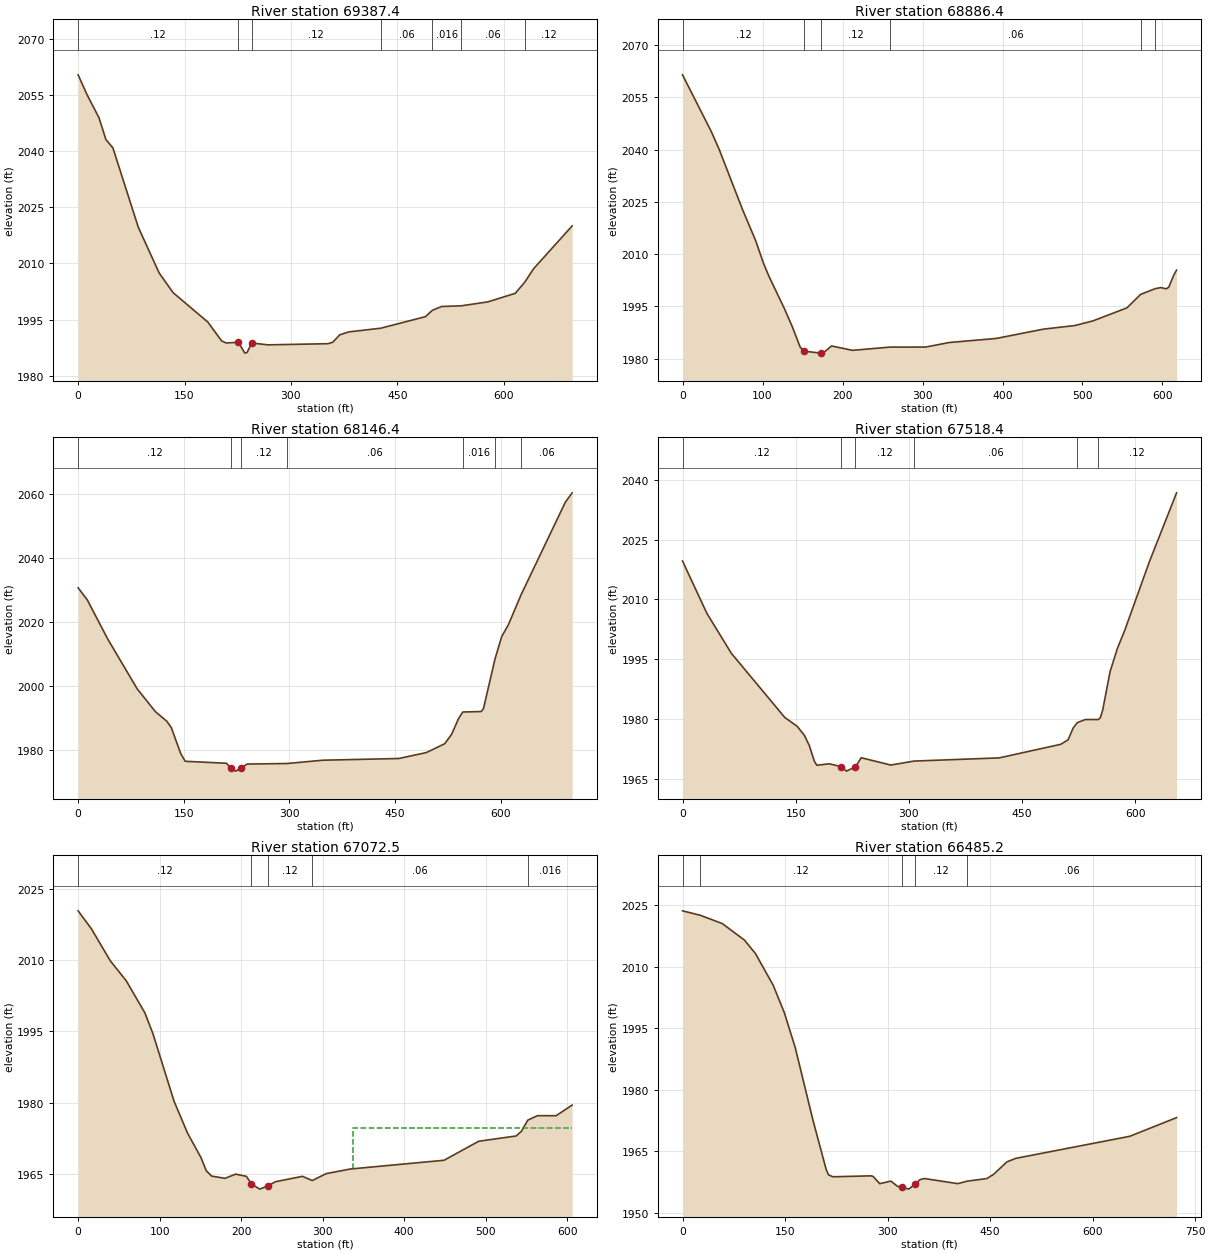
Type RM Length L Ch R = 1 ,69387.4 ,496.4,501,501.9
XS GIS Cut Line= 3
     2073394.684      173749.234     2073219.336      174299.581
     2073308.646      174377.988
#Sta/Elev= 30
       0 2060.41      13 2054.94    29.4 2048.96    39.2  2043.1      49  2040.9
    84.8 2019.69   114.2 2007.47   133.8 2002.22   182.8 1994.35   202.3  1989.3
   208.8 1988.75     226 1988.94     235 1986.04   238.2 1986.24   244.8 1988.75
   267.6 1988.25   352.4 1988.56     359 1988.96   368.8 1990.93   381.8 1991.72
   426.41992.693   489.5 1995.78  499.471997.494   512.3  1998.5  540.141998.683
   577.6 1999.74   616.2 2002.02  629.752005.037   641.8 2008.54   696.4 2020.05
#Mann= 7 ,-1 , 0
       0     .12       0     226    .045       0   244.8     .12       0
   426.4     .06       0  499.47    .016       0  540.14     .06       0
  629.75     .12       0
Bank Sta=226,244.8
XS Rating Curve= 0 ,0
Exp/Cntr=0.3,0.1

Type RM Length L Ch R = 1 ,68886.4 ,754.7,740,723.9
XS GIS Cut Line= 3
     2073003.337      173655.229     2072818.673      174070.389
     2072789.302      174230.956
#Sta/Elev= 30
       0 2061.51      36  2045.2    45.8 2040.11    75.2 2022.71    91.5 2013.84
   101.3 2007.34   107.9 2003.71   127.5 1994.28   137.3 1989.12   147.1 1983.28
   152.2 1982.11   173.2 1981.56   176.5 1981.73   186.3 1983.62   212.5 1982.36
  259.461983.291     304  1983.3   333.4 1984.61   392.3 1985.78   451.1 1988.45
   490.3 1989.48   513.1 1990.82   555.6 1994.57  572.721998.449     5912000.087
     598 2000.39   604.6 2000.03   607.8 2000.48   614.3 2004.07   617.6  2005.4
#Mann= 6 ,-1 , 0
       0     .12       0   152.2    .045       0   173.2     .12       0
  259.46     .06       0  572.72    .016       0     591     .08       0
Bank Sta=152.2,173.2
XS Rating Curve= 0 ,0
Exp/Cntr=0.3,0.1

Type RM Length L Ch R = 1 ,68146.4 ,622.5,628,630
XS GIS Cut Line= 4
     2072294.757      173549.863     2072266.979      173662.711
     2072393.716      174070.697     2072336.424      174218.266
#Sta/Elev= 30
       0 2030.68    12.9 2026.95      42 2014.72    83.9 1999.14   109.8 1992.02
     126 1989.03   132.5 1986.99   145.6 1979.01   152.1 1976.54   210.8 1975.92
   216.7 1974.42   223.8 1973.47   231.7 1974.46   240.1 1975.68  296.551975.841
   347.8 1976.88   455.4 1977.41   494.5 1979.25   520.6 1982.01   530.4 1984.94
   540.2  1989.8  546.291991.914   572.5 1992.07   575.7 1992.96  592.182008.556
   601.6 2015.45   611.3 2019.24  628.962028.422     692  2057.4   701.7 2060.32
#Mann= 7 ,-1 , 0
       0     .12       0   216.7    .045       0   231.7     .12       0
  296.55     .06       0  546.29    .016       0  592.18     .12       0
  628.96     .06       0
Bank Sta=216.7,231.7
XS Rating Curve= 0 ,0
Exp/Cntr=0.3,0.1

Type RM Length L Ch R = 1 ,67518.4 ,441,446,443.5
XS GIS Cut Line= 3
     2071827.743      173508.197     2071740.938      173612.363
     2071721.841      174131.461
#Sta/Elev= 30
       0 2019.62    32.3 2006.54    64.6 1996.58   135.6 1980.49   151.9  1978.3
   161.7 1975.99   168.3 1973.37   174.8 1969.54   178.1 1968.54   194.4  1968.9
   210.7 1968.19   217.3 1967.07   229.3 1968.14   236.9 1970.42   276.1 1968.59
  307.091969.585   419.8 1970.38   501.5 1973.78   511.3 1974.92   517.8 1977.82
  523.35 1979.19   534.2 1979.98  550.991979.971   553.8 1980.38     557 1982.27
   566.8 1991.93   576.6 1997.79   586.4 2002.34   619.1 2019.52     655 2036.68
#Mann= 6 ,-1 , 0
       0     .12       0   210.7    .045       0   229.3     .12       0
  307.09     .06       0  523.35    .016       0  550.99     .12       0
Bank Sta=210.7,229.3
XS Rating Curve= 0 ,0
Exp/Cntr=0.3,0.1

Type RM Length L Ch R = 1 ,67072.5 ,592,587.2,581.9
XS GIS Cut Line= 2
     2071319.063      173431.808     2071329.479      174037.711
#Sta/Elev= 30
       0 2020.33    16.4 2016.53    39.3 2009.87      59 2005.64    81.9  1998.9
    91.7 1994.56   117.9 1980.23   134.3 1973.61   150.7  1968.5   157.2 1965.73
   163.8  1964.6   180.2 1964.14   193.3 1965.02   206.4 1964.55   212.6 1962.97
   222.7 1961.87   232.6 1962.55   242.4 1963.44   275.2 1964.56  287.171963.682
   304.6 1965.14   334.1  1966.1   448.8 1967.93   491.4 1971.93   537.2 1973.03
   543.8 1974.02  551.551976.357   563.4  1977.3   586.3 1977.29     606 1979.53
#Mann= 5 ,-1 , 0
       0     .12       0   212.6    .045       0   232.6     .12       0
  287.17     .06       0  551.55    .016       0
#XS Ineff= 2 , 0
                          336.74         1974.75
Permanent Ineff=
       F       F
Bank Sta=212.6,232.6
XS Rating Curve= 0 ,0
Exp/Cntr=0.3,0.1

Type RM Length L Ch R = 1 ,66485.2 ,693.4,693.4,687.1
XS GIS Cut Line= 3
     2070832.952      173292.919     2070753.091      173487.363
     2070801.702       173997.78
#Sta/Elev= 30
       0 2023.59   25.982022.505    58.2 2020.48    90.6 2016.46   106.7 2013.18
   132.6 2005.47   148.8 1998.84   164.9 1990.27   190.8 1972.59   210.2 1960.54
   213.5 1959.25     220 1958.75   275.5 1958.98   278.8 1958.85   288.6 1957.07
   304.9  1957.7   314.7 1956.41   320.9 1956.26     331 1955.74   340.8 1957.01
   347.4 1958.05   353.9 1958.32   402.9 1957.08  416.381957.674   445.3 1958.32
   455.1 1959.33   474.7 1962.39   487.8 1963.25   654.4 1968.62   722.9 1973.17
#Mann= 5 ,-1 , 0
       0     .06       0   25.98     .12       0   320.9    .045       0
   340.8     .12       0  416.38     .06       0
Bank Sta=320.9,340.8
XS Rating Curve= 0 ,0
Exp/Cntr=0.3,0.1