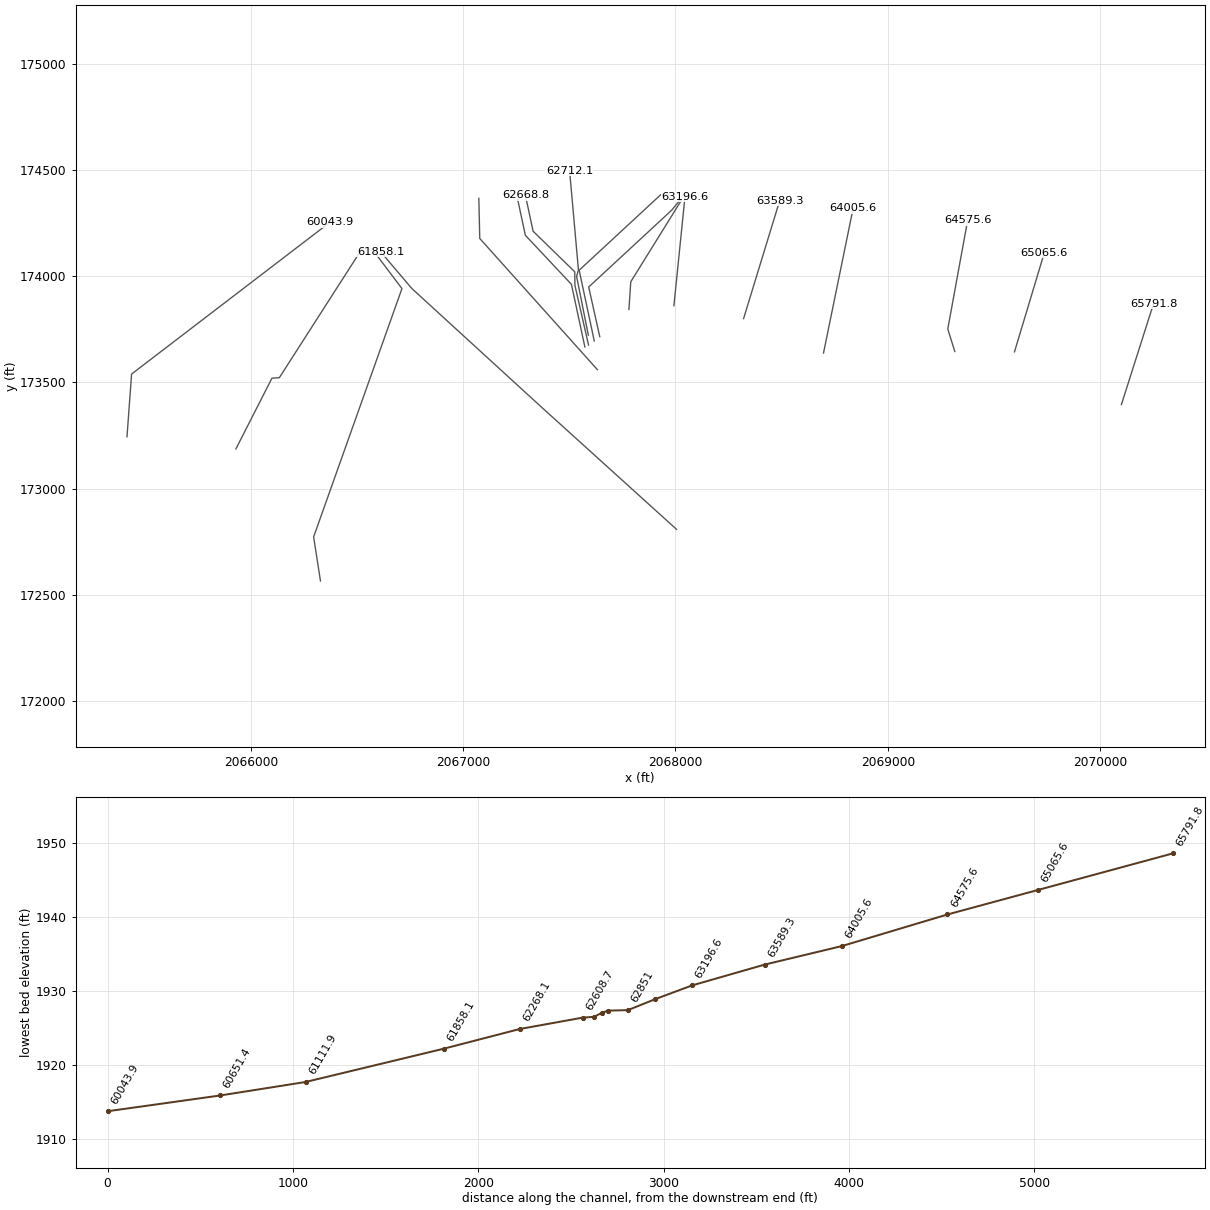
HEC-RAS study HNSCK.prj: HNSCK

--- HNSCK.g01 (geometry) --- (continued)

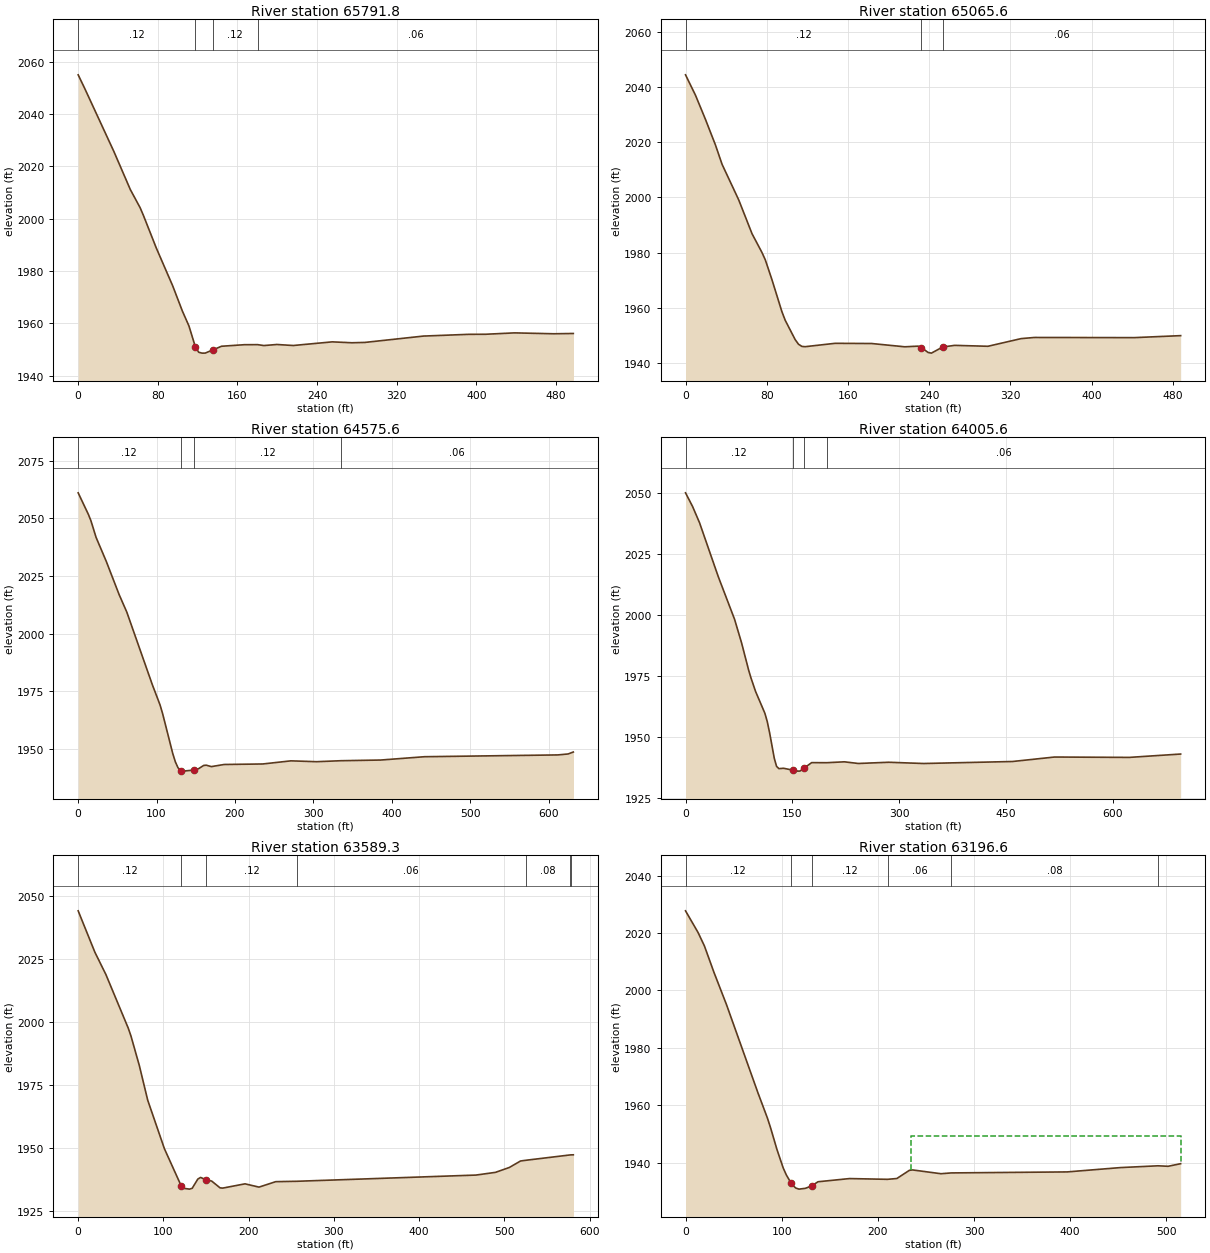
Type RM Length L Ch R = 1 ,65791.8 ,718.5,726.2,725.9
XS GIS Cut Line= 2
     2070100.313       173395.35     2070251.354      173869.308
#Sta/Elev= 30
       0 2054.96     6.6 2049.74      36 2025.54    52.4 2011.09    62.2 2004.18
    65.4 2001.35    78.5 1988.73    94.9 1974.34   104.7 1964.63   111.3 1958.93
   117.8 1950.86   121.1  1948.9   124.4 1948.56   127.6 1948.57     135 1949.74
     144 1951.19   166.9 1951.78  180.31  1951.8   186.5 1951.45   199.6 1951.86
     216 1951.47   255.3 1952.87   274.9 1952.52     288 1952.65   346.9 1955.08
   392.7 1955.75   409.1 1955.77   438.5  1956.3   477.8 1955.96   497.4 1956.07
#Mann= 4 ,-1 , 0
       0     .12       0   117.8    .045       0     135     .12       0
  180.31     .06       0
Bank Sta=117.8,135
XS Rating Curve= 0 ,0
Exp/Cntr=0.3,0.1

Type RM Length L Ch R = 1 ,65065.6 ,490.2,489.9,485.5
XS GIS Cut Line= 2
     2069596.841      173643.613     2069737.466      174110.627
#Sta/Elev= 30
       0  2044.4     9.8 2037.03    19.6 2028.31    29.5 2018.98      36    2012
    52.4 1999.12    65.5 1986.88    75.3 1980.07    78.6 1977.39    85.1 1970.27
    94.9 1958.68    98.2 1955.52     108 1948.53   111.3 1946.84   114.6 1946.07
   117.8 1945.96   147.3 1947.18   183.3 1947.11     216 1945.92   229.1 1946.16
   232.4 1945.63     239 1943.86   242.2 1943.63   253.3 1945.85   265.1 1946.44
   297.9 1946.11   330.6 1948.89   343.7  1949.3   441.9 1949.24   487.7 1949.96
#Mann= 3 ,-1 , 0
       0     .12       0   232.4    .045       0   253.3     .06       0
Bank Sta=232.4,253.3
XS Rating Curve= 0 ,0
Exp/Cntr=0.3,0.1

Type RM Length L Ch R = 1 ,64575.6 ,573.7,570,565.3
XS GIS Cut Line= 3
     2069315.591       173645.35     2069282.604      173751.252
     2069376.354      174263.405
#Sta/Elev= 30
       0 2061.04      13 2051.71    16.3 2048.91    22.8 2041.75    35.9 2031.26
    52.2 2016.93      62 2009.33    94.6 1977.81   104.4 1969.07   107.7 1965.28
   120.7 1947.88     124 1944.31   127.3 1941.81   130.6 1940.54   133.8 1940.31
   148.2 1940.79   153.5 1941.35     160 1942.76   163.3 1942.89   169.9 1942.27
   186.2 1943.19   235.4 1943.41   271.4 1944.77   304.1  1944.4  335.281944.826
     386 1945.12   441.7 1946.56   611.9 1947.34     625 1947.76   631.6  1948.6
#Mann= 4 ,-1 , 0
       0     .12       0   130.6    .045       0   148.2     .12       0
  335.28     .06       0
Bank Sta=130.6,148.2
XS Rating Curve= 0 ,0
Exp/Cntr=0.3,0.1

Type RM Length L Ch R = 1 ,64005.6 ,411.4,416.3,415.9
XS GIS Cut Line= 2
     2068697.344      173638.127     2068836.859       174319.47
#Sta/Elev= 30
       0    2050     9.8 2044.47    19.7 2037.75    45.9 2015.76    68.9 1998.21
    78.7  1988.6    88.6 1977.48    91.9 1974.25    98.4 1968.67   111.5 1959.71
   114.8 1956.35   118.1 1951.78   124.7 1941.27   127.9 1937.98   131.2 1937.06
   137.8 1937.21   150.9 1936.43   157.5 1936.04   160.8 1936.07   165.9 1937.15
   177.2 1939.52  198.311939.489   223.1 1939.85   242.8 1939.17   285.4 1939.67
   334.6 1939.16   459.3 1939.98   518.3 1941.81   623.3 1941.66   695.5 1943.04
#Mann= 4 ,-1 , 0
       0     .12       0   150.9    .045       0   165.9     .12       0
  198.31     .06       0
Bank Sta=150.9,165.9
XS Rating Curve= 0 ,0
Exp/Cntr=0.3,0.1

Type RM Length L Ch R = 1 ,63589.3 ,385.4,392.7,393.2
XS GIS Cut Line= 2
     2068320.799      173799.863     2068490.938      174355.419
#Sta/Elev= 30
       0    2044    19.6 2027.58    32.6 2018.67    58.8 1997.41      62 1994.26
    71.8 1982.54    81.6 1968.84   101.2 1949.58   120.8  1934.9     124 1933.86
   130.6 1933.54   133.8 1933.87   140.4 1937.53   143.6 1938.18   150.2 1937.25
   156.7 1936.73   166.5 1934.04   169.7 1933.95   195.8 1935.64   212.2 1934.34
   231.8  1936.5  256.621936.655   466.8 1939.12   489.6 1940.19     506 1942.14
     519  1944.7  525.051944.979  577.681947.129  578.771947.139     581 1947.16
#Mann= 7 ,-1 , 0
       0     .12       0   120.8    .045       0   150.2     .12       0
  256.62     .06       0  525.05     .08       0  577.68     .12       0
  578.77     .08       0
Bank Sta=120.8,150.2
XS Rating Curve= 0 ,0
Exp/Cntr=0.3,0.1

Type RM Length L Ch R = 1 ,63196.6 ,208.3,197.9,187.1
XS GIS Cut Line= 2
     2067992.674      173860.627     2068044.757       174372.78
#Sta/Elev= 30
       0 2027.77    13.1 2020.18    19.7 2015.48    29.5 2006.38    42.6 1995.06
    75.4 1964.21    85.2 1955.46    88.5 1952.03    95.1 1944.51   101.6 1938.07
   104.9 1935.61   109.6 1932.93   111.5 1932.02   114.8 1931.07     118 1930.72
   124.6    1931   131.2 1931.84   137.7 1933.29   170.5  1934.4  210.041934.139
   219.7 1934.42   232.8 1937.28   236.1 1937.41   265.6 1936.09   276.31936.371
   396.8 1936.72   452.5 1938.24  491.311938.855   501.7 1938.68   514.8 1939.59
#Mann= 6 ,-1 , 0
       0     .12       0   109.6    .045       0   131.2     .12       0
  210.04     .06       0   276.3     .08       0  491.31    .016       0
#XS Ineff= 2 , 0
                          234.03         1949.29
Permanent Ineff=
       F       F
Bank Sta=109.6,131.2
XS Rating Curve= 0 ,0
Exp/Cntr=0.3,0.1

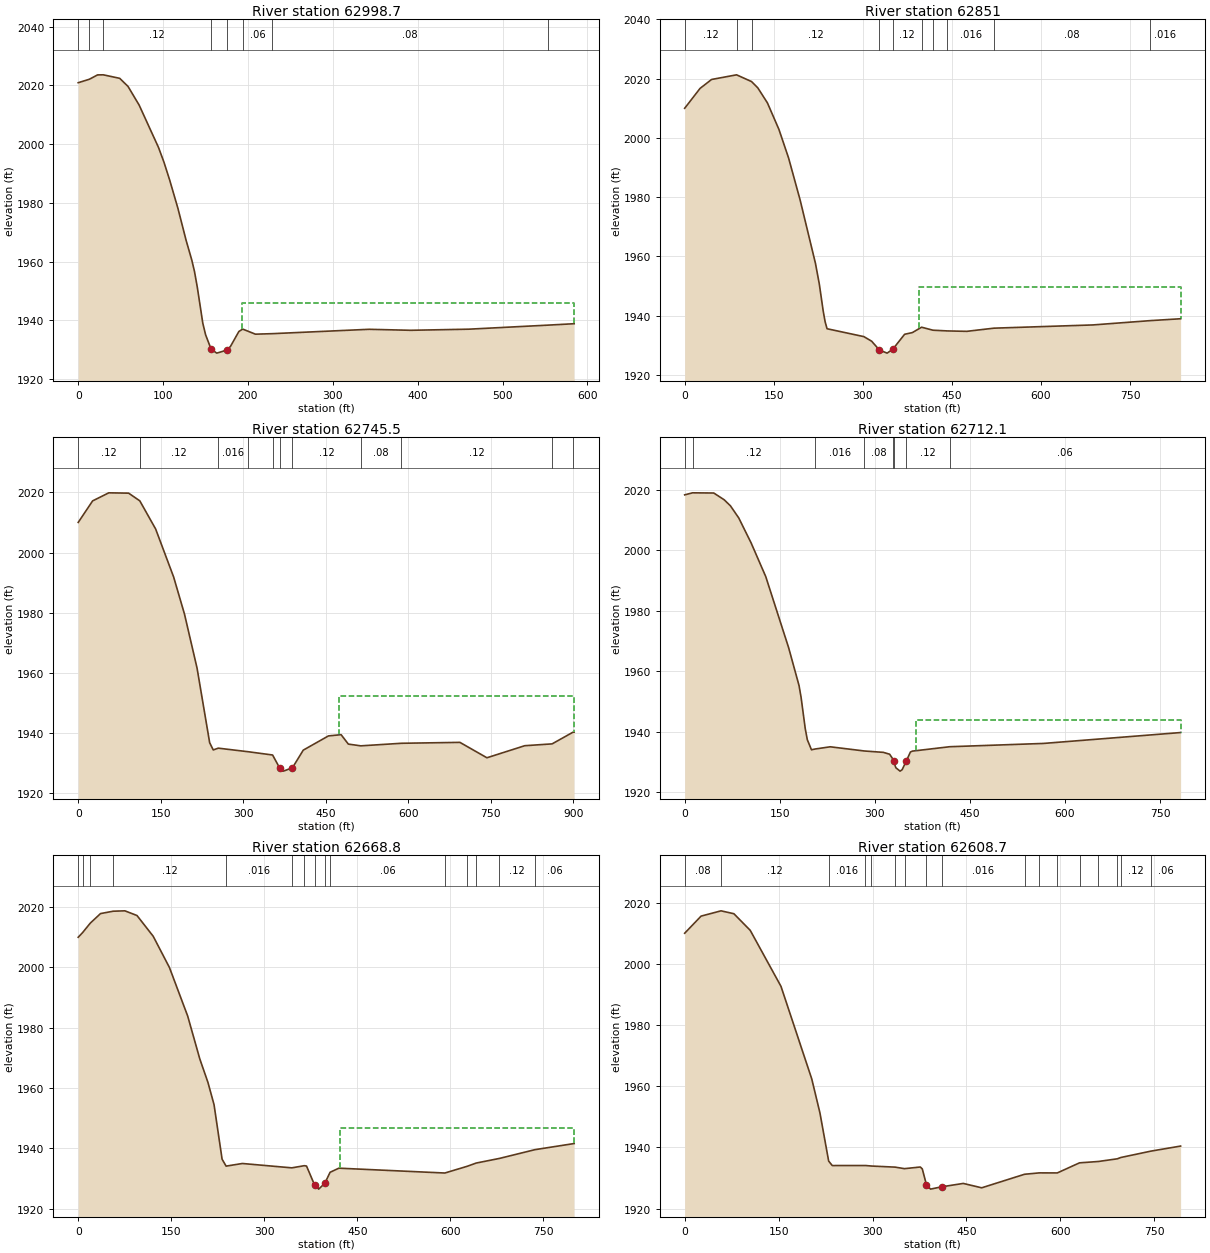
Type RM Length L Ch R = 1 ,62998.7 ,154,147.7,137.7
XS GIS Cut Line= 3
     2067780.868      173843.266     2067789.549      173973.475
     2068029.132      174358.891
#Sta/Elev= 30
       0 2020.91   13.222022.095    22.8 2023.57   29.552023.593    48.9  2022.4
    58.7 2019.64    71.8 2013.29    94.6 1998.88   101.1  1993.8   107.7 1987.83
   117.4 1978.23   127.2 1967.18   133.8 1960.57     137 1956.65   140.3 1951.32
   146.8 1939.04   150.1  1935.1   156.6 1930.22   163.2 1928.87   175.8 1929.95
   179.5 1931.21   189.3 1936.24  193.82 1937.05   208.8 1935.32   228.61935.492
   342.7 1936.98   391.7 1936.64   460.2 1937.02   552.91938.389   584.3 1938.88
#Mann= 8 ,-1 , 0
       0     .12       0   13.22     .08       0   29.55     .12       0
   156.6    .045       0   175.8     .12       0  193.82     .06       0
   228.6     .08       0   552.9    .016       0
#XS Ineff= 2 , 0
                          193.33            1946
Permanent Ineff=
       F       F
Bank Sta=156.6,175.8
XS Rating Curve= 0 ,0
Exp/Cntr=0.3,0.1

Type RM Length L Ch R = 1 ,62851   ,111.4,105.5,101.2
XS GIS Cut Line= 4
     2067643.454      173714.785     2067591.369      173948.721
     2067982.257       174310.28     2068022.188      174358.891
#Sta/Elev= 30
       0    2010    25.9 2016.71    45.3 2019.72   87.372021.289  112.61 2019.01
   123.1  2016.9   139.3 2011.83   158.7 2002.87   174.9 1993.26   194.3 1979.12
   220.2 1957.67   226.7 1950.68   233.2 1941.64   236.4 1938.03   239.7 1935.62
   301.7 1932.96   314.8 1931.41   327.9 1928.43   340.9 1927.39   350.5 1928.73
   370.3 1933.75   383.4 1934.32  398.811936.136  417.991935.126  442.31 1934.88
   474.9 1934.74  520.64 1935.81   687.2  1936.9  783.111938.343     835 1938.99
#Mann= 10 ,-1 , 0
       0     .12       0   87.37     .08       0  112.61     .12       0
   327.9    .045       0   350.5     .12       0  398.81     .08       0
  417.99     .06       0  442.31    .016       0  520.64     .08       0
  783.11    .016       0
#XS Ineff= 2 , 0
                          395.14         1949.57
Permanent Ineff=
       F       F
Bank Sta=327.9,350.5
XS Rating Curve= 0 ,0
Exp/Cntr=0.3,0.1

Type RM Length L Ch R = 1 ,62745.5 ,6.5,33.4,62.2
XS GIS Cut Line= 4
     2067617.575      173694.731     2067546.466      174027.684
     2067930.956      174383.413     2067968.368      174384.933
#Sta/Elev= 30
       0    2010    26.2 2017.16    55.6 2019.84    91.7 2019.73  111.842017.189
  112.282017.082   140.8 2007.81   173.5 1991.86   193.2 1979.55   216.1 1961.55
     239 1936.77   245.5 1934.37  254.771934.955   309.21933.764  353.421932.681
   366.6 1928.25   373.2 1927.32   389.6 1928.46   409.2  1934.3     455 1939.03
     478 1939.44   491.1 1936.31  513.791935.723  587.561936.577     694 1936.88
   743.1 1931.76   811.9 1935.77  861.65 1936.38  899.251940.227   901.7 1940.29
#Mann= 12 ,-1 , 0
       0     .12       0  111.84     .08       0  112.28     .12       0
  254.77    .016       0   309.2     .08       0  353.42     .12       0
   366.6    .045       0   389.6     .12       0  513.79     .08       0
  587.56     .12       0  861.65     .08       0  899.25    .016       0
#XS Ineff= 2 , 0
                          474.84         1952.43
Permanent Ineff=
       F       F
Bank Sta=366.6,389.6
XS Rating Curve= 0 ,0
Exp/Cntr=0.3,0.1

Type RM Length L Ch R = 1 ,62712.1 ,25.9,43.3,60.1
XS GIS Cut Line= 4
     2067589.536      173722.234     2067534.398      173998.822
     2067543.021       174029.03     2067501.354      174496.044
#Sta/Elev= 30
       0 2018.35   12.412019.021    45.9 2018.96    62.3 2016.73    72.2 2014.72
    85.3 2010.72   104.9 2002.42   127.9 1991.33     164 1967.83   180.4 1955.32
   183.6 1951.46   190.2 1941.07   193.5  1937.4     200  1934.1  205.691934.355
   229.6 1935.09  283.561933.705   313.4 1933.25   323.3 1932.64  328.041931.157
   329.4 1930.36   333.1 1928.17   339.7 1927.05     343 1927.51   349.5 1930.35
   356.1 1933.37   359.4 1933.67  417.981935.114   565.9  1936.2   782.3  1939.8
#Mann= 8 ,-1 , 0
       0     .08       0   12.41     .12       0  205.69    .016       0
  283.56     .08       0  328.04     .12       0   329.4    .045       0
   349.5     .12       0  417.98     .06       0
#XS Ineff= 2 , 0
                           365.4         1943.93
Permanent Ineff=
       F       F
Bank Sta=329.4,349.5
XS Rating Curve= 0 ,0
Exp/Cntr=0.3,0.1

Type RM Length L Ch R = 1 ,62668.8 ,57.1,60.2,182.5
XS GIS Cut Line= 5
       2067590.6      173675.774     2067526.511       173956.15
      2067525.66       174020.35     2067329.479      174211.322
     2067293.021      174381.461
#Sta/Elev= 30
       0    2010     7.12011.556   19.462014.686      36 2017.86   56.322018.642
    75.2 2018.77    94.8 2017.21   120.9 2010.34   147.1 1999.97   176.5 1983.88
   196.1 1969.62   209.2 1961.85     219 1954.49     232 1936.39  238.461934.109
   264.7 1934.98   344.41933.535  364.561934.251   368.1 1934.14   381.2  1927.8
   387.7 1926.48   397.6 1928.41  406.111932.066   420.3 1933.43   591.11931.822
  626.761934.027  641.861935.137  678.991936.652   736.51939.571   799.6  1941.6
#Mann= 15 ,-1 , 0
       0     .08       0     7.1     .12       0   19.46     .08       0
   56.32     .12       0  238.46    .016       0   344.4     .08       0
  364.56     .12       0   381.2    .045       0   397.6     .12       0
  406.11     .06       0   591.1    .016       0  626.76     .08       0
  641.86    .016       0  678.99     .12       0   736.5     .06       0
#XS Ineff= 2 , 0
                          421.48          1946.9
Permanent Ineff=
       F       F
Bank Sta=381.2,397.6
XS Rating Curve= 0 ,0
Exp/Cntr=0.3,0.1

Type RM Length L Ch R = 1 ,62608.7 ,346.2,340.6,215.7
XS GIS Cut Line= 4
     2067573.236      173666.892     2067510.035      173961.322
     2067293.021      174192.225     2067256.563      174362.363
#Sta/Elev= 30
       0    2010    26.2 2015.59   58.07 2017.32    78.6 2016.37   104.7 2010.94
   153.8 1992.64   202.9 1962.42     216  1951.3  229.931935.547   235.7 1934.08
  288.571934.098  298.281933.925  336.271933.565  351.051933.067   376.3 1933.61
   379.5 1932.96   386.1 1927.81   392.6 1926.38   410.2 1927.13   444.9 1928.24
   474.3 1926.81  542.761931.238  566.52 1931.69  595.081931.672  630.521934.968
  660.731935.413  690.941936.289  696.381936.712  744.821938.807     792 1940.45
#Mann= 17 ,-1 , 0
       0     .08       0   58.07     .12       0  229.93    .016       0
  288.57     .08       0  298.28    .016       0  336.27     .08       0
  351.05    .016       0   386.1    .045       0   410.2    .016       0
  542.76     .12       0  566.52    .016       0  595.08     .06       0
  630.52     .12       0  660.73    .016       0  690.94     .06       0
  696.38     .12       0  744.82     .06       0
Bank Sta=386.1,410.2
XS Rating Curve= 0 ,0
Exp/Cntr=0.3,0.1

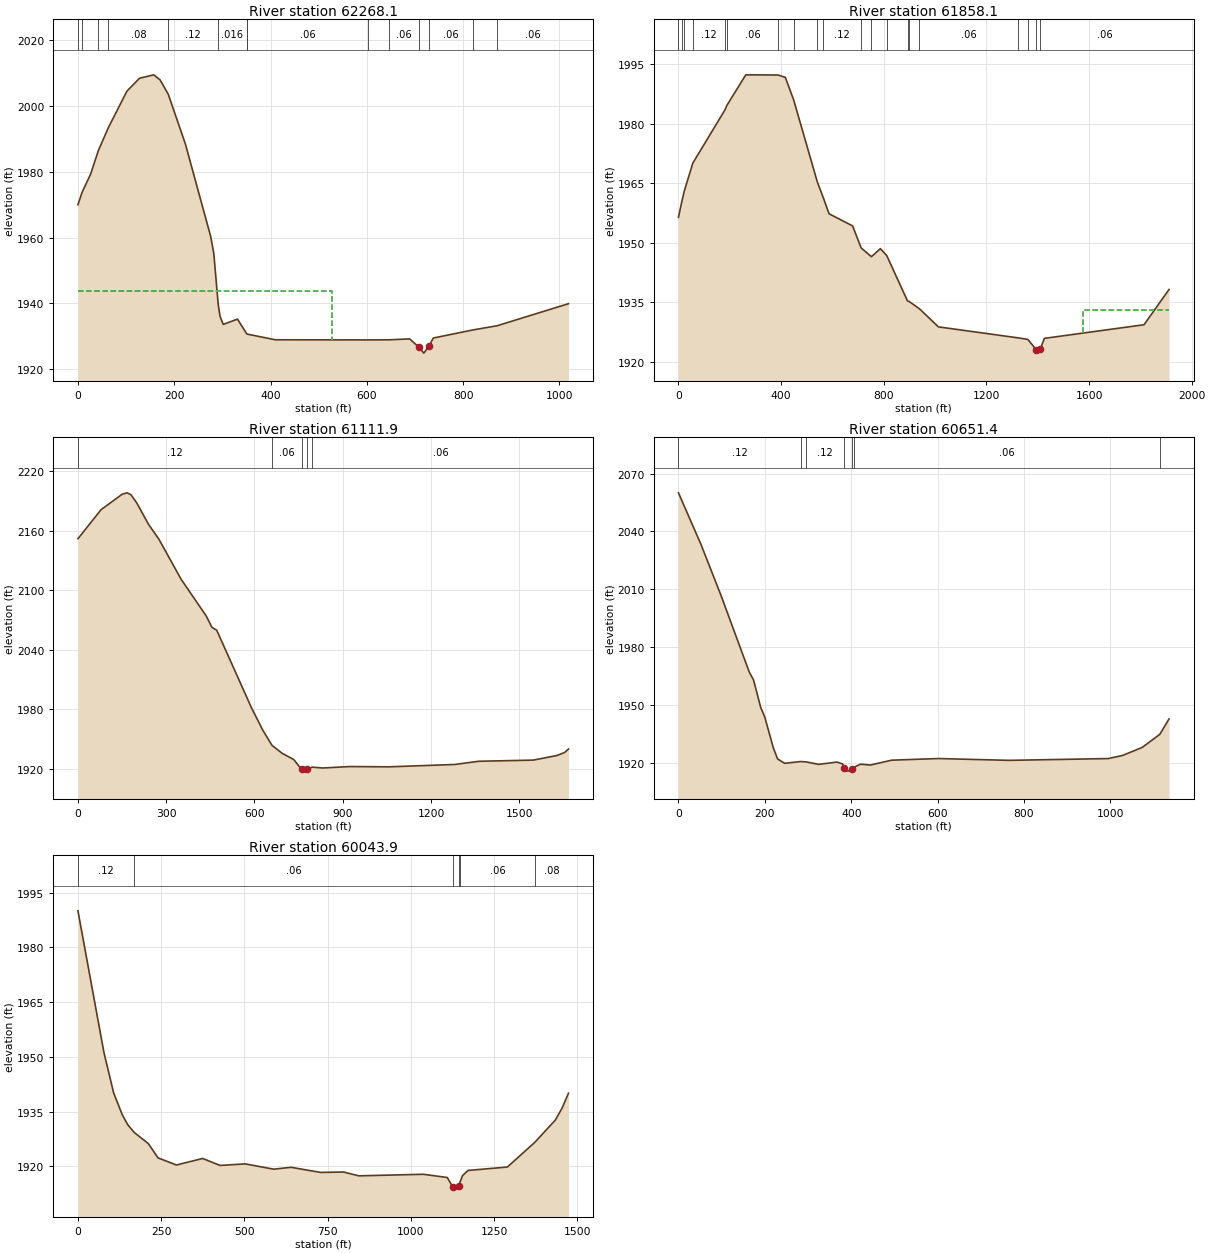
Type RM Length L Ch R = 1 ,62268.1 ,406.4,410,412.4
XS GIS Cut Line= 3
     2067632.499      173559.615     2067078.235      174177.207
     2067073.895      174366.009
#Sta/Elev= 30
       0    1970    8.631973.784    26.2 1979.27   42.441986.487   63.221993.468
   101.7 2004.56   127.9 2008.49   157.4 2009.53   170.6 2007.99  187.552003.622
     223 1988.56   275.5 1960.43   282.1 1955.24  291.281939.671   295.2 1935.96
   301.8 1933.58   331.3 1935.19  350.481930.714  352.041930.611     410  1928.9
  602.121928.861  645.921928.892   688.8 1929.17   708.5 1926.61   718.3 1924.84
   729.3 1927.08     738 1929.43  819.581931.878  870.63 1933.18  1018.7 1939.88
#Mann= 14 ,-1 , 0
       0    .016       0    8.63     .08       0   42.44     .06       0
   63.22     .08       0  187.55     .12       0  291.28    .016       0
  350.48     .08       0  352.04     .06       0  602.12    .016       0
  645.92     .06       0   708.5    .045       0   729.3     .06       0
  819.58    .016       0  870.63     .06       0
#XS Ineff= 2 , 0
          528.43 1943.81
Permanent Ineff=
       F       F
Bank Sta=708.5,729.3
XS Rating Curve= 0 ,0
Exp/Cntr=0.3,0.1

Type RM Length L Ch R = 1 ,61858.1 ,767.9,746.1,713.4
XS GIS Cut Line= 4
     2068005.124      172808.208     2067365.599      173386.442
     2066758.682      173941.371     2066611.655      174114.273
#Sta/Elev= 30
       0 1956.41   11.861960.043   22.811963.071    55.91970.086  182.111983.617
  188.021984.571   262.3 1992.35  387.841992.304   416.3 1991.72  448.58 1986.08
  541.551965.242  564.551961.334   586.8 1957.32   678.6 1954.26  711.861948.707
   751.81946.493   786.8 1948.52  811.491946.786  892.491935.345  899.151935.194
  939.181933.356  1012.9  1928.8 1321.821926.044 1361.421925.645  1394.4 1923.03
  1399.5 1922.18  1410.2  1923.2  1425.7  1925.9  1814.2 1929.34  1911.5 1938.22
#Mann= 20 ,-1 , 0
       0    .016       0   11.86     .08       0   22.81     .06       0
    55.9     .12       0  182.11     .08       0  188.02     .06       0
  387.84     .08       0  448.58     .12       0  541.55     .06       0
  564.55     .12       0  711.86     .06       0   751.8     .12       0
  811.49    .016       0  892.49     .08       0  899.15    .016       0
  939.18     .06       0 1321.82    .016       0 1361.42     .06       0
  1394.4    .045       0  1410.2     .06       0
#XS Ineff= 2 , 0
                          1574.9         1933.05
Permanent Ineff=
       F       F
Bank Sta=1394.4,1410.2
XS Rating Curve= 0 ,0
Exp/Cntr=0.3,0.1

Type RM Length L Ch R = 1 ,61111.9 ,480.6,460.5,441.6
XS GIS Cut Line= 4
      2066328.04      172565.153     2066295.779       172772.61
     2066711.807      173941.371     2066581.108      174114.402
#Sta/Elev= 30
       0 2152.12    78.7 2181.44   150.9  2197.1   167.3  2198.4   180.4 2196.44
   200.1 2188.16   239.4 2166.83   275.4 2151.54   350.7 2111.24   435.8 2074.32
   455.4 2062.76   471.8 2059.82   589.7  1981.7   628.9 1958.68  659.69 1943.67
   694.4  1935.6   733.7 1929.36   759.9 1919.43   769.7 1917.68   779.5 1919.54
  796.081921.718   831.9 1920.85   923.5 1922.28  1057.8 1922.02  1280.3 1924.38
  1362.2 1927.62  1547.6 1928.79  1628.6 1933.45  1654.4 1936.55  1667.4    1940
#Mann= 5 ,-1 , 0
       0     .12       0  659.69     .06       0   759.9    .045       0
   779.5     .08       0  796.08     .06       0
Bank Sta=759.9,779.5
XS Rating Curve= 0 ,0
Exp/Cntr=0.3,0.1

Type RM Length L Ch R = 1 ,60651.4 ,598.8,607.5,609.4
XS GIS Cut Line= 4
     2065929.757      173186.808     2066099.503      173519.655
     2066134.225      173521.825      2066527.02      174133.804
#Sta/Elev= 30
       0    2060    52.4 2033.12    98.3 2006.97   163.9 1967.16   173.7 1963.14
   190.1 1949.07   199.9 1943.78   219.6 1927.92   229.4 1922.19   245.8 1919.91
   283.21920.828   295.91920.629   324.5 1919.36   367.1 1920.55     380 1919.58
   383.6 1917.55   386.3 1916.31   392.6 1915.86   402.1 1917.01  406.971917.922
   421.5 1919.46   444.4 1919.01   493.6 1921.53   601.7 1922.38   765.5 1921.44
   994.8 1922.37  1027.5 1923.93  1073.4 1928.11 1114.211934.906  1135.6 1942.87
#Mann= 7 ,-1 , 0
       0     .12       0   283.2     .06       0   295.9     .12       0
   383.6    .045       0   402.1     .12       0  406.97     .06       0
 1114.21    .016       0
Bank Sta=383.6,402.1
XS Rating Curve= 0 ,0
Exp/Cntr=0.3,0.1

Type RM Length L Ch R = 1 ,60043.9 ,593,598.9,600.5
XS GIS Cut Line= 3
     2065416.739      173243.976      2065438.44      173539.114
     2066374.069      174254.479
#Sta/Elev= 30
       0    1990      78 1951.22   107.3 1940.09   133.3 1934.08   149.6 1931.39
  168.511929.307   211.4 1926.21   240.6  1922.3   295.9 1920.34   374.7 1922.13
   427.2 1920.22   502.6 1920.65   587.9  1919.2   640.4 1919.71     729 1918.31
   797.9 1918.42   843.8 1917.37  1037.4  1917.8  1109.6 1916.92 1125.731914.365
  1135.8 1913.73  1143.6 1914.54 1148.071915.728  1155.5 1917.44  1171.9 1918.85
    1290 1919.78 1372.381926.543  1434.3 1932.66    1454 1935.85  1473.7 1940.01
#Mann= 6 ,-1 , 0
       0     .12       0  168.51     .06       0 1125.73    .045       0
  1143.6     .12       0 1148.07     .06       0 1372.38     .08       0
Bank Sta=1125.73,1143.6
XS Rating Curve= 0 ,0
Exp/Cntr=0.3,0.1