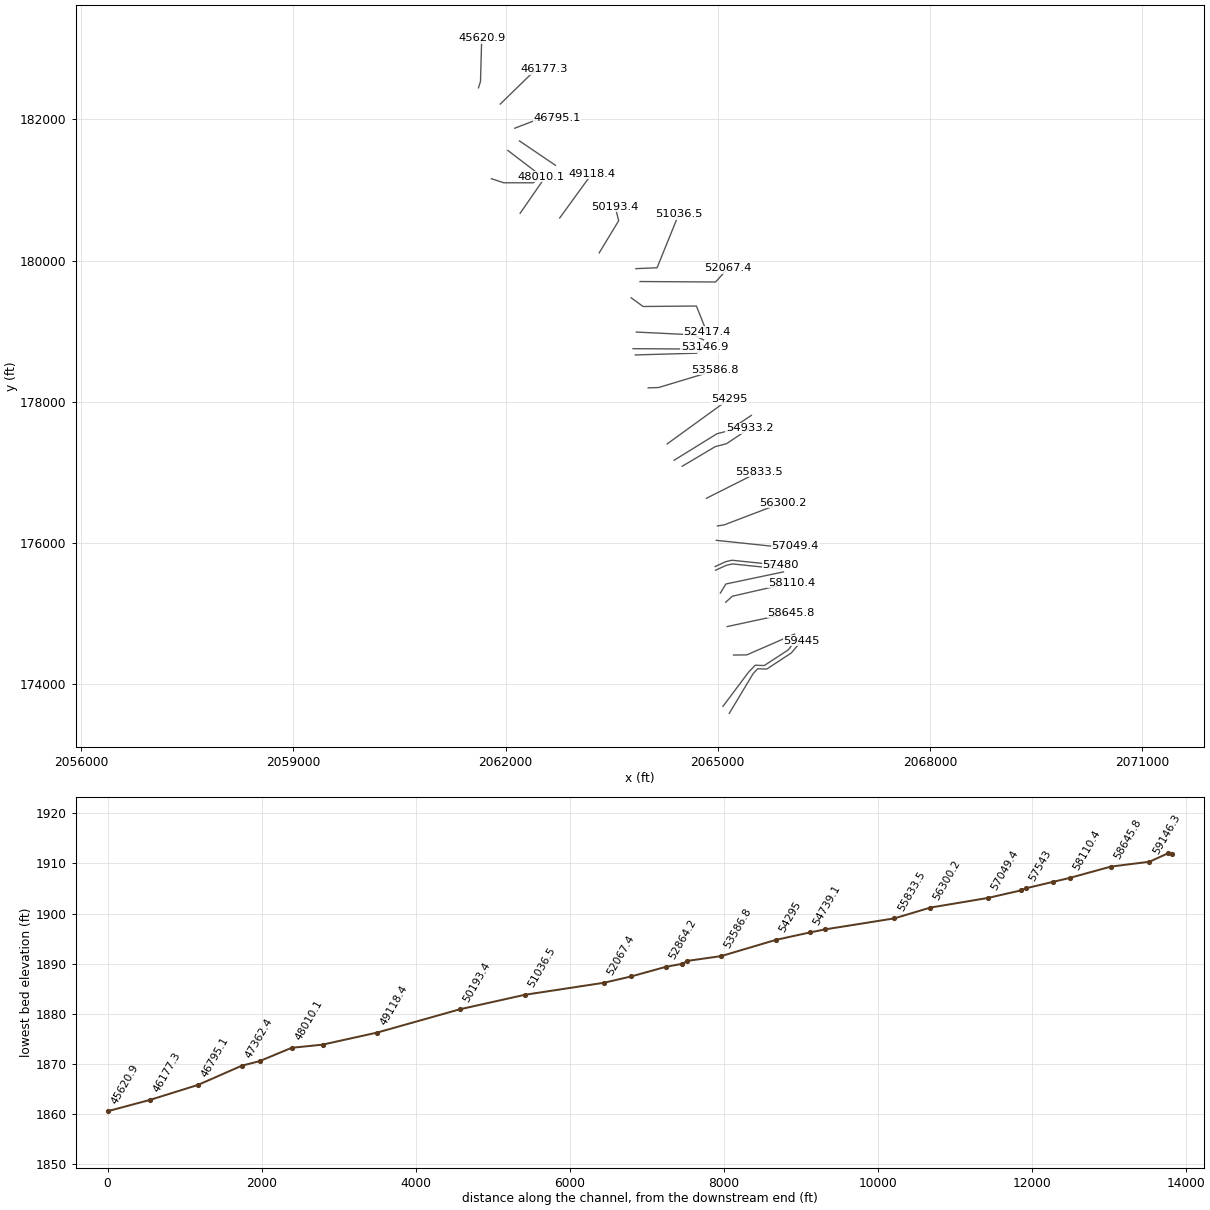
HEC-RAS study HNSCK.prj: HNSCK

--- HNSCK.g01 (geometry) --- (continued)

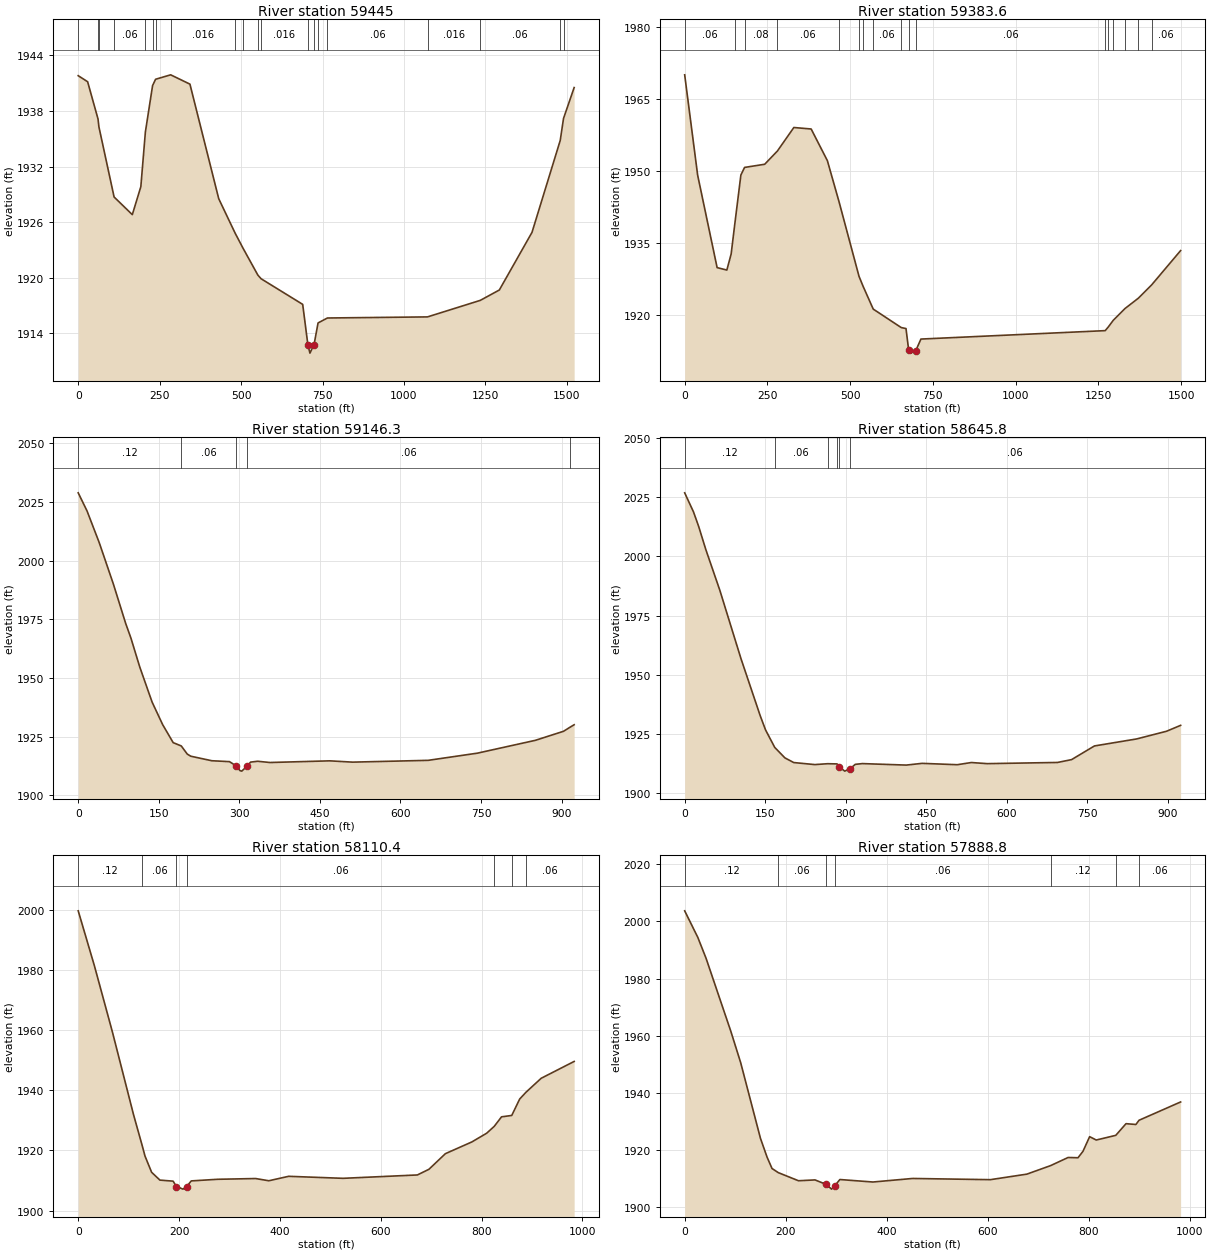
Type RM Length L Ch R = 1 ,59445   ,61.2,61.4,65.3
XS GIS Cut Line= 6
     2065162.005      173583.992     2065500.544      174148.995
     2065563.478       174216.27     2065691.516      174211.929
     2066038.799      174439.702     2066184.138      174613.405
#Sta/Elev= 30
       0  1941.8    28.9 1941.15   60.89 1937.12   63.57 1936.28  110.211928.711
   166.1 1926.81   192.3 1929.83  206.211935.722  228.321940.732  237.531941.415
  283.841941.894     343 1940.89   431.4 1928.53  481.741924.815  505.891923.198
  551.521920.291   561.41919.896   689.2 1917.13   705.1 1912.78   711.4 1911.87
   724.1  1912.8  736.391915.126  765.06 1915.66 1072.381915.778 1234.351917.561
  1292.9 1918.68  1393.2  1924.9 1479.831934.812 1490.011937.193  1522.6 1940.52
#Mann= 20 ,-1 , 0
       0     .08       0   60.89     .06       0   63.57     .08       0
  110.21     .06       0  206.21     .12       0  228.32    .016       0
  237.53     .06       0  283.84    .016       0  481.74     .06       0
  505.89    .016       0  551.52     .08       0   561.4    .016       0
   705.1    .045       0   724.1     .12       0  736.39    .016       0
  765.06     .06       0 1072.38    .016       0 1234.35     .06       0
 1479.83     .08       0 1490.01    .016       0
Bank Sta=705.1,724.1
XS Rating Curve= 0 ,0
Exp/Cntr=0.3,0.1

Type RM Length L Ch R = 1 ,59383.6 ,245.5,237.3,223.8
XS GIS Cut Line= 6
     2065073.698      173684.286     2065433.143      174165.829
     2065528.756      174266.183     2065656.794      174261.843
     2065995.336      174483.197     2066132.055      174663.318
#Sta/Elev= 30
       0    1970    39.2 1949.09      98 1929.82   127.4 1929.31   140.4 1932.66
  150.761938.542   169.8 1949.12  180.951950.702   241.7 1951.36  280.111954.121
   329.8 1959.02   382.1 1958.71   431.1 1952.11  466.241943.571  526.591928.022
  538.381926.027  569.611921.177  654.11 1917.33   668.6 1917.12   676.8 1912.58
   681.5    1912   697.6 1912.43   713.7 1914.93 1270.411916.687 1279.731917.451
 1294.691918.833    13301921.283 1370.611923.453  1410.81926.232  1498.2 1933.37
#Mann= 17 ,-1 , 0
       0     .06       0  150.76     .12       0  180.95     .08       0
  280.11     .06       0  466.24     .12       0  526.59     .08       0
  538.38     .12       0  569.61     .06       0  654.11     .12       0
   676.8    .045       0   697.6     .06       0 1270.41    .016       0
 1279.73     .06       0 1294.69     .08       0    1330     .06       0
 1370.61    .016       0  1410.8     .06       0
Bank Sta=676.8,697.6
XS Rating Curve= 0 ,0
Exp/Cntr=0.3,0.1

Type RM Length L Ch R = 1 ,59146.3 ,502.9,500.5,492.6
XS GIS Cut Line= 3
     2065222.766      174410.497     2065409.398      174412.667
     2066084.312      174707.806
#Sta/Elev= 30
       0 2028.84    16.4 2021.14    39.3 2007.53    65.5 1989.98    88.4 1973.21
    98.2 1966.95   114.6 1954.67   137.5 1939.78   157.2 1930.15   176.8 1922.47
  191.911921.055     203  1917.6   209.6 1916.69   248.8 1914.76   281.6 1914.38
   293.1 1912.71   301.2 1910.56   304.5 1910.34   314.3 1912.44   320.9 1914.18
     334 1914.54   356.9 1914.01   468.2 1914.72   510.8 1914.17   651.5 1914.93
   743.2 1917.99   851.2 1923.46   903.6 1927.31  915.191928.974   923.3 1930.09
#Mann= 5 ,-1 , 0
       0     .12       0  191.91     .06       0   293.1    .045       0
   314.3     .06       0  915.19     .08       0
Bank Sta=293.1,314.3
XS Rating Curve= 0 ,0
Exp/Cntr=0.3,0.1

Type RM Length L Ch R = 1 ,58645.8 ,527.2,535.3,528.5
XS GIS Cut Line= 2
     2065133.791      174814.143     2066036.569      175009.455
#Sta/Elev= 30
       0 2026.88    16.4 2018.84    26.2 2012.59    39.3 2002.98    65.5 1985.72
   104.8 1956.91   140.8 1932.69   150.7 1926.74  167.761919.374   186.7 1914.96
   203.1 1912.99   242.4 1912.13  266.111912.497  283.931912.417   288.2 1911.12
   298.1 1909.37   307.9 1910.35   317.7 1912.23   330.8 1912.55   412.7 1911.92
   442.2 1912.65   507.7 1912.08   533.9    1913   563.4 1912.53   694.4 1913.03
   720.6 1914.23   763.2    1920   841.8 1922.96   897.5 1926.21   923.7  1928.7
#Mann= 6 ,-1 , 0
       0     .12       0  167.76     .06       0  266.11     .12       0
  283.93     .06       0   288.2    .045       0   307.9     .06       0
Bank Sta=288.2,307.9
XS Rating Curve= 0 ,0
Exp/Cntr=0.3,0.1

Type RM Length L Ch R = 1 ,58110.4 ,218.4,221.7,224.6
XS GIS Cut Line= 3
     2065112.089      175159.195     2065205.405       175243.83
     2066040.909      175436.973
#Sta/Elev= 30
       0 1999.61    32.3 1981.24    67.8 1959.36   109.8 1931.81  127.141921.428
   132.5 1918.08   145.6  1912.7     162 1910.11   188.2 1909.76   194.7 1907.98
   207.8 1907.11   214.9 1907.94   224.2 1909.84   276.5 1910.38   351.8 1910.63
     378 1909.89   417.3 1911.37   525.3  1910.7   672.6 1911.82   695.5  1913.7
   728.2  1918.9   780.6 1922.79     810 1925.69  825.021927.972   839.5 1931.14
  859.751931.596   875.5 1937.06  888.071939.327   918.1 1943.95   983.5 1949.55
#Mann= 7 ,-1 , 0
       0     .12       0  127.14     .06       0   194.7    .045       0
   214.9     .06       0  825.02    .016       0  859.75     .12       0
  888.07     .06       0
Bank Sta=194.7,214.9
XS Rating Curve= 0 ,0
Exp/Cntr=0.3,0.1

Type RM Length L Ch R = 1 ,57888.8 ,347.4,345.8,298.8
XS GIS Cut Line= 3
     2065036.135      175289.403      2065114.26      175417.442
     2065928.062      175588.883
#Sta/Elev= 30
       0 2003.68    26.1 1994.35    42.4 1987.04    91.3 1961.56   110.9 1950.52
     150 1924.08   163.1 1917.49   172.9 1913.52  185.421912.062   225.3 1909.23
     258 1909.52   280.1 1907.96   290.8  1906.3   297.3 1907.51   307.2 1909.66
   372.6 1908.79   451.2 1910.03   605.1 1909.61   677.2 1911.54  724.421914.532
     759 1917.37   778.6 1917.28   788.5 1919.55   801.6 1924.66   814.7 1923.48
  853.361925.121   873.6  1929.2   893.2 1928.92  899.371930.393   981.7  1936.8
#Mann= 7 ,-1 , 0
       0     .12       0  185.42     .06       0   280.1    .045       0
   297.3     .06       0  724.42     .12       0  853.36    .016       0
  899.37     .06       0
Bank Sta=280.1,297.3
XS Rating Curve= 0 ,0
Exp/Cntr=0.3,0.1

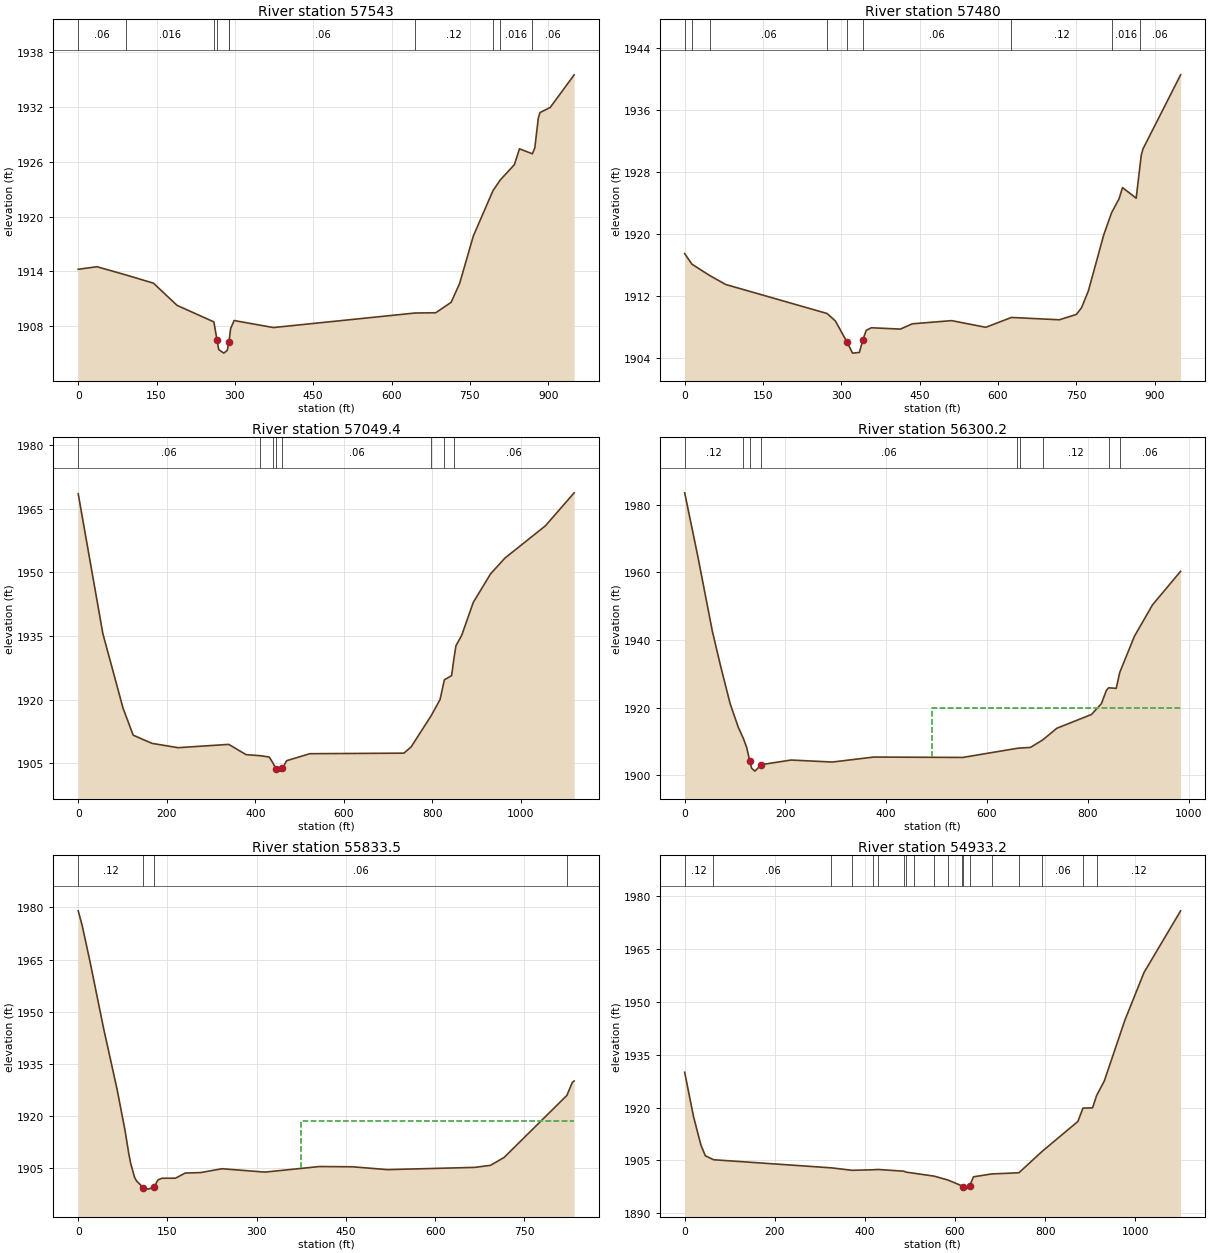
Type RM Length L Ch R = 1 ,57543   ,65.1,63,68.4
XS GIS Cut Line= 4
      2064968.86      175612.754      2065120.77      175682.199
     2065207.575       175701.73      2065897.68      175630.115
#Sta/Elev= 30
       0 1914.23      36 1914.51   90.721913.622   144.1 1912.71   189.3 1910.28
  259.82 1908.47   265.8 1906.51   269.1 1905.44   278.9 1905.05   285.5 1905.36
   288.7  1906.3  289.521906.663     292 1907.76   298.6 1908.62   373.8 1907.85
  645.891909.445   684.7 1909.47   714.2 1910.61   730.6  1912.7   756.7 1917.87
  794.381922.843  808.431924.019   835.3 1925.68   845.1 1927.42  869.791926.876
   874.5 1927.53   881.1 1930.76   884.4 1931.39     904 1931.95   949.8 1935.52
#Mann= 10 ,-1 , 0
       0     .06       0   90.72    .016       0  259.82     .12       0
   265.8    .045       0   288.7     .12       0  289.52     .06       0
  645.89     .12       0  794.38     .06       0  808.43    .016       0
  869.79     .06       0
Bank Sta=265.8,288.7
XS Rating Curve= 0 ,0
Exp/Cntr=0.3,0.1

Type RM Length L Ch R = 1 ,57480   ,426.7,430.6,422.9
XS GIS Cut Line= 4
      2064962.35      175664.837      2065114.26      175734.282
     2065201.065      175753.813     2065891.169      175682.199
#Sta/Elev= 30
       0 1917.46   13.971916.092   48.861914.599    78.6 1913.48  272.821909.738
   288.7 1908.77   310.9 1906.06   321.5 1904.63   334.6 1904.72   341.1 1906.32
   347.6 1907.56   357.5  1907.9   413.1 1907.73     436 1908.41   511.3 1908.82
   576.7 1907.96  625.721909.229   717.5 1908.93   750.2 1909.62     760 1910.48
   773.1 1912.64   802.5 1919.86   817.51922.721     832 1924.54   838.5 1925.97
   864.7 1924.61  871.981928.778   874.5 1930.18   877.8 1930.97   949.8 1940.51
#Mann= 9 ,-1 , 0
       0     .08       0   13.97    .016       0   48.86     .06       0
  272.82     .12       0   310.9    .045       0   341.1     .06       0
  625.72     .12       0   817.5    .016       0  871.98     .06       0
Bank Sta=310.9,341.1
XS Rating Curve= 0 ,0
Exp/Cntr=0.3,0.1

Type RM Length L Ch R = 1 ,57049.4 ,736,749.2,758.2
XS GIS Cut Line= 3
     2064979.711      176035.931     2065821.725      175946.955
     2066095.162      175951.296
#Sta/Elev= 30
       0 1968.56    55.6 1935.59   101.3 1917.96   124.2  1911.6   166.7 1909.67
   225.6 1908.65     340 1909.43   379.2 1907.01  411.151906.758   431.5 1906.45
  440.86 1904.86   446.3 1903.68   454.4 1903.12   461.3  1903.8   470.8 1905.58
   523.1 1907.23   735.6 1907.36   751.9 1908.82   797.3 1916.21   817.3 1920.01
  827.011924.657   843.4 1925.65  848.43 1929.52   853.2  1932.7   866.2 1935.16
   892.3 1942.92   931.4 1949.66   963.9 1953.39  1055.1 1960.98  1120.2 1968.78
#Mann= 8 ,-1 , 0
       0     .06       0  411.15     .12       0  440.86     .06       0
   446.3    .045       0   461.3     .06       0   797.3     .08       0
  827.01    .016       0  848.43     .06       0
Bank Sta=446.3,461.3
XS Rating Curve= 0 ,0
Exp/Cntr=0.3,0.1

Type RM Length L Ch R = 1 ,56300.2 ,462.6,466.7,468.9
XS GIS Cut Line= 3
     2064994.902      176239.924     2065090.388      176255.115
     2065919.381      176571.955
#Sta/Elev= 30
       0 1983.53    25.8 1964.96    54.8 1942.67    70.9 1932.53    90.2 1921.16
   106.5 1914.12  116.061910.994   122.9 1908.27   129.4  1904.1   132.7 1902.08
   139.3 1901.19   152.4 1903.12   211.3 1904.47   293.2 1903.88     375 1905.35
   551.9 1905.24  658.831907.913  666.361908.028   686.2 1908.21  710.351910.401
   738.6 1913.88   807.3 1917.95     827 1921.15   836.8 1925.05  841.321925.843
   856.4 1925.68  863.451930.403   892.5 1941.09   928.5  1950.4   984.2 1960.32
#Mann= 9 ,-1 , 0
       0     .12       0  116.06     .06       0   129.4    .045       0
   152.4     .06       0  658.83     .12       0  666.36     .06       0
  710.35     .12       0  841.32    .016       0  863.45     .06       0
#XS Ineff= 2 , 0
                          490.11         1919.76
Permanent Ineff=
       F       F
Bank Sta=129.4,152.4
XS Rating Curve= 0 ,0
Exp/Cntr=0.3,0.1

Type RM Length L Ch R = 1 ,55833.5 ,899.9,900.3,894
XS GIS Cut Line= 2
     2064840.822      176632.719      2065585.18      177008.153
#Sta/Elev= 30
       0    1979     6.5 1974.91     9.8 1972.32    19.6  1964.6    42.5 1945.37
    65.4 1927.67    78.5 1916.09      85 1909.27    88.3 1906.37    94.8 1902.42
    98.1 1901.38   109.6 1899.44   117.7 1899.04   127.5 1899.65     134 1901.67
   140.6 1902.16   163.5 1902.18   179.8 1903.65     206  1903.8   241.9  1904.9
   313.9 1903.93   405.4 1905.53     461 1905.46   519.8 1904.64   666.9 1905.29
   693.1 1905.88     716 1908.15  821.491925.969   830.4 1929.64   833.7 1930.12
#Mann= 4 ,-1 , 0
       0     .12       0   109.6    .045       0   127.5     .06       0
  821.49    .016       0
#XS Ineff= 2 , 0
                          375.35         1918.57
Permanent Ineff=
       F       F
Bank Sta=109.6,127.5
XS Rating Curve= 0 ,0
Exp/Cntr=0.3,0.1

Type RM Length L Ch R = 1 ,54933.2 ,193.6,194.1,193.7
XS GIS Cut Line= 4
      2064497.94      177086.278      2064964.52      177364.056
      2065122.94      177405.289     2065450.631      177624.473
#Sta/Elev= 30
       0 1930.04    19.6 1917.47      36 1909.37    45.8 1906.34   63.911905.192
  325.671902.886  371.591902.188  417.661902.333  429.341902.428  486.411901.931
  490.961901.684  509.611901.344  554.311900.517  584.321899.424  614.851897.806
   617.3 1897.41   624.9 1896.84   632.3 1897.74   641.2 1900.34  681.421901.152
   741.91901.488  793.641907.577   872.9 1916.07  884.051919.839   905.4 1919.93
  914.551923.462   931.5 1927.57   977.1  1944.8  1019.5 1958.34  1100.9  1975.9
#Mann= 19 ,-1 , 0
       0     .12       0   63.91     .06       0  325.67    .016       0
  371.59     .12       0  417.66     .06       0  429.34     .12       0
  486.41    .016       0  490.96     .06       0  509.61    .016       0
  554.31     .06       0  584.32     .12       0  614.85     .06       0
   617.3    .045       0   632.3     .06       0  681.42    .016       0
   741.9     .12       0  793.64     .06       0  884.05    .016       0
  914.55     .12       0
Bank Sta=617.3,632.3
XS Rating Curve= 0 ,0
Exp/Cntr=0.3,0.1

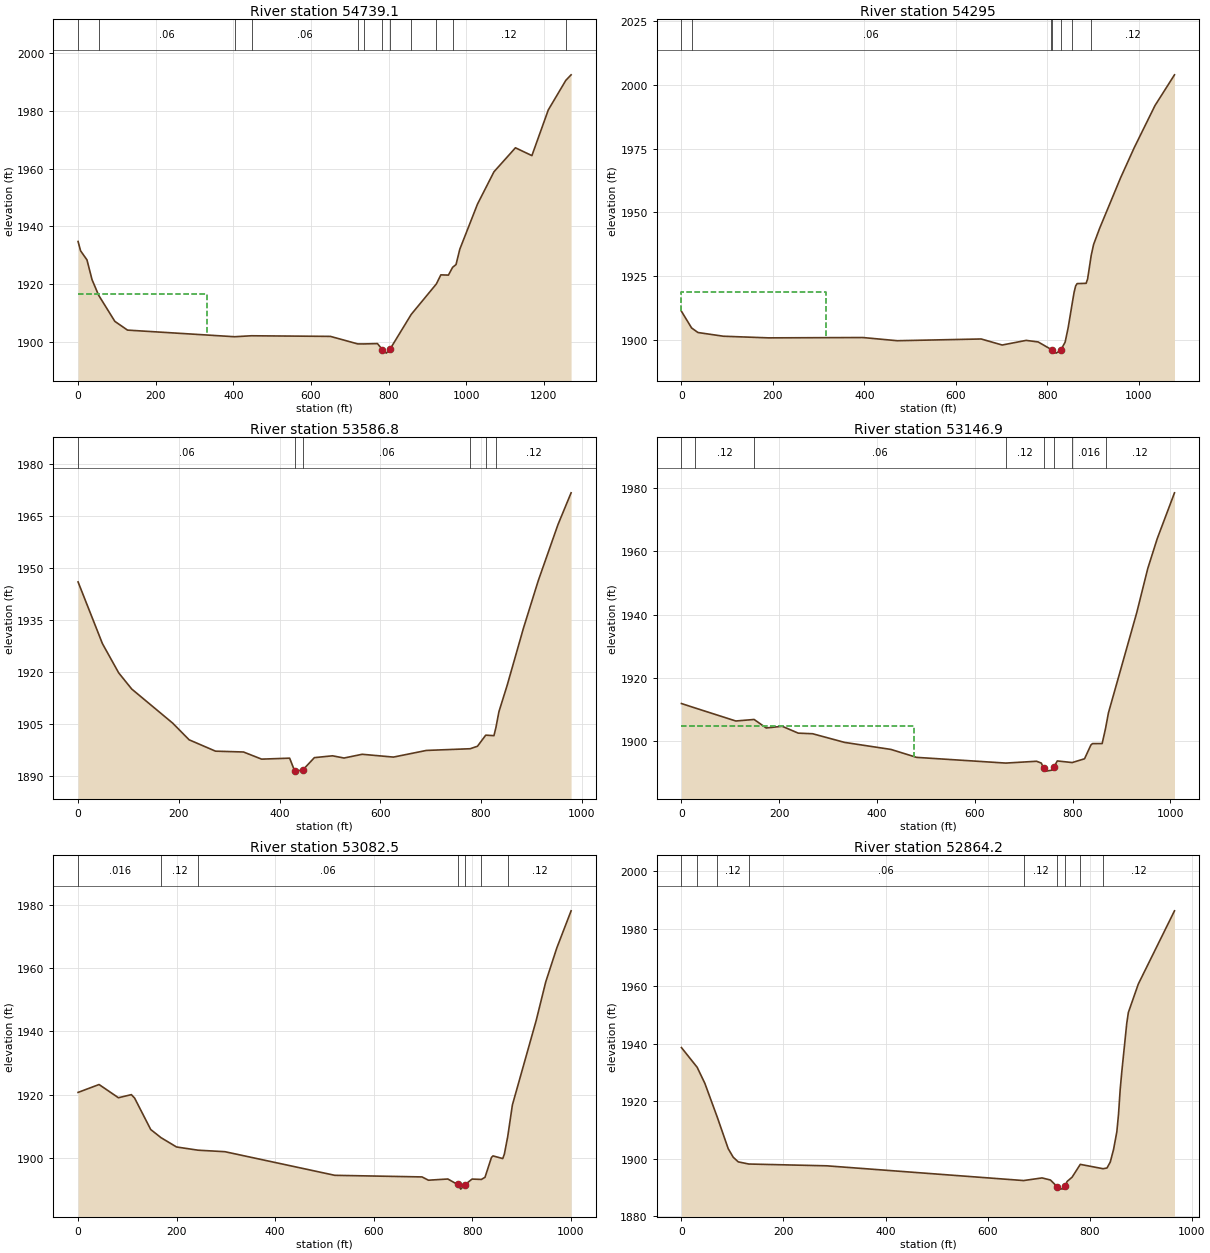
Type RM Length L Ch R = 1 ,54739.1 ,433.4,444.2,451.4
XS GIS Cut Line= 4
     2064382.923      177170.914     2064988.391      177546.348
     2065146.812       177587.58     2065474.503      177806.765
#Sta/Elev= 30
       0  1934.8     6.5 1931.58    22.9 1928.46      36 1921.62   52.99 1916.24
    94.8 1907.21   127.4 1904.19  403.131901.906  446.911902.235   650.3 1902.02
  720.741899.421  736.281899.414   771.4 1899.53   784.1 1897.48   794.3 1896.24
   804.1 1897.67  858.471909.616  923.221920.134   934.8 1923.27   954.3 1923.19
   965.11925.872   973.9 1926.83   983.6 1932.12  1029.2 1947.71  1071.6 1958.86
    1127 1967.16  1169.4 1964.46  1211.7 1980.26  1256.81990.446  1270.4 1992.36
#Mann= 12 ,-1 , 0
       0     .12       0   52.99     .06       0  403.13     .12       0
  446.91     .06       0  720.74     .12       0  736.28     .06       0
   784.1    .045       0   804.1     .06       0  858.47     .12       0
  923.22    .016       0   965.1     .12       0  1256.8     .06       0
#XS Ineff= 2 , 0
           331.6 1916.71
Permanent Ineff=
       F       F
Bank Sta=784.1,804.1
XS Rating Curve= 0 ,0
Exp/Cntr=0.3,0.1

Type RM Length L Ch R = 1 ,54295   ,715,708.1,700.3
XS GIS Cut Line= 2
     2064285.266      177403.119     2065157.662      178036.799
#Sta/Elev= 30
       0 1911.17   22.151904.635      36 1902.84    91.8 1901.38   190.1 1900.74
   396.6 1900.87   471.9 1899.62   655.5  1900.3   701.4 1897.93   753.8 1899.75
     780 1899.14  807.281896.327   809.5 1895.97   819.3 1894.75   829.2 1895.85
     839 1899.04   845.6 1904.66     854 1913.73   858.7 1918.66     862 1921.09
   865.2 1922.03   884.9 1922.14   888.2 1923.85  896.071933.113   901.3 1937.38
   914.4 1943.69   960.3 1963.54   989.8 1975.24  1035.6 1991.92  1078.2 2003.96
#Mann= 7 ,-1 , 0
       0     .12       0   22.15     .06       0  807.28     .12       0
   809.5    .045       0   829.2     .12       0     854    .016       0
  896.07     .12       0
#XS Ineff= 2 , 0
          315.43 1918.83
Permanent Ineff=
       F       F
Bank Sta=809.5,829.2
XS Rating Curve= 0 ,0
Exp/Cntr=0.3,0.1

Type RM Length L Ch R = 1 ,53586.8 ,445.3,440,433.1
XS GIS Cut Line= 4
     2064016.495      178196.579     2064164.932      178201.788
     2064828.995      178402.308     2064955.839      178453.466
#Sta/Elev= 30
       0 1946.11    48.4  1928.3    80.7 1919.86   106.6  1915.2   187.8 1905.38
   220.5 1900.56   272.9 1897.28   328.5 1897.04   364.5 1894.98   420.1 1895.26
   429.9 1891.65   433.2 1891.52   446.6  1891.9   469.2 1895.41   505.2 1895.94
   528.1  1895.3   564.1 1896.38   626.2 1895.57   691.7 1897.49  778.631897.981
   793.1  1898.7  809.481901.897   825.8 1901.75  829.711904.094   835.7 1908.67
     852 1916.25   884.5 1932.82   913.8 1946.47   952.9 1962.63     979 1971.81
#Mann= 6 ,-1 , 0
       0     .06       0   429.9    .045       0   446.6     .06       0
  778.63     .12       0  809.48    .016       0  829.71     .12       0
Bank Sta=429.9,446.6
XS Rating Curve= 0 ,0
Exp/Cntr=0.3,0.1

Type RM Length L Ch R = 1 ,53146.9 ,65.1,64.4,63.5
XS GIS Cut Line= 3
     2063833.012      178663.193     2064699.763      178687.841
      2064814.78      178770.306
#Sta/Elev= 30
       0 1911.93   27.291910.559   111.2 1906.41  148.621906.891   173.4  1904.2
   206.1 1904.74   238.9 1902.57   268.3 1902.38   333.8 1899.64   428.6 1897.42
     481 1894.91  663.471893.104   726.4 1893.68   736.2  1893.1     741 1891.44
     746 1890.56   759.1  1890.9   762.4 1892.02   768.9 1893.78  799.371893.271
   824.6 1894.46   837.6 1898.83   840.9 1899.26   860.6 1899.27  867.53 1904.04
   873.5 1908.99   931.4 1940.68     954 1954.66   973.2 1964.02  1008.6 1978.55
#Mann= 8 ,-1 , 0
       0     .06       0   27.29     .12       0  148.62     .06       0
  663.47     .12       0     741    .045       0   762.4     .06       0
  799.37    .016       0  867.53     .12       0
#XS Ineff= 2 , 0
           476.2 1904.88
Permanent Ineff=
       F       F
Bank Sta=741,762.4
XS Rating Curve= 0 ,0
Exp/Cntr=0.3,0.1

Type RM Length L Ch R = 1 ,53082.5 ,218.2,218.3,216.7
XS GIS Cut Line= 3
     2063802.236      178752.103     2064686.742      178746.435
     2064786.569      178805.028
#Sta/Elev= 30
       0 1920.67    42.6 1923.17    81.9 1918.98   108.1 1919.96   114.7 1918.88
   147.4  1908.9  168.33 1906.31   199.8 1903.36  243.391902.342   298.1 1901.86
   520.9 1894.37   697.8 1893.86   710.9 1892.82   750.2  1893.2   770.1 1891.46
   776.4 1889.99   785.1 1891.41   799.4 1893.18   818.21893.065   825.6 1893.73
   838.7 1900.04   841.9 1900.53   861.6 1899.68   864.9 1901.09  871.731906.678
   881.2  1916.7   929.5  1943.5   948.8  1955.7   971.3  1966.5  1000.3 1978.27
#Mann= 7 ,-1 , 0
       0    .016       0  168.33     .12       0  243.39     .06       0
   770.1    .045       0   785.1     .06       0   818.2    .016       0
  871.73     .12       0
Bank Sta=770.1,785.1
XS Rating Curve= 0 ,0
Exp/Cntr=0.3,0.1

Type RM Length L Ch R = 1 ,52864.2 ,443.8,446.8,448.9
XS GIS Cut Line= 3
     2063849.069       178987.32      2064656.36      178948.258
     2064797.419      178876.643
#Sta/Elev= 30
       0 1938.66   30.771931.805    45.8 1926.23   70.051914.498    91.6 1903.47
   101.4 1900.48   111.3 1898.86  131.971898.104   284.7 1897.48  670.591892.346
   706.8 1893.26   723.2 1892.54     737 1890.11   746.1 1889.36     752 1890.31
   755.9 1892.03   765.7 1893.52  781.751897.986  826.551896.463   834.1 1896.73
   840.5 1898.78     847 1903.21   853.4 1909.34   856.7 1915.46   859.9 1923.96
   863.1 1930.21   872.8 1947.09     876  1950.9   895.4 1960.77   966.4  1986.3
#Mann= 9 ,-1 , 0
       0     .12       0   30.77     .06       0   70.05     .12       0
  131.97     .06       0  670.59     .12       0     737    .045       0
     752     .12       0  781.75    .016       0  826.55     .12       0
Bank Sta=737,752
XS Rating Curve= 0 ,0
Exp/Cntr=0.3,0.1

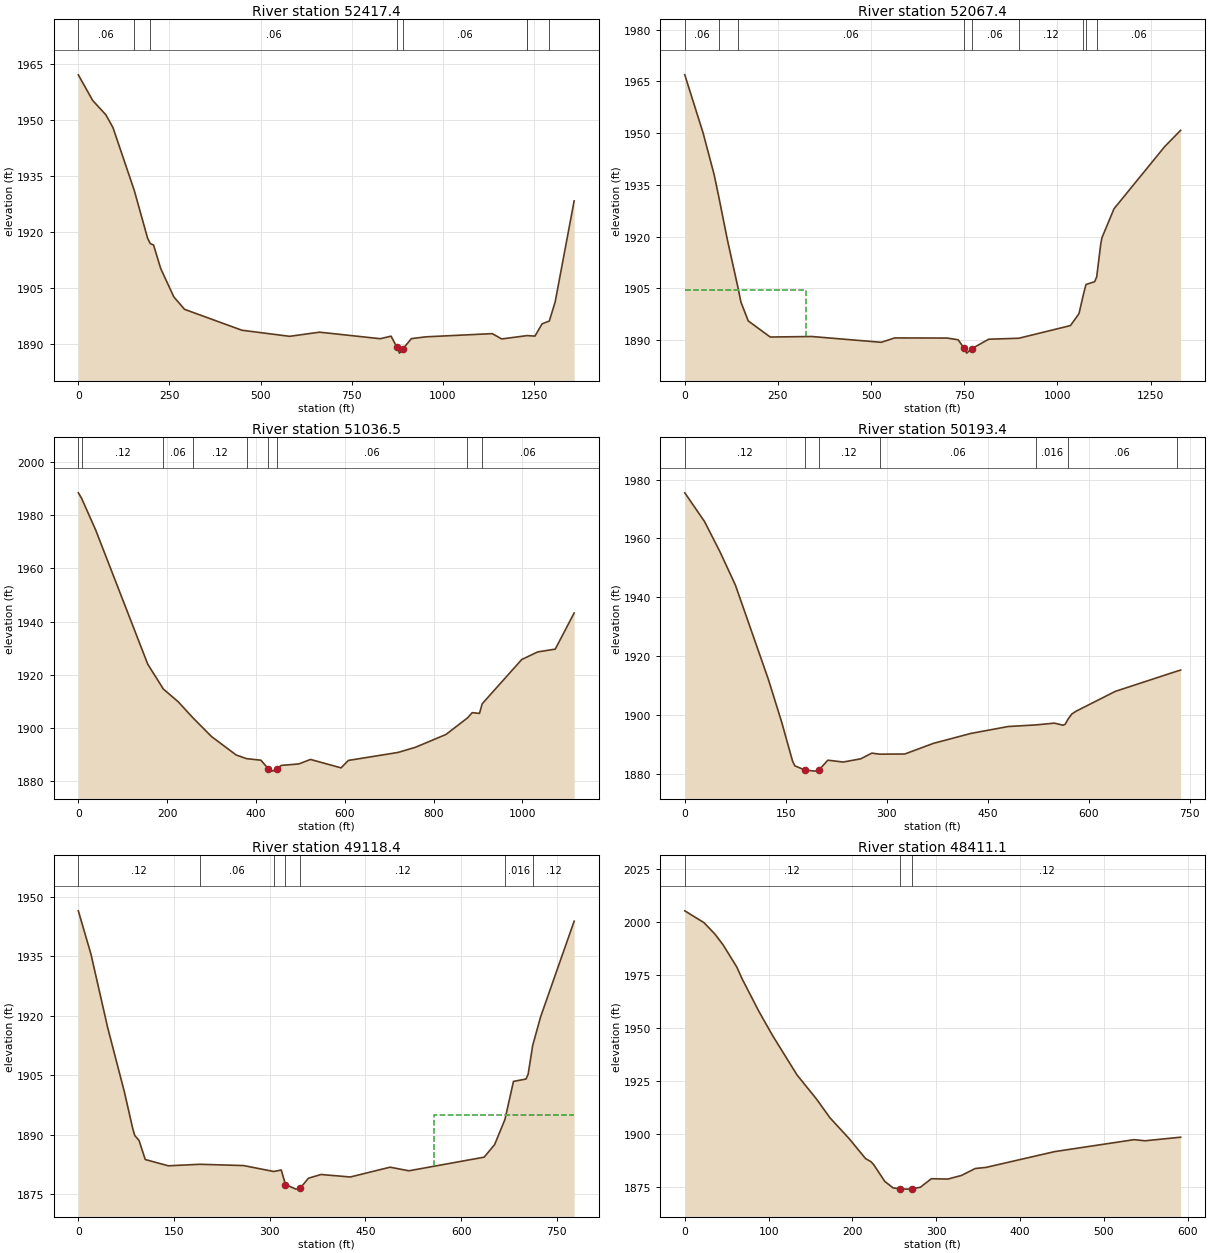
Type RM Length L Ch R = 1 ,52417.4 ,349,350,351.4
XS GIS Cut Line= 4
     2063775.284      179473.431     2063944.555      179349.733
     2064697.593      179356.244     2064845.162       178987.32
#Sta/Elev= 30
       0 1961.97    39.3 1955.12    75.3  1951.3      95 1947.86  153.421931.031
     190 1918.23  197.341916.788   206.4 1916.41     226  1910.1     262 1902.51
   291.5 1899.18   448.7 1893.59   579.6 1891.96   661.5 1893.07   828.5 1891.32
   857.9    1892   874.3 1888.97   880.9 1887.46   890.3 1888.61   913.6 1891.34
   952.9 1891.82  1135.3 1892.68  1161.4 1891.26 1230.321892.142 1232.091892.147
  1252.6 1892.02  1272.1  1895.3 1291.961896.061    1308 1901.17  1360.1 1928.22
#Mann= 8 ,-1 , 0
       0     .06       0  153.42     .12       0  197.34     .06       0
   874.3    .045       0   890.3     .06       0 1230.32     .12       0
 1232.09    .016       0 1291.96     .12       0
Bank Sta=874.3,890.3
XS Rating Curve= 0 ,0
Exp/Cntr=0.3,0.1

Type RM Length L Ch R = 1 ,52067.4 ,1002,1030.9,1055
XS GIS Cut Line= 4
     2063901.152      179703.466      2064968.86      179696.955
     2065090.388      179831.504     2065142.471      179894.438
#Sta/Elev= 30
       0 1966.93    49.1 1950.08    78.6 1938.04   90.931931.707   114.6 1918.94
  142.791905.201   150.7    1901   170.3 1895.55   229.3 1890.88   340.6 1891.03
   527.3 1889.35   563.3 1890.62   704.2 1890.58   733.6 1890.09  748.34 1887.81
   756.6 1886.21   769.7 1887.46   815.5 1890.24  896.471890.527    1035  1894.2
  1057.9 1897.66 1069.911903.265 1076.641906.108  1100.1 1906.94 1105.461908.336
  1116.3 1917.82  1119.5 1919.67  1151.9 1928.08  1288.2 1946.15  1330.7 1950.83
#Mann= 9 ,-1 , 0
       0     .06       0   90.93     .12       0  142.79     .06       0
  748.34    .045       0   769.7     .06       0  896.47     .12       0
 1069.91     .08       0 1076.64    .016       0 1105.46     .06       0
#XS Ineff= 2 , 0
          325.27 1904.64
Permanent Ineff=
       F       F
Bank Sta=748.34,769.7
XS Rating Curve= 0 ,0
Exp/Cntr=0.3,0.1

Type RM Length L Ch R = 1 ,51036.5 ,846.1,843.1,838.6
XS GIS Cut Line= 3
     2063842.558      179885.758     2064142.037      179898.778
     2064448.027      180656.157
#Sta/Elev= 30
       0 1988.42    7.181986.442    39.1 1974.43   156.4 1923.98  191.521914.651
   224.8  1909.9  257.95 1903.87   299.8 1896.82   355.5 1889.86  378.751888.499
   411.3  1887.9   427.7 1884.71   437.5  1883.8   447.4 1884.74   457.2 1885.96
   496.6  1886.5   522.8 1888.19   591.7 1885.03   608.1 1887.82   719.7 1890.82
     759 1892.75   827.9 1897.58  876.311903.793     887 1905.78   903.4 1905.51
  909.541909.128   998.5 1925.75  1034.6 1928.62    1074 1929.66  1116.6 1943.25
#Mann= 9 ,-1 , 0
       0     .06       0    7.18     .12       0  191.52     .06       0
  257.95     .12       0  378.75     .06       0   427.7    .045       0
   447.4     .06       0  876.31    .016       0  909.54     .06       0
Bank Sta=427.7,447.4
XS Rating Curve= 0 ,0
Exp/Cntr=0.3,0.1

Type RM Length L Ch R = 1 ,50193.4 ,1077,1075.1,1072.2
XS GIS Cut Line= 3
     2063323.895      180109.282     2063599.503      180565.011
     2063549.589      180762.494
#Sta/Elev= 30
       0 1975.51    29.4 1965.72    52.3 1955.44    75.2 1944.12   124.2 1912.04
   143.8 1897.63   160.1 1884.27   163.4 1882.71   178.3  1881.3   192.8 1880.91
   199.3  1881.3   212.4 1884.63   235.2    1884   261.4  1885.1   277.7 1887.03
   289.41886.679   326.7 1886.73   369.2 1890.35   424.8 1893.72   480.3 1896.08
  521.031896.614   548.8 1897.22   561.7 1896.52   564.9 1896.84   568.7 1898.44
   574.6  1900.3   581.1 1901.28   639.3 1908.02   730.21914.839   736.3 1915.25
#Mann= 7 ,-1 , 0
       0     .12       0   178.3    .045       0   199.3     .12       0
   289.4     .06       0  521.03    .016       0   568.7     .06       0
   730.2     .12       0
Bank Sta=178.3,199.3
XS Rating Curve= 0 ,0
Exp/Cntr=0.3,0.1

Type RM Length L Ch R = 1 ,49118.4 ,703.3,707.3,705.7
XS GIS Cut Line= 2
     2062766.169      180604.074     2063221.898      181233.414
#Sta/Elev= 30
       0 1946.42    19.7 1935.56    45.9 1917.04    72.1 1900.81    85.2 1891.57
    88.5 1889.76    95.1 1888.55   104.9 1883.72     141 1882.14  190.311882.524
     259  1882.2  306.191880.706     318 1881.08   324.6 1877.42     341 1876.26
   347.5 1876.48   360.6 1879.01   380.3 1879.95   426.2 1879.32   488.5 1881.79
     518 1880.88     636 1884.32   652.4  1887.5   668.61893.847   681.9 1903.42
   701.6 1904.02   704.9 1905.25  712.091912.529   724.6 1919.78     777 1943.81
#Mann= 7 ,-1 , 0
       0     .12       0  190.31     .06       0  306.19     .12       0
   324.6    .045       0   347.5     .12       0   668.6    .016       0
  712.09     .12       0
#XS Ineff= 2 , 0
                          558.06         1895.05
Permanent Ineff=
       F       F
Bank Sta=324.6,347.5
XS Rating Curve= 0 ,0
Exp/Cntr=0.3,0.1

Type RM Length L Ch R = 1 ,48411.1 ,422.7,401,379.1
XS GIS Cut Line= 2
     2062206.599      180670.538     2062542.536      181157.517
#Sta/Elev= 30
       0 2005.28    22.9 1999.69      36 1994.28    45.8 1989.14    62.1 1978.72
    68.6 1973.01    88.2 1957.95   104.6 1946.48     134 1927.73   156.9 1916.53
   173.2 1907.56   196.1  1897.7   215.7 1888.28   222.3 1886.77   225.5 1885.37
   238.6 1877.51   248.4 1874.48   256.4 1873.98   264.8 1873.86   271.4 1873.98
   281.1 1874.77   294.2 1878.78   313.8 1878.61   330.1 1880.32   346.5 1883.59
   359.5 1884.13   441.3 1891.58     536 1897.22   549.1 1896.69   591.6 1898.38
#Mann= 3 ,-1 , 0
       0     .12       0   256.4    .045       0   271.4     .12       0
Bank Sta=256.4,271.4
XS Rating Curve= 0 ,0
Exp/Cntr=0.3,0.1

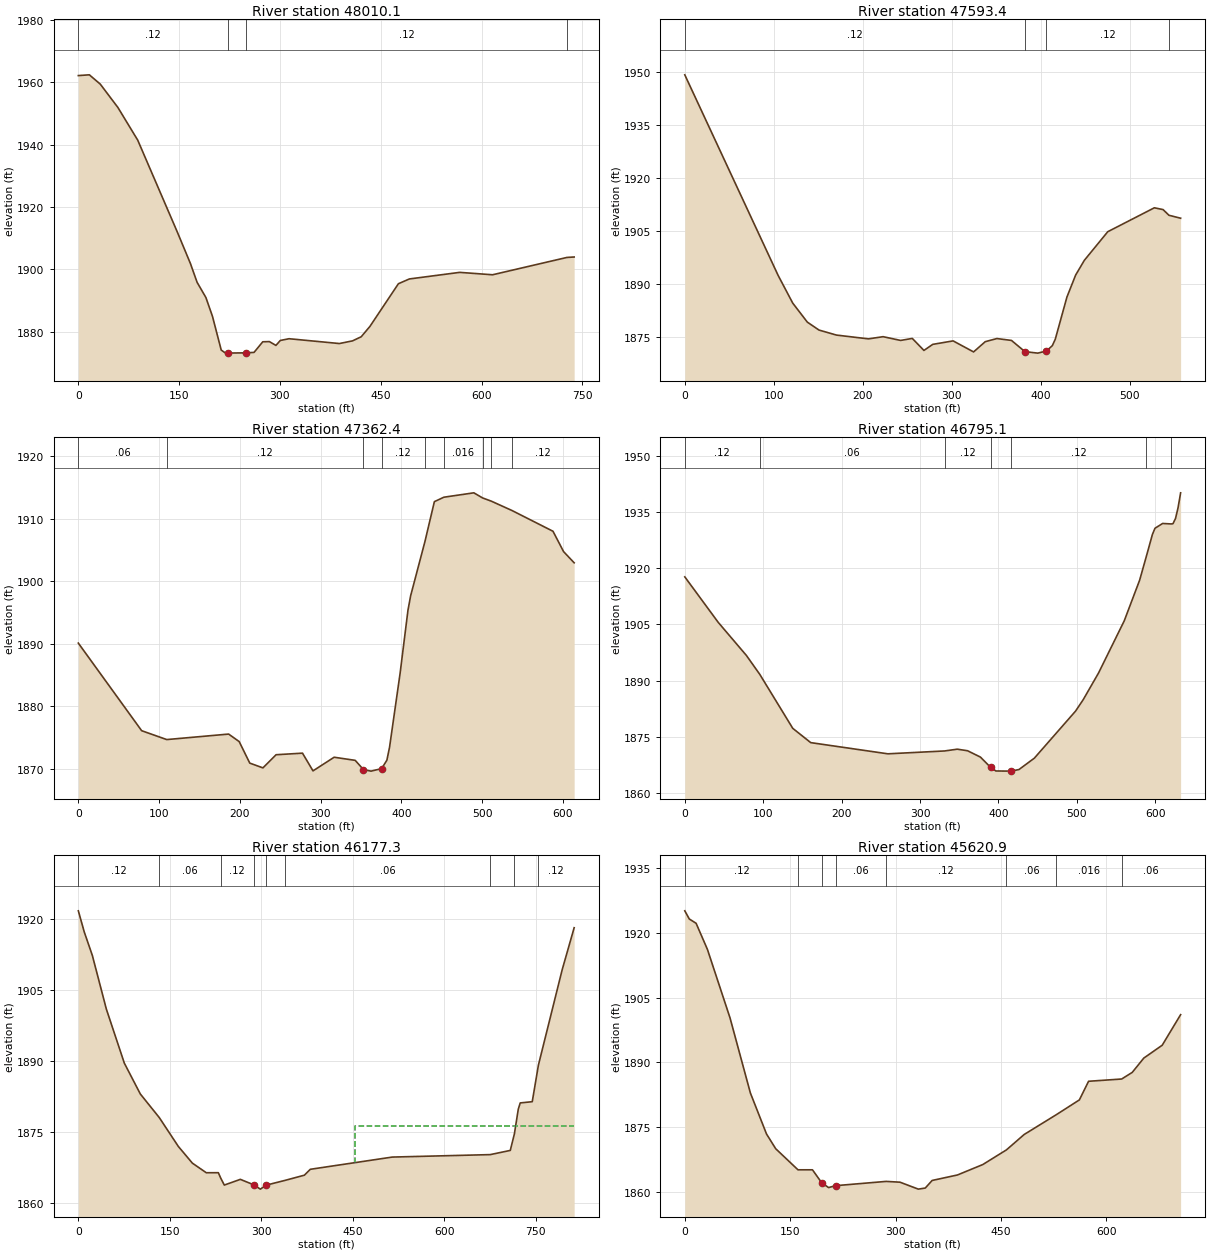
Type RM Length L Ch R = 1 ,48010.1 ,430.3,416.7,401.4
XS GIS Cut Line= 4
     2061800.895      181160.586     2061974.828      181102.829
     2062391.495      181102.829     2062498.812      181189.232
#Sta/Elev= 30
       0 1962.07    16.4 1962.31    32.7 1959.32    58.9 1951.85    88.4 1941.39
   147.3 1911.98   166.9 1901.84   176.7  1895.9   189.8 1891.03   199.6    1885
   212.6 1874.21   219.1 1873.23   222.3 1873.25   249.7 1873.32   261.4 1873.46
   274.4 1876.86   284.2 1876.92     294  1875.7   300.5 1877.28   313.5 1877.84
   388.4  1876.3   407.9 1877.15   420.9 1878.47   433.9  1881.8   476.2 1895.44
   492.5 1896.97   567.4 1899.08   616.3 1898.31  726.941903.857   737.7    1904
#Mann= 4 ,-1 , 0
       0     .12       0   222.3    .045       0   249.7     .12       0
  726.94     .06       0
Bank Sta=222.3,249.7
XS Rating Curve= 0 ,0
Exp/Cntr=0.3,0.1

Type RM Length L Ch R = 1 ,47593.4 ,229.8,231,231.7
XS GIS Cut Line= 2
     2062032.662      181561.105     2062475.371      181222.563
#Sta/Elev= 30
       0 1949.08   104.9  1892.5   121.3 1884.69   137.7 1879.32   150.8 1877.08
   170.5 1875.66   206.5 1874.59   222.9 1875.21   242.6 1874.15   255.7 1874.72
   268.8 1871.33   278.7 1873.04   301.6 1874.02   324.6 1870.91   337.7  1873.8
   350.8 1874.68   367.2 1874.15   382.3 1870.99   396.7 1870.57   406.5 1871.16
   413.1 1872.68   416.4 1874.48   429.5 1886.38   439.3 1892.59   449.1 1896.76
   475.4 1904.82   527.8 1911.57   537.6 1911.06   544.2 1909.46   557.3 1908.63
#Mann= 4 ,-1 , 0
       0     .12       0   382.3    .045       0   406.5     .12       0
   544.2     .06       0
Bank Sta=382.3,406.5
XS Rating Curve= 0 ,0
Exp/Cntr=0.3,0.1

Type RM Length L Ch R = 1 ,47362.4 ,544.3,567.3,588.6
XS GIS Cut Line= 2
     2062197.593      181695.653     2062705.405      181350.601
#Sta/Elev= 30
       0 1890.11    78.4 1876.12  109.49  1874.7   186.1 1875.58   199.2 1874.38
   212.3 1870.94   228.6 1870.18   244.9 1872.28   277.6 1872.53   290.6  1869.7
   316.8 1871.88   342.9 1871.38   353.1  1869.9   362.5 1869.66   375.6 1870.06
   382.1 1871.41   385.4 1873.48   398.4 1885.23   408.2 1895.36   411.5 1897.67
  429.141906.297   440.9 1912.71  452.68 1913.42   489.8 1914.12  500.571913.307
  511.531912.781  536.911911.301   587.8 1907.98   600.9 1904.73     614 1902.94
#Mann= 9 ,-1 , 0
       0     .06       0  109.49     .12       0   353.1    .045       0
   375.6     .12       0  429.14     .06       0  452.68    .016       0
  500.57     .12       0  511.53     .08       0  536.91     .12       0
Bank Sta=353.1,375.6
XS Rating Curve= 0 ,0
Exp/Cntr=0.3,0.1

Type RM Length L Ch R = 1 ,46795.1 ,608,617.8,626.4
XS GIS Cut Line= 3
     2062130.319      181875.775     2062586.048      182051.556
     2062727.107      182023.344
#Sta/Elev= 30
       0  1917.7    42.6 1905.56    78.7 1896.68   95.691891.648   137.7 1877.25
   160.6 1873.44     259 1870.45  331.361871.216   347.5 1871.69   360.6 1871.27
     377 1869.58   390.1 1866.82   396.7 1865.87   416.3 1865.83   426.2 1866.26
   445.8  1869.3   498.3 1881.85   508.1 1884.92   527.7 1892.06   560.4 1905.96
     580  1916.8  588.631923.208   596.3 1929.01   599.6 1930.68   609.4 1931.96
  620.191931.831   622.5 1931.88   625.8 1933.29     629 1936.14   632.3 1940.14
#Mann= 7 ,-1 , 0
       0     .12       0   95.69     .06       0  331.36     .12       0
   390.1    .045       0   416.3     .12       0  588.63    .016       0
  620.19     .12       0
Bank Sta=390.1,416.3
XS Rating Curve= 0 ,0
Exp/Cntr=0.3,0.1

Type RM Length L Ch R = 1 ,46177.3 ,537.7,556.5,574.5
XS GIS Cut Line= 3
     2061926.325      182218.657     2062390.735      182672.216
     2062549.155      182713.449
#Sta/Elev= 30
       0 1921.82     9.8 1917.31      23 1912.36    45.9 1901.02    75.4 1889.56
   101.6 1883.03   132.71878.028   163.9 1871.92   186.9 1868.38   209.8 1866.34
   229.5 1866.35  233.311865.234   239.3 1863.73   265.6 1864.94   287.8 1863.77
   298.4 1862.87   308.2 1863.72  339.461864.743   370.5 1865.82   380.3 1867.07
   514.7 1869.66  675.24 1870.18   708.1 1871.07  714.81 1874.56   721.2  1879.8
   724.4 1881.13   744.1 1881.39  754.231889.152   793.2 1909.36   812.8 1918.24
#Mann= 9 ,-1 , 0
       0     .12       0   132.7     .06       0  233.31     .12       0
   287.8    .045       0   308.2     .12       0  339.46     .06       0
  675.24     .12       0  714.81    .016       0  754.23     .12       0
#XS Ineff= 2 , 0
                           452.8         1876.17
Permanent Ineff=
       F       F
Bank Sta=287.8,308.2
XS Rating Curve= 0 ,0
Exp/Cntr=0.3,0.1

Type RM Length L Ch R = 1 ,45620.9 ,479.1,492.3,502.8
XS GIS Cut Line= 3
     2061618.166      182448.692     2061646.378      182537.667
     2061663.739      183149.646
#Sta/Elev= 30
       0  1925.1     6.4 1923.21    16.1 1922.21    32.2 1916.16    64.4 1900.26
    93.3 1882.89   116.3 1873.36   129.4 1869.94  161.111865.057   181.7 1865.06
   194.8 1862.06   204.6 1860.94   214.5 1861.38  286.48 1862.37   306.2 1862.19
   332.3 1860.58   342.2 1860.83     352 1862.59     388 1863.86     424 1866.27
  457.781869.683   482.9 1873.24  528.511877.818   561.5 1881.26   574.6 1885.58
  621.721886.108   636.8 1887.65   653.2 1890.96   679.4 1893.94   705.6 1901.03
#Mann= 8 ,-1 , 0
       0     .12       0  161.11     .06       0   194.8    .045       0
   214.5     .06       0  286.48     .12       0  457.78     .06       0
  528.51    .016       0  621.72     .06       0
Bank Sta=194.8,214.5
XS Rating Curve= 0 ,0
Exp/Cntr=0.3,0.1