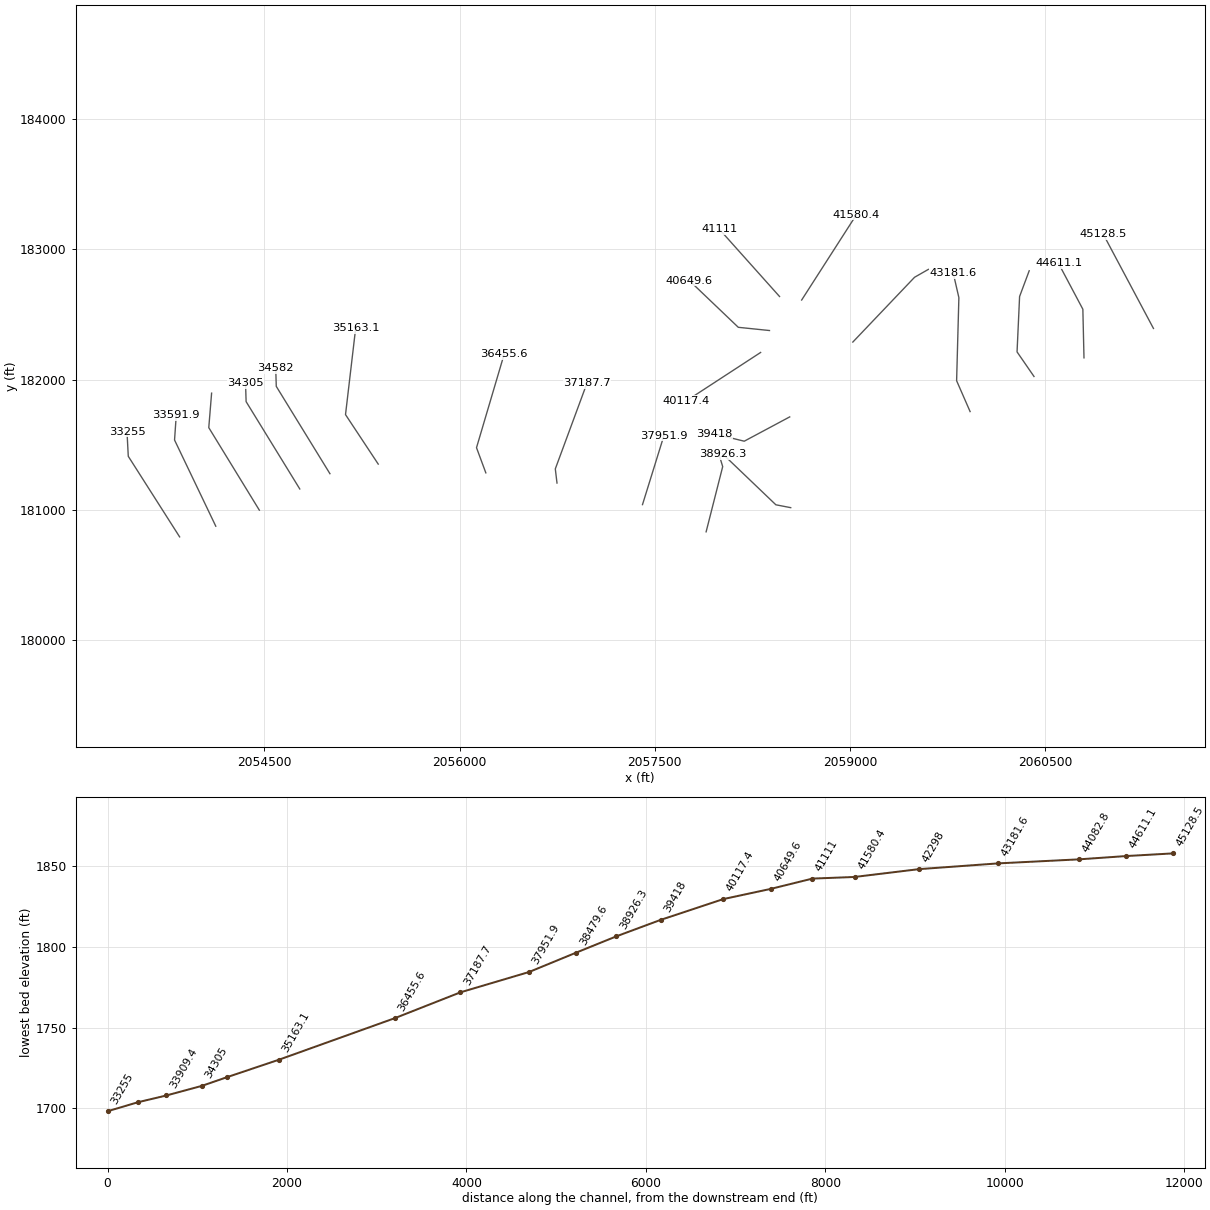
HEC-RAS study HNSCK.prj: HNSCK

--- HNSCK.g01 (geometry) --- (continued)

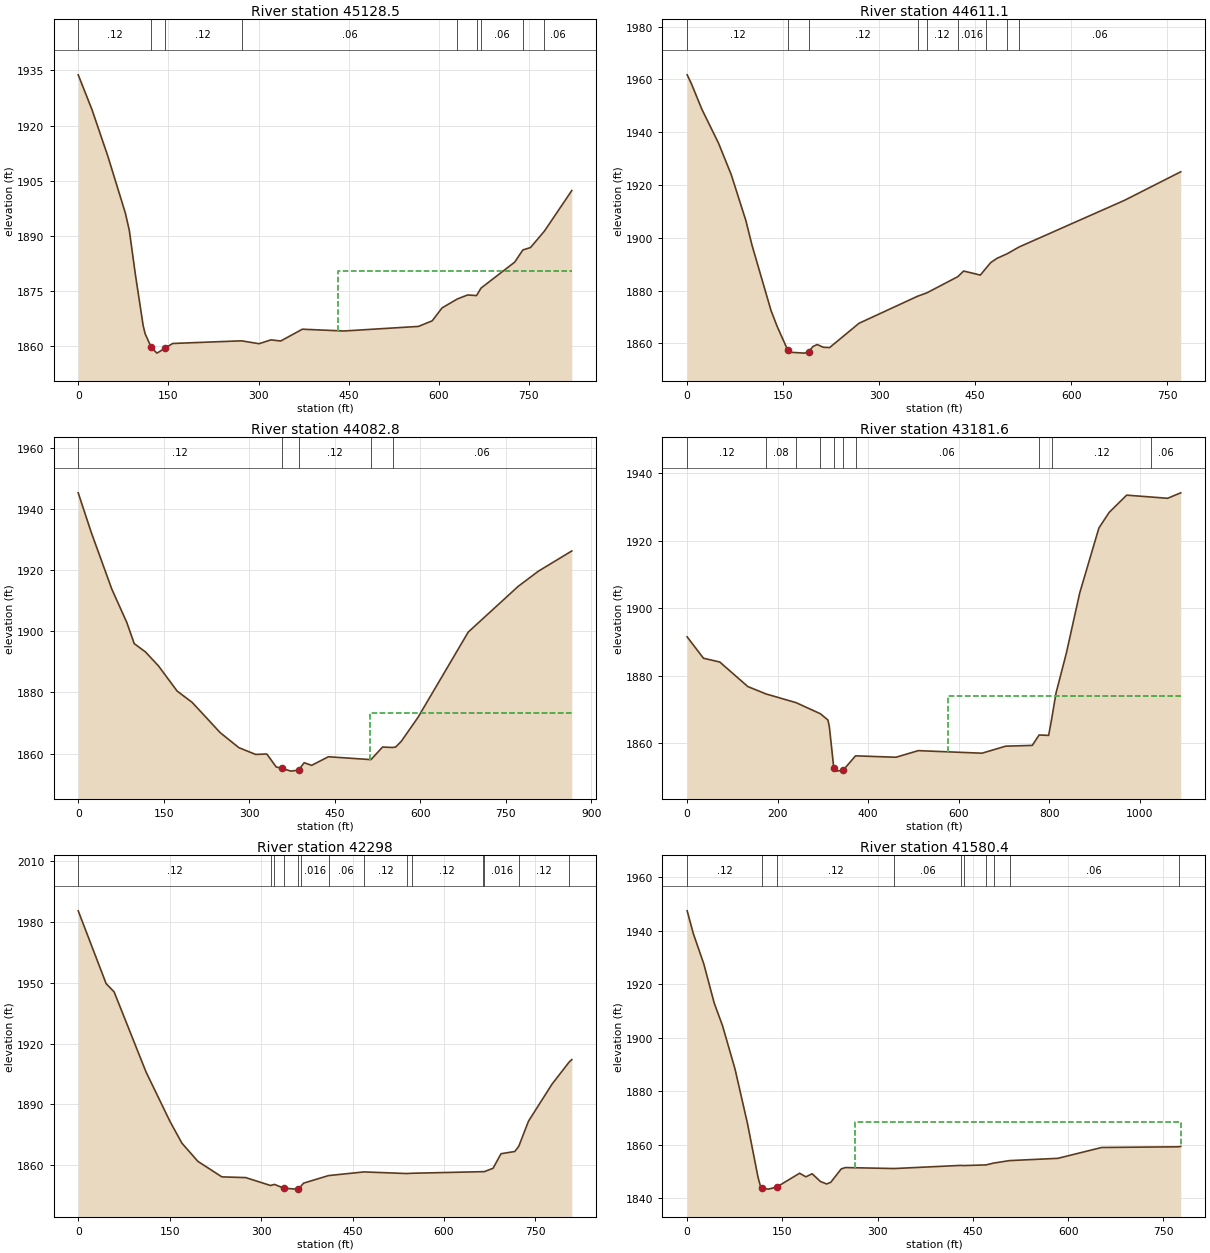
Type RM Length L Ch R = 1 ,45128.5 ,527.7,517.4,506.6
XS GIS Cut Line= 2
     2061331.707      182392.268     2060945.423      183117.094
#Sta/Elev= 30
       0 1933.81    22.9 1924.33    49.1 1911.74    78.5 1896.11    85.1 1891.35
    94.9 1879.64     108 1865.54   111.3 1863.27   121.5 1859.55   130.9 1857.97
     144 1859.25   157.1  1860.6   271.71861.322     301 1860.54   320.7 1861.58
     337 1861.28     373 1864.49   441.8    1864   566.1 1865.25     589 1866.77
   605.4 1870.29  630.861872.726   647.9 1873.82  662.791873.657  670.331875.703
   726.4 1882.78  739.861886.086   752.6 1886.74  775.76 1891.23   821.3 1902.27
#Mann= 9 ,-1 , 0
       0     .12       0   121.5    .045       0     144     .12       0
   271.7     .06       0  630.86    .016       0  662.79     .08       0
  670.33     .06       0  739.86    .016       0  775.76     .06       0
#XS Ineff= 2 , 0
                          431.88         1880.36
Permanent Ineff=
       F       F
Bank Sta=121.5,144
XS Rating Curve= 0 ,0
Exp/Cntr=0.3,0.1

Type RM Length L Ch R = 1 ,44611.1 ,528.1,528.3,525
XS GIS Cut Line= 3
     2060797.853      182166.574     2060789.173      182539.837
     2060602.541        182891.4
#Sta/Elev= 30
       0 1961.71     6.6 1958.38    22.9 1948.72    49.1 1935.79    68.8 1923.97
    91.7 1906.58   101.5 1897.07     131 1872.52   140.8 1866.36   157.2 1857.48
   160.5 1856.68   183.4 1856.34     190 1856.92   196.5 1858.82   203.1 1859.59
   212.9 1858.56   222.7 1858.45   268.6 1867.64   360.11877.879  374.661879.165
  422.991885.288   432.1 1887.43   458.2 1885.89  467.181888.537   474.5 1890.63
   484.3 1892.24  500.621894.022  518.611896.514   683.3 1914.17   771.4    1925
#Mann= 9 ,-1 , 0
       0     .12       0   157.2    .045       0     190     .12       0
   360.1     .06       0  374.66     .12       0  422.99    .016       0
  467.18     .08       0  500.62     .12       0  518.61     .06       0
Bank Sta=157.2,190
XS Rating Curve= 0 ,0
Exp/Cntr=0.3,0.1

Type RM Length L Ch R = 1 ,44082.8 ,898.3,901.2,897.2
XS GIS Cut Line= 4
     2060413.739      182023.344      2060283.53      182212.146
     2060303.062      182637.494     2060376.846      182834.976
#Sta/Elev= 30
       0 1945.26    22.9 1932.31      59 1913.76    85.2  1902.9    98.3 1895.97
     118 1893.25   140.9 1888.67   173.6 1880.45   199.9 1876.77     249 1866.89
   281.8 1861.97   311.2 1859.75   330.9 1859.89   347.3 1855.67   357.1 1855.19
   373.5 1854.29   386.6 1854.62   396.4 1857.04   409.5 1856.18     439 1858.99
  513.621858.049     534 1862.16   551.61862.022   556.9 1862.15   566.7    1864
   596.2 1871.88   684.3 1899.74   771.9 1914.68   807.6 1919.67     866 1926.26
#Mann= 5 ,-1 , 0
       0     .12       0   357.1    .045       0   386.6     .12       0
  513.62    .016       0   551.6     .06       0
#XS Ineff= 2 , 0
                          512.72         1873.14
Permanent Ineff=
       F       F
Bank Sta=357.1,386.6
XS Rating Curve= 0 ,0
Exp/Cntr=0.3,0.1

Type RM Length L Ch R = 1 ,43181.6 ,899.6,883.6,866.1
XS GIS Cut Line= 4
     2059922.745      181753.871     2059819.121      181990.792
     2059836.482      182628.813     2059793.079      182817.615
#Sta/Elev= 30
       0 1891.56      36 1885.24      72 1884.12   134.2 1876.83  174.471874.649
   240.51872.083  294.091868.809     311 1866.95   314.2 1864.92     324 1852.72
   330.6 1851.79   345.1 1852.11  371.991856.321   461.5  1855.9   510.6 1857.86
   651.4  1857.1   703.7 1859.18   762.6 1859.41  777.651862.496   798.7 1862.38
  805.211867.049     815 1874.91   837.9 1886.77   867.4 1904.58   909.8 1923.83
   932.4 1928.43   971.1 1933.55 1025.631932.994  1061.5 1932.62  1090.6 1934.24
#Mann= 10 ,-1 , 0
       0     .12       0  174.47     .08       0   240.5     .06       0
  294.09     .12       0     324    .045       0   345.1     .12       0
  371.99     .06       0  777.65    .016       0  805.21     .12       0
 1025.63     .06       0
#XS Ineff= 2 , 0
                          575.92         1874.05
Permanent Ineff=
       F       F
Bank Sta=324,345.1
XS Rating Curve= 0 ,0
Exp/Cntr=0.3,0.1

Type RM Length L Ch R = 1 ,42298   ,714,717.6,720
XS GIS Cut Line= 3
     2059021.703      182287.725      2059495.77      182785.063
     2059602.107      182845.827
#Sta/Elev= 30
       0  1985.6    45.8 1949.65    58.9 1945.59   111.2 1906.09   150.5 1881.65
   170.1 1870.91   196.3 1861.93   235.6 1854.27   274.8 1853.91  315.531850.006
  321.761850.566     337 1848.72   356.6 1848.22   359.9 1848.35  365.181849.629
   369.7 1851.18  410.581854.903   468.81856.717  539.121855.912  546.851856.053
  664.161856.839  666.121856.852   680.5 1858.53   693.5 1865.69   716.1  1866.8
  722.641869.367   738.6 1881.78   777.3  1900.1  805.651911.096   809.6 1912.16
#Mann= 14 ,-1 , 0
       0     .12       0  315.53     .06       0  321.76     .12       0
     337    .045       0   359.9     .12       0  365.18    .016       0
  410.58     .06       0   468.8     .12       0  539.12     .06       0
  546.85     .12       0  664.16     .06       0  666.12    .016       0
  722.64     .12       0  805.65     .06       0
Bank Sta=337,359.9
XS Rating Curve= 0 ,0
Exp/Cntr=0.3,0.1

Type RM Length L Ch R = 1 ,41580.4 ,439.3,469.4,498.4
XS GIS Cut Line= 2
     2058628.474      182610.642     2059048.721      183264.664
#Sta/Elev= 30
       0 1947.39     9.8 1938.81    26.2 1927.56    42.6 1912.93    55.8 1904.38
    75.4 1888.25    95.1  1867.8   111.5 1847.95   114.8    1845   118.1 1843.68
   127.9 1843.38     141 1844.15   177.1 1849.32     187 1847.98   196.8 1849.12
   209.9 1846.24   219.8  1845.3   226.3 1845.96   242.7 1850.94   249.3 1851.44
  326.161851.076  431.28 1852.25  435.551852.181  470.661852.434  483.121853.125
  507.761854.042   583.9 1854.89   652.8 1858.94  773.991859.199   777.4 1859.35
#Mann= 10 ,-1 , 0
       0     .12       0   118.1    .045       0     141     .12       0
  326.16     .06       0  431.28     .12       0  435.55    .016       0
  470.66     .12       0  483.12    .016       0  507.76     .06       0
  773.99    .016       0
#XS Ineff= 2 , 0
                          263.65         1868.29
Permanent Ineff=
       F       F
Bank Sta=118.1,141
XS Rating Curve= 0 ,0
Exp/Cntr=0.3,0.1

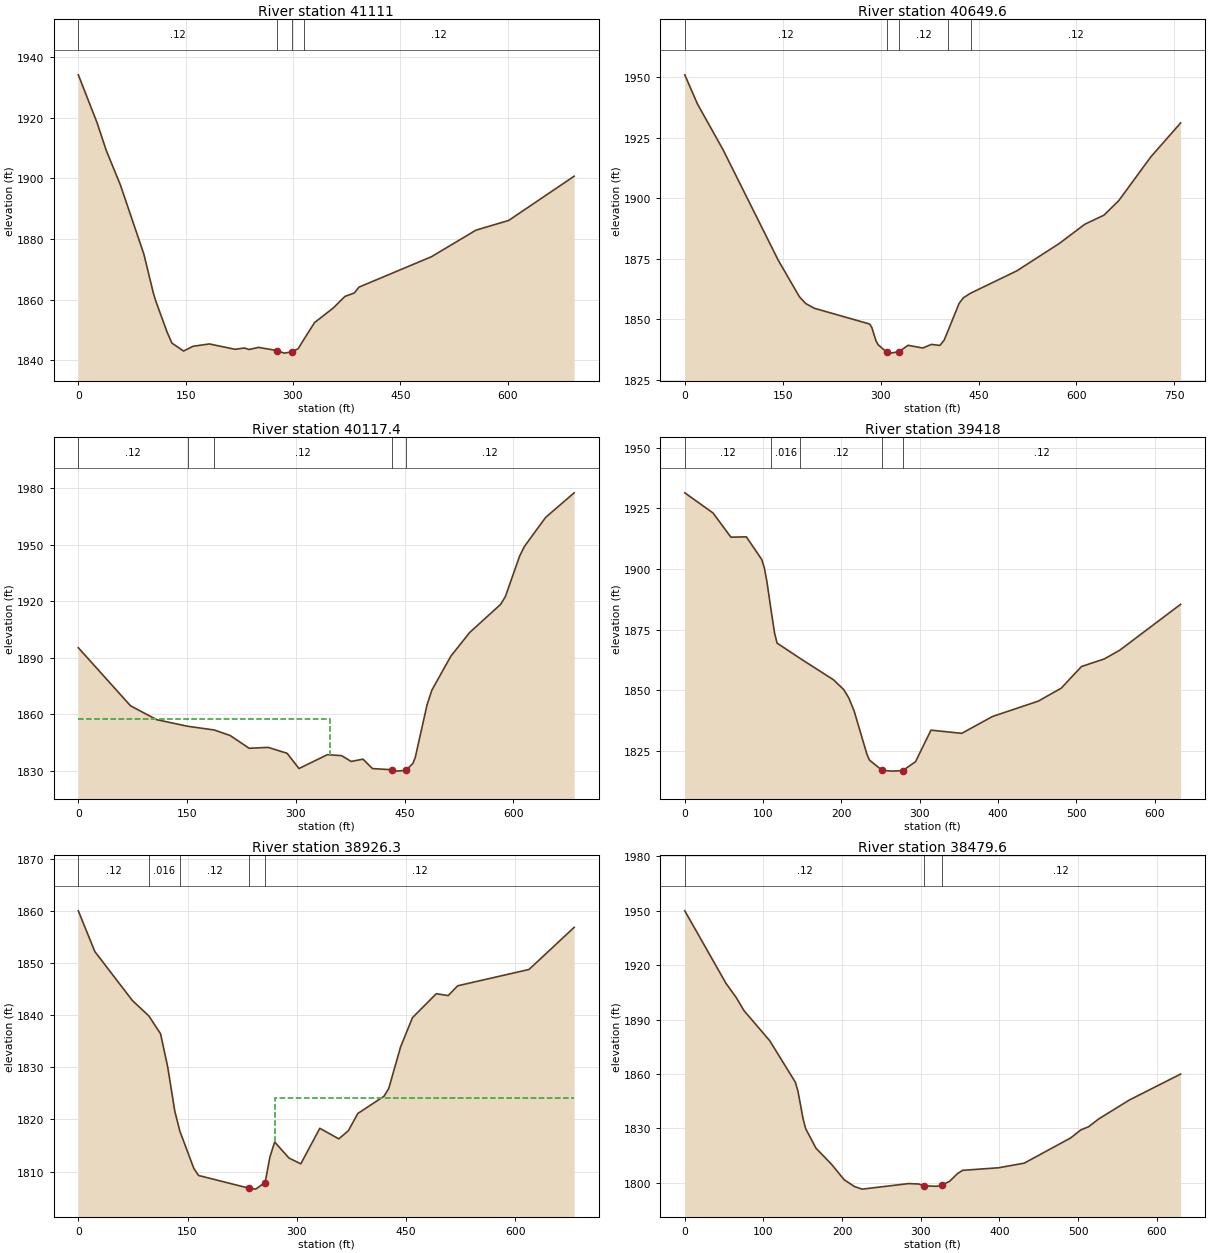
Type RM Length L Ch R = 1 ,41111   ,459.3,461.4,463.2
XS GIS Cut Line= 2
     2058458.444      182637.494     2057996.204      183153.987
#Sta/Elev= 30
       0 1934.17    26.2 1918.37    39.2 1909.13    58.8 1897.85    91.6 1875.04
   104.6 1862.44   107.9 1859.79   124.2 1849.24   130.8 1845.68   147.1 1843.06
   160.2 1844.62   183.1  1845.4   219.1 1843.63   232.1 1844.06   238.7 1843.57
   251.8 1844.27   277.9 1843.21   287.7 1842.37   298.4 1842.79   307.3 1843.81
  316.131847.214   330.2 1852.44   356.4 1857.27   372.7 1861.08   385.8 1862.21
   392.3 1864.14   493.7 1874.18   555.8 1882.93   601.6 1886.14   693.1 1900.73
#Mann= 4 ,-1 , 0
       0     .12       0   277.9    .045       0   298.4    .016       0
  316.13     .12       0
Bank Sta=277.9,298.4
XS Rating Curve= 0 ,0
Exp/Cntr=0.3,0.1

Type RM Length L Ch R = 1 ,40649.6 ,501,532.2,561.8
XS GIS Cut Line= 3
     2058381.078      182376.267     2058141.603      182400.949
     2057766.169      182759.021
#Sta/Elev= 30
       0 1950.92    19.5 1938.84    58.6    1920   143.1 1874.41   175.7 1859.25
   185.4 1856.48   198.4 1854.55   283.2 1848.04   286.4 1846.69     293 1841.05
   296.2 1839.51   309.2 1836.43   315.8 1836.03   328.8  1836.7   341.9 1839.26
   364.7 1838.14   377.8 1839.64   390.8  1839.2   397.4 1841.42  403.031845.125
   420.2 1856.51   426.7 1858.87  437.961860.788   508.3 1869.94   573.6 1881.27
   612.7 1889.22   642.1 1892.97   664.9    1899   713.9 1917.03   759.6 1931.06
#Mann= 5 ,-1 , 0
       0     .12       0   309.2    .045       0   328.8     .12       0
  403.03    .016       0  437.96     .12       0
Bank Sta=309.2,328.8
XS Rating Curve= 0 ,0
Exp/Cntr=0.3,0.1

Type RM Length L Ch R = 1 ,40117.4 ,701.4,699.4,696.2
XS GIS Cut Line= 2
     2058313.044      182207.806     2057740.128      181834.542
#Sta/Elev= 30
       0 1895.27      72  1864.4     108 1857.03  150.621853.531  187.611851.529
   209.4  1848.6   235.6 1841.81   261.7  1842.3   287.9 1839.16   304.3 1831.06
   343.5 1838.41   363.2  1837.9   376.2 1834.81   392.6 1836.04   405.7 1831.02
   431.9 1830.42   438.4 1829.67   451.9 1830.09   461.3 1833.73   464.6 1836.83
   480.9 1864.87   487.5 1872.67   513.7 1890.76   539.8 1903.41   582.4 1918.33
   588.9 1922.43   608.5 1943.88   615.1 1949.06   644.5 1964.57   683.8 1977.62
#Mann= 5 ,-1 , 0
       0     .12       0  150.62    .016       0  187.61     .12       0
   431.9    .045       0   451.9     .12       0
#XS Ineff= 2 , 0
          347.03 1857.14
Permanent Ineff=
       F       F
Bank Sta=431.9,451.9
XS Rating Curve= 0 ,0
Exp/Cntr=0.3,0.1

Type RM Length L Ch R = 1 ,39418   ,520.7,491.7,457.5
XS GIS Cut Line= 3
     2058536.569      181713.015     2058187.176      181526.383
     2057957.141      181582.806
#Sta/Elev= 30
       0 1931.39      36  1923.1    58.9 1913.12    78.6 1913.26    98.2 1903.95
   101.5 1900.55   104.8  1894.9  110.461882.408   114.6 1873.66   117.8  1869.5
   147.61863.113   189.9 1854.38     203 1850.32   209.5 1846.83   216.1 1841.63
   232.4 1823.86   235.7 1821.34   252.1 1817.05   265.2 1816.77   278.3 1816.99
   294.6 1820.68   314.3 1833.65   353.6 1832.33   392.8 1839.27   451.3  1845.6
   480.5 1850.91   506.4 1859.85   535.6 1862.98   555.1 1866.53     633 1885.47
#Mann= 5 ,-1 , 0
       0     .12       0  110.46    .016       0   147.6     .12       0
   252.1    .045       0   278.3     .12       0
Bank Sta=252.1,278.3
XS Rating Curve= 0 ,0
Exp/Cntr=0.3,0.1

Type RM Length L Ch R = 1 ,38926.3 ,468.3,446.7,425.2
XS GIS Cut Line= 3
     2058544.286      181016.056     2058430.232      181038.101
     2058021.972      181428.322
#Sta/Elev= 30
       0 1860.01    22.6 1852.21    74.2 1842.81   96.891839.838   112.9 1836.43
   122.7 1830.09   132.5 1821.55  139.391817.767   158.6 1810.59   165.1 1809.24
   234.7 1806.79   243.5 1806.62   256.5 1807.89   263.1  1812.8   269.6 1815.66
   289.2 1812.59   305.5 1811.47   331.6 1818.29   357.7 1816.27   370.8 1817.82
   383.8 1821.13   419.8 1824.44   426.3 1825.93   442.6 1833.93   458.9 1839.52
   491.6 1844.11   507.9 1843.75     521 1845.63   618.9 1848.76   680.9 1856.84
#Mann= 5 ,-1 , 0
       0     .12       0   96.89    .016       0  139.39     .12       0
   234.7    .045       0   256.5     .12       0
#XS Ineff= 2 , 0
                          269.87         1824.17
Permanent Ineff=
       F       F
Bank Sta=234.7,256.5
XS Rating Curve= 0 ,0
Exp/Cntr=0.3,0.1

Type RM Length L Ch R = 1 ,38479.6 ,528.2,527.7,526
XS GIS Cut Line= 3
     2057894.261      180830.413     2058021.635      181331.138
     2057988.704      181439.947
#Sta/Elev= 30
       0 1950.01    52.3 1910.07    65.4  1902.2    75.2 1895.02   107.9 1878.44
   140.6 1855.48   143.9  1850.5   150.4 1835.35   153.7 1829.88   166.8 1819.11
   186.4 1810.34   202.7 1801.72   215.8 1797.95   225.6 1796.56   284.5 1799.61
   297.6 1799.38   304.1 1798.36   320.5 1798.13     327 1798.84   336.8 1800.92
   346.6 1805.08   353.2 1806.92     399 1808.34   431.6 1810.89   490.5 1824.76
   503.6 1829.22   513.4 1830.95   526.4 1835.31   565.4 1845.74   630.4    1860
#Mann= 3 ,-1 , 0
       0     .12       0   304.1    .045       0     327     .12       0
Bank Sta=304.1,327
XS Rating Curve= 0 ,0
Exp/Cntr=0.3,0.1

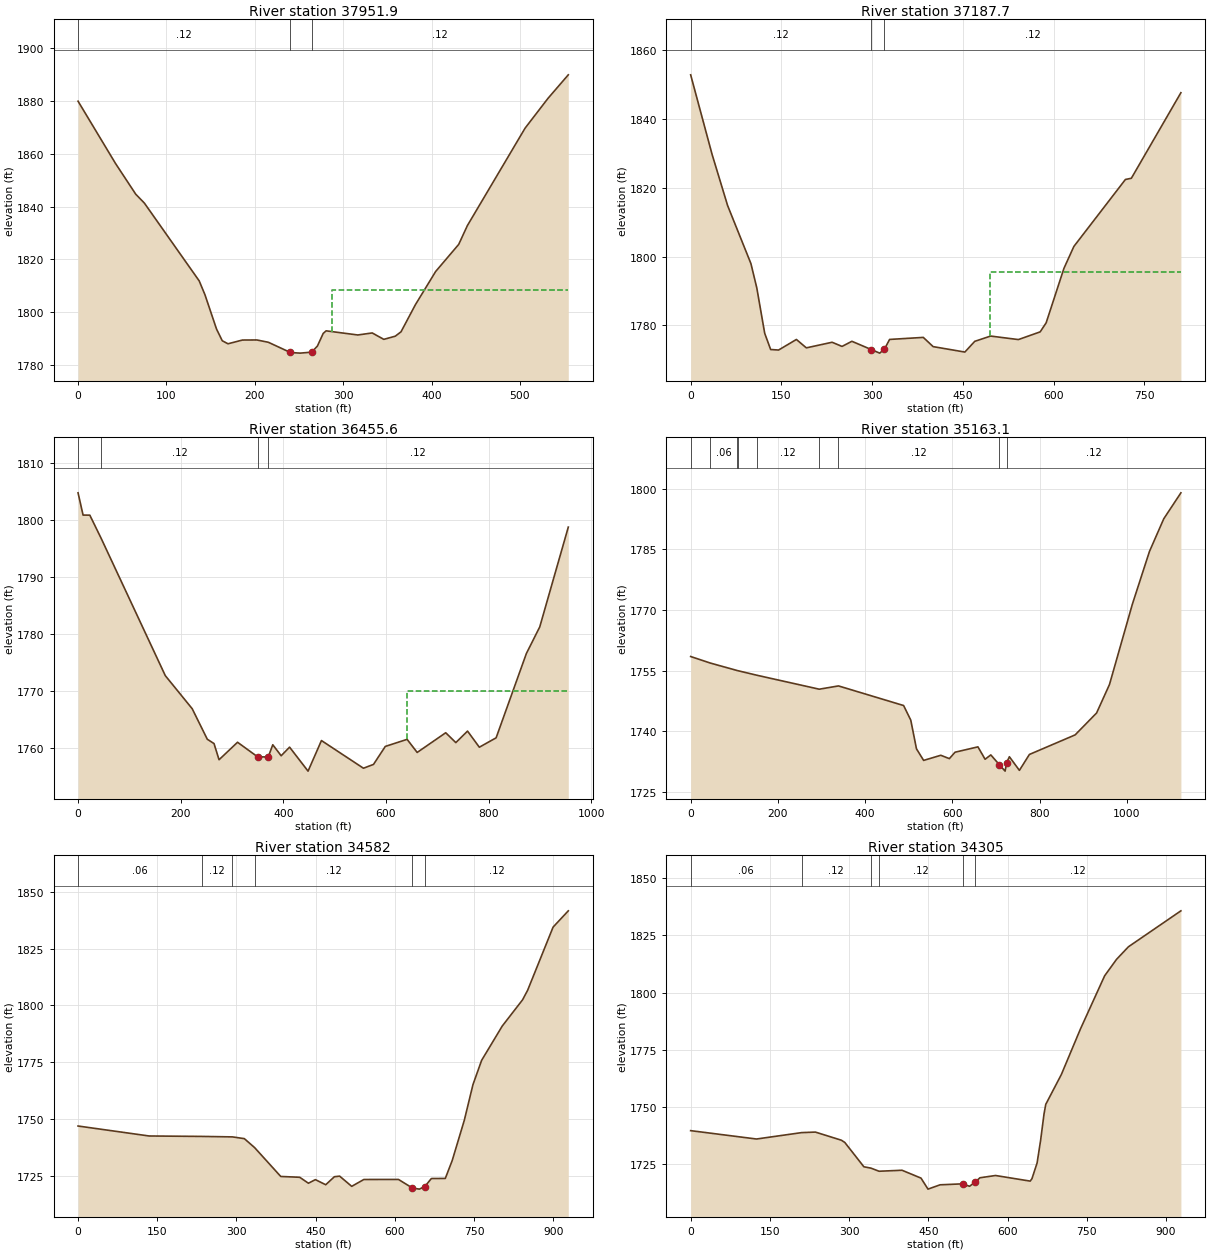
Type RM Length L Ch R = 1 ,37951.9 ,764.8,764.2,762.2
XS GIS Cut Line= 2
     2057405.416      181039.443     2057570.112      181569.254
#Sta/Elev= 30
       0 1880.01    42.4  1856.4    65.3 1844.75    75.1 1841.37   137.1 1811.89
   143.6 1806.66   156.7 1793.64   163.2 1789.19   169.7 1788.04     186 1789.46
   202.4 1789.49   215.4 1788.61   240.3 1784.74   251.3  1784.5   264.4 1784.87
   270.9 1787.19   277.4 1791.95   280.7 1792.95   316.6 1791.38   332.9 1792.15
     346 1789.72     359 1790.92   365.5 1792.58   381.8 1802.88   404.7 1815.45
   430.8 1825.73   440.6 1832.85   505.9 1869.79     532 1881.16   554.8 1890.01
#Mann= 3 ,-1 , 0
       0     .12       0   240.3    .045       0   264.4     .12       0
#XS Ineff= 2 , 0
                          287.28         1808.57
Permanent Ineff=
       F       F
Bank Sta=240.3,264.4
XS Rating Curve= 0 ,0
Exp/Cntr=0.3,0.1

Type RM Length L Ch R = 1 ,37187.7 ,729.5,732,732.7
XS GIS Cut Line= 3
     2056748.374      181205.202     2056735.353      181313.709
     2056978.409      181971.261
#Sta/Elev= 30
       0 1852.83    35.4 1829.71    61.1 1814.82    99.6 1797.96   109.3  1790.9
   122.4 1777.69   132.2 1772.98   145.3 1772.83   174.8  1775.9   191.2 1773.46
   233.8 1775.09   250.2 1773.88   266.5 1775.37   298.4 1772.98   312.4 1771.93
  320.19 1773.05   328.8 1775.91   384.5  1776.5   400.8 1773.82   453.2 1772.24
   469.6 1775.36   495.8 1776.89   541.7 1775.87   577.7 1778.11   587.6 1780.75
     617 1796.58   633.4 1802.94   718.6 1822.41   728.4 1822.76   810.3 1847.63
#Mann= 3 ,-1 , 0
       0     .12       0   298.4    .045       0  320.19     .12       0
#XS Ineff= 2 , 0
                          494.63          1795.6
Permanent Ineff=
       F       F
Bank Sta=298.4,320.19
XS Rating Curve= 0 ,0
Exp/Cntr=0.3,0.1

Type RM Length L Ch R = 1 ,36455.6 ,1283.2,1292.5,1294.3
XS GIS Cut Line= 3
     2056201.499      181283.327     2056129.885      181476.469
     2056342.558      182194.785
#Sta/Elev= 30
       0  1804.8     9.8 1800.89    22.9 1800.88   45.161796.779     170 1772.69
   222.4 1766.88   251.8 1761.52   264.9 1760.76   274.7 1757.92   310.7 1760.99
   349.9 1758.43   370.5 1758.41   379.4 1760.55   395.7 1758.62   412.1 1760.13
   448.1 1755.92   474.2 1761.29     556 1756.43   575.6  1757.1   598.6 1760.26
   641.1  1761.5   660.7  1759.2   716.3 1762.66     736 1760.93   758.8 1762.95
   781.8 1760.12   814.5 1761.77   873.4 1776.57   899.5 1781.25   955.1 1798.78
#Mann= 4 ,-1 , 0
       0    .016       0   45.16     .12       0   349.9    .045       0
   370.5     .12       0
#XS Ineff= 2 , 0
                          641.04         1769.93
Permanent Ineff=
       F       F
Bank Sta=349.9,370.5
XS Rating Curve= 0 ,0
Exp/Cntr=0.3,0.1

Type RM Length L Ch R = 1 ,35163.1 ,567.6,581.1,595.3
XS GIS Cut Line= 3
     2055374.676      181350.601     2055123.266      181730.433
     2055201.391      182394.496
#Sta/Elev= 30
       0 1758.51   45.011756.896  107.211755.032  108.251755.005  151.911753.881
  294.881750.431  338.951751.241   488.3 1746.39   504.7 1742.78   517.8 1735.68
   534.2 1732.82   573.5 1734.09   593.2 1733.26   606.3 1734.85   658.7 1736.17
   675.1 1733.11   688.2 1734.18   707.9 1731.75     721 1730.17   724.5 1732.22
   730.8 1733.73   753.8 1730.36   776.7 1734.29   881.6 1739.13   930.8 1744.55
   960.3 1751.58  1012.7 1771.41    1052 1784.49  1084.8 1792.57  1124.1 1798.99
#Mann= 9 ,-1 , 0
       0    .016       0   45.01     .06       0  107.21     .12       0
  108.25     .06       0  151.91     .12       0  294.88    .016       0
  338.95     .12       0   707.9    .045       0   724.5     .12       0
Bank Sta=707.9,724.5
XS Rating Curve= 0 ,0
Exp/Cntr=0.3,0.1

Type RM Length L Ch R = 1 ,34582   ,284.5,276.9,276.8
XS GIS Cut Line= 3
     2055003.582      181276.817     2054591.256       181947.39
     2054586.916      182088.449
#Sta/Elev= 30
       0 1747.04   134.5 1742.66  234.351742.469  292.171742.261   314.9 1741.49
  334.341737.554   383.8 1724.88   419.8 1724.51   436.2  1721.9   449.4 1723.48
     469 1721.24   485.4 1724.76   495.3 1725.02   518.2 1720.53   541.2 1723.55
   606.8 1723.56     633 1719.81   646.2 1719.31   656.5 1720.44   669.1 1723.97
   695.4 1724.01   708.5 1731.88   731.4 1749.57   747.8 1765.24   764.2  1775.9
   803.2 1790.95   841.7 1802.48   851.4 1806.73   899.5 1834.43   928.3 1841.59
#Mann= 6 ,-1 , 0
       0     .06       0  234.35     .12       0  292.17    .016       0
  334.34     .12       0     633    .045       0   656.5     .12       0
Bank Sta=633,656.5
XS Rating Curve= 0 ,0
Exp/Cntr=0.3,0.1

Type RM Length L Ch R = 1 ,34305   ,387.2,395.7,394.8
XS GIS Cut Line= 3
     2054771.812      181159.629     2054359.485      181830.202
     2054355.145      181971.261
#Sta/Elev= 30
       0 1739.58   124.6 1735.92  210.181738.719   236.2 1738.95   285.4 1735.39
   291.9 1734.41     328 1723.77  341.281723.182  356.751721.816   400.2 1722.25
   436.2 1718.81   449.4 1713.99   472.3 1715.88     515  1716.3   528.1 1715.23
   538.5 1717.05   547.8 1718.96   577.3 1719.95   642.9  1717.5   646.2 1718.52
     656 1725.44   662.6 1735.25   669.1 1746.86   672.4 1751.08   701.9 1764.13
     738 1784.03   783.9 1807.34   806.4 1814.53   828.9 1820.03   928.3 1835.77
#Mann= 6 ,-1 , 0
       0     .06       0  210.18     .12       0  341.28    .016       0
  356.75     .12       0     515    .045       0   538.5     .12       0
Bank Sta=515,538.5
XS Rating Curve= 0 ,0
Exp/Cntr=0.3,0.1

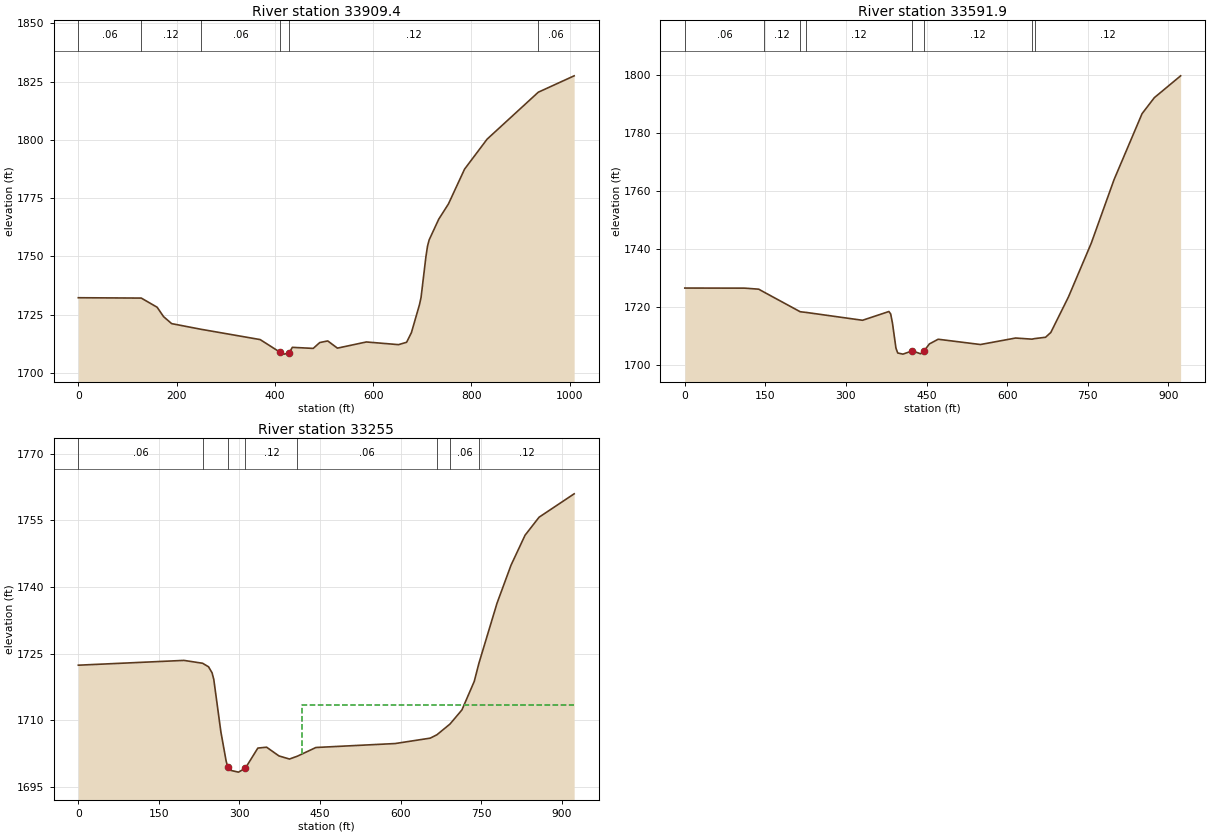
Type RM Length L Ch R = 1 ,33909.4 ,319.2,317.5,314.7
XS GIS Cut Line= 3
     2054461.048      180996.869     2054072.593      181630.549
     2054094.294      181895.306
#Sta/Elev= 30
       0 1732.24   128.1 1732.09   160.4 1728.15   173.5 1724.11   189.9 1721.13
  249.41 1718.71     370 1714.28   410.1  1708.9   419.1 1708.04   428.9 1708.58
   435.5 1710.95     478  1710.5   491.2    1713   507.5  1713.7   527.2 1710.61
   586.1 1713.26   651.6 1712.11     668 1713.13   677.8  1717.3   694.2 1729.29
   697.4 1732.41   707.2 1749.75   710.5 1754.34   713.8 1757.03   733.4 1765.96
   753.1 1772.49   785.9 1787.42   831.8 1800.29  935.85 1820.42  1008.9 1827.46
#Mann= 6 ,-1 , 0
       0     .06       0   128.1     .12       0  249.41     .06       0
   410.1    .045       0   428.9     .12       0  935.85     .06       0
Bank Sta=410.1,428.9
XS Rating Curve= 0 ,0
Exp/Cntr=0.3,0.1

Type RM Length L Ch R = 1 ,33591.9 ,333.7,336.9,339.5
XS GIS Cut Line= 3
     2054126.412      180873.605     2053809.572      181535.497
     2053822.593      181724.299
#Sta/Elev= 30
       0 1726.63   111.4  1726.6   137.6 1726.24  147.171725.262  214.831718.463
  226.391718.219   330.9 1715.52     380 1718.54   383.3  1717.7   386.6 1714.58
   393.1 1705.93   396.4 1704.24   406.2 1703.85   423.4 1704.98     439 1703.97
   445.5 1704.96   455.4 1707.37   471.7 1708.98   550.4 1707.16   615.9  1709.4
  646.431709.011  651.061709.195   671.6 1709.66   681.4 1711.31   714.2 1723.54
   756.7 1742.09   799.1 1763.98   851.3 1786.75   874.1 1792.26   923.1  1799.8
#Mann= 8 ,-1 , 0
       0     .06       0  147.17     .12       0  214.83     .06       0
  226.39     .12       0   423.4    .045       0   445.5     .12       0
  646.43     .06       0  651.06     .12       0
Bank Sta=423.4,445.5
XS Rating Curve= 0 ,0
Exp/Cntr=0.3,0.1

Type RM Length L Ch R = 1 ,33255   ,630.3,642.9,653.9
XS GIS Cut Line= 3
     2053848.536      180791.704     2053454.018      181410.449
     2053444.123       181599.44
#Sta/Elev= 30
       0 1722.39   196.6 1723.47  231.311722.828   242.4 1722.03     249 1720.67
   252.2 1719.17   265.4 1707.36   275.2 1700.77   278.5 1699.34   281.7 1698.74
   298.1 1698.29   310.9 1699.16   334.2 1703.71   350.5 1703.91   373.5 1701.94
   393.1 1701.24  407.971701.891   442.3 1703.84   589.7 1704.73   655.2 1705.95
  667.741706.723  691.991709.133   714.2 1712.32   737.1 1718.74  745.811722.838
   779.5 1736.36   805.6 1744.94   831.7 1751.68   857.8 1755.74   923.1 1761.01
#Mann= 8 ,-1 , 0
       0     .06       0  231.31     .12       0   278.5    .045       0
   310.9     .12       0  407.97     .06       0  667.74     .08       0
  691.99     .06       0  745.81     .12       0
#XS Ineff= 2 , 0
                          416.05         1713.33
Permanent Ineff=
       F       F
Bank Sta=278.5,310.9
XS Rating Curve= 0 ,0
Exp/Cntr=0.3,0.1