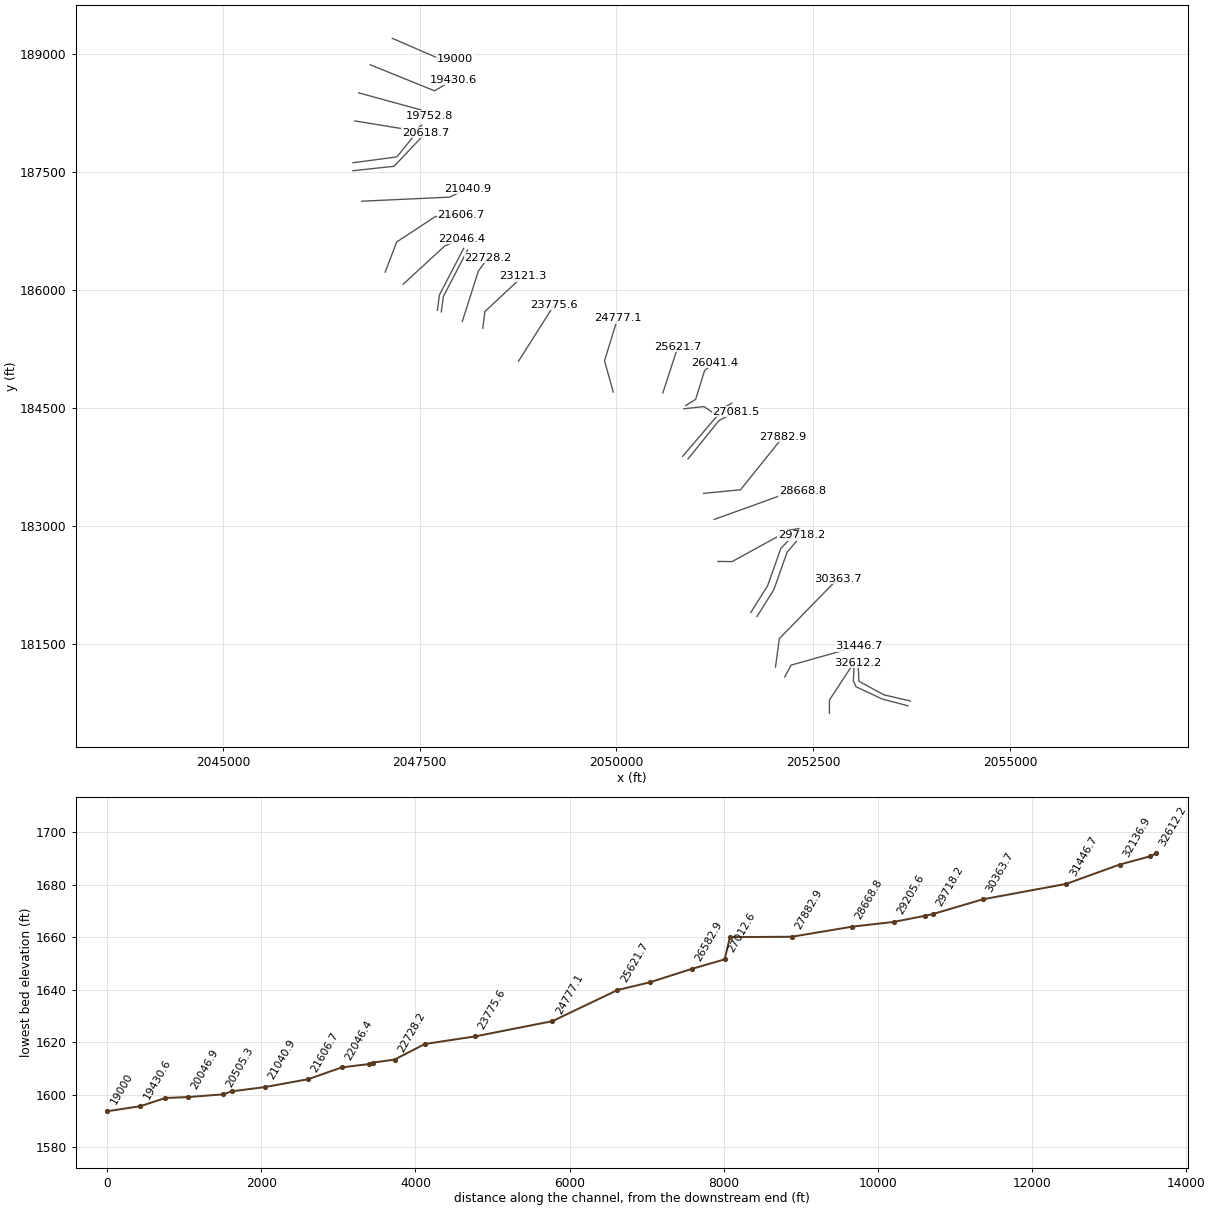
HEC-RAS study HNSCK.prj: HNSCK

--- HNSCK.g01 (geometry) --- (continued)

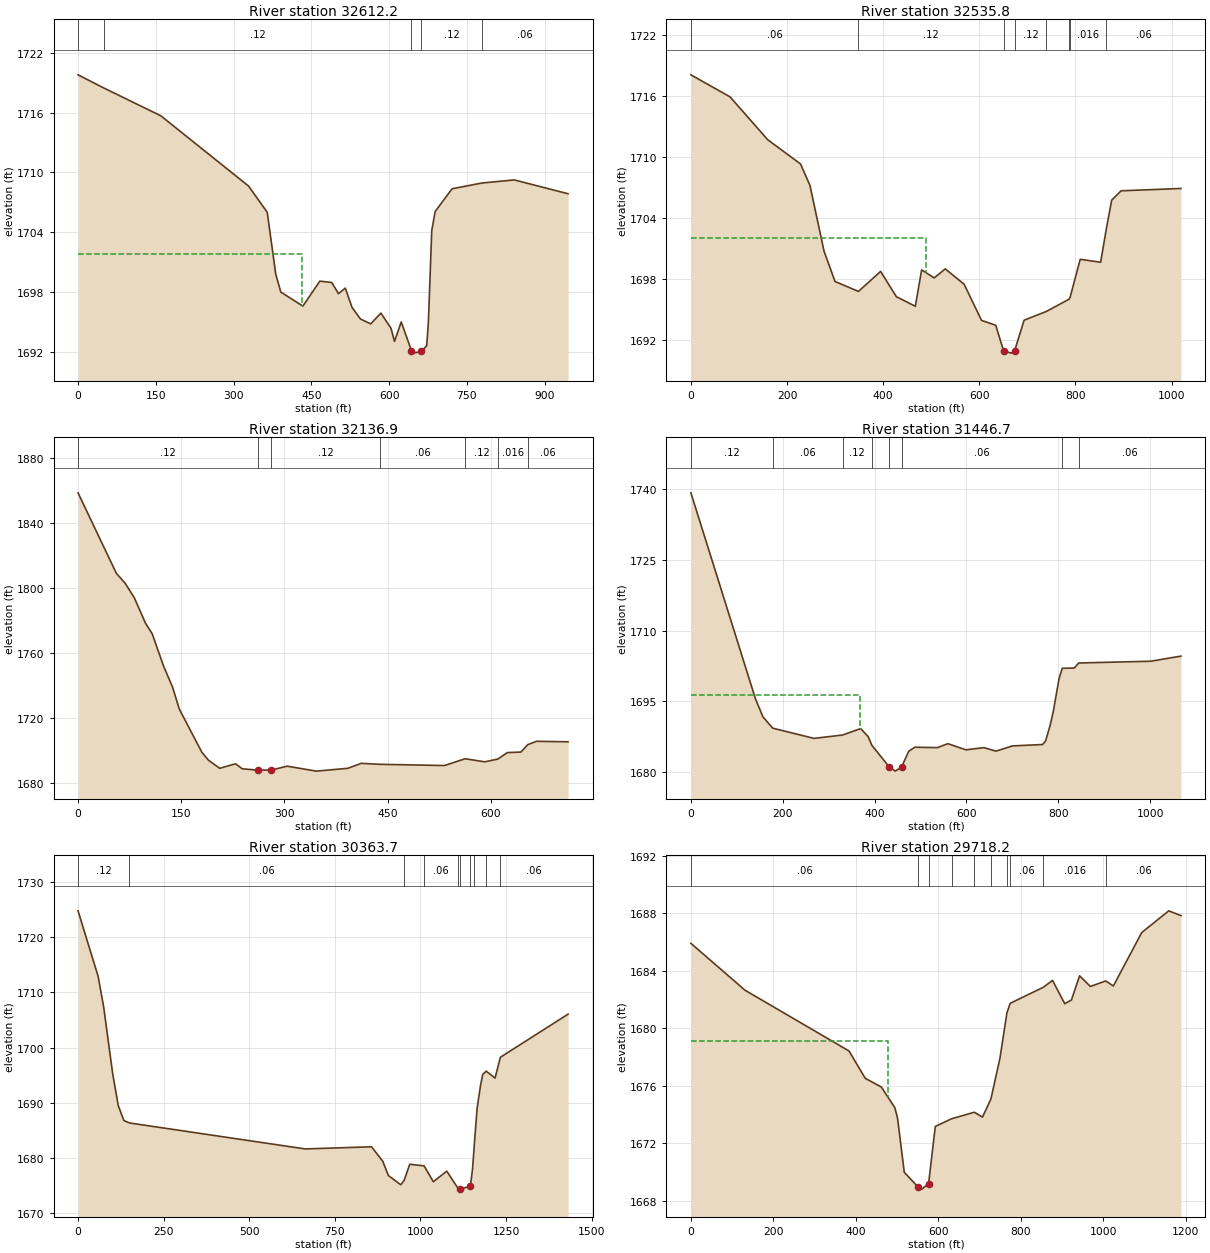
Type RM Length L Ch R = 1 ,32612.2 ,75.1,76.4,77.7
XS GIS Cut Line= 4
     2053736.221      180775.515      2053399.85       180853.64
     2053080.839      181027.251     2053072.159      181263.796
#Sta/Elev= 30
       0 1719.79   49.721718.467   159.6 1715.68     329 1708.62     365 1705.98
   381.3 1699.79   391.1 1697.98   433.7 1696.57   466.4 1699.08   489.3 1698.94
   502.4 1697.82   515.5 1698.38   528.6 1696.43   544.9 1695.27   564.6 1694.79
   584.2 1695.87   603.8 1694.33   610.4 1693.03   623.4 1694.98   643.1  1692.1
   646.4 1691.85   662.1 1692.02   672.5 1692.58   675.8 1694.98   682.3 1704.17
   688.9 1706.07   721.5 1708.35  778.821708.927   841.5 1709.24   945.2 1707.85
#Mann= 5 ,-1 , 0
       0     .06       0   49.72     .12       0   643.1    .045       0
   662.1     .12       0  778.82     .06       0
#XS Ineff= 2 , 0
          431.88 1701.79
Permanent Ineff=
       F       F
Bank Sta=643.1,662.1
XS Rating Curve= 0 ,0
Exp/Cntr=0.3,0.1

Type RM Length L Ch R = 1 ,32535.8 ,437.9,398.9,360
XS GIS Cut Line= 5
     2053703.995      180714.808     2053379.306      180799.909
     2053043.947      180957.806     2053011.395      181031.591
     2053022.246      181263.796
#Sta/Elev= 30
       0 1718.13    81.5 1715.96   159.7 1711.75   228.1 1709.36   247.7 1707.25
     277 1700.78   299.8  1697.8  348.511696.821   394.7 1698.79   427.5  1696.3
   466.9 1695.36     480 1698.94   506.2 1698.15   529.2 1699.04   568.6 1697.52
   604.6 1693.97   634.2 1693.49   650.6 1690.96     667 1690.75   673.5 1690.99
   693.2 1693.99  739.471694.849  786.751696.058  788.881696.236   809.9 1699.98
   852.4 1699.69  864.431703.026   875.4  1705.8     895 1706.72  1019.4 1706.95
#Mann= 8 ,-1 , 0
       0     .06       0  348.51     .12       0   650.6    .045       0
   673.5     .12       0  739.47    .016       0  786.75     .06       0
  788.88    .016       0  864.43     .06       0
#XS Ineff= 2 , 0
          489.09 1702.11
Permanent Ineff=
       F       F
Bank Sta=650.6,673.5
XS Rating Curve= 0 ,0
Exp/Cntr=0.3,0.1

Type RM Length L Ch R = 1 ,32136.9 ,705.9,690.2,673.7
XS GIS Cut Line= 3
     2052706.599      180618.454     2052707.575      180788.535
     2053004.885      181242.094
#Sta/Elev= 30
       0 1858.55    55.6  1809.2    68.7 1802.87    81.8 1794.09    98.1 1778.45
   107.9 1771.92   124.3 1752.15   137.4 1739.21   147.2 1725.71   179.9 1699.28
   189.7 1694.28     206 1689.32   228.9  1692.1   238.7 1689.03   261.6 1688.19
     281 1688.26     304 1690.63   346.5 1687.59   392.2 1689.33   411.8 1692.38
  438.441691.776   532.7 1691.03  562.791695.197   591.5  1693.3  610.471695.031
   624.2 1698.98   643.8  1699.3  653.86 1703.88   666.7 1705.92   712.4 1705.61
#Mann= 7 ,-1 , 0
       0     .12       0   261.6    .045       0     281     .12       0
  438.44     .06       0  562.79     .12       0  610.47    .016       0
  653.86     .06       0
Bank Sta=261.6,281
XS Rating Curve= 0 ,0
Exp/Cntr=0.3,0.1

Type RM Length L Ch R = 1 ,31446.7 ,1071.2,1082.9,1094.1
XS GIS Cut Line= 3
     2052138.999      181081.504     2052219.294      181231.244
      2053083.01      181474.299
#Sta/Elev= 30
       0 1739.16   140.5  1695.6   156.8 1691.76  178.391689.347   268.2 1687.19
  330.181687.899   369.7 1689.26     386 1687.59   394.2 1685.71   431.9 1681.17
     445 1680.26   458.7 1681.09   474.4 1684.46   487.6 1685.32   536.7 1685.23
   559.6 1686.07   598.9 1684.77   638.2 1685.23   664.4 1684.49   700.4  1685.6
   765.9 1685.89   772.4 1686.63   782.3 1689.92   788.8 1692.65   801.9 1699.87
  808.731702.021   834.7 1702.08  844.811703.147  1001.7 1703.52  1067.2  1704.6
#Mann= 8 ,-1 , 0
       0     .12       0  178.39     .06       0  330.18     .12       0
   394.2     .06       0   431.9    .045       0   458.7     .06       0
  808.73    .016       0  844.81     .06       0
#XS Ineff= 2 , 0
          367.67 1696.36
Permanent Ineff=
       F       F
Bank Sta=431.9,458.7
XS Rating Curve= 0 ,0
Exp/Cntr=0.3,0.1

Type RM Length L Ch R = 1 ,30363.7 ,635.3,645.5,655.4
XS GIS Cut Line= 3
     2052021.703      181206.996     2052071.182      181568.975
     2052816.082      182331.504
#Sta/Elev= 30
       0 1724.73    58.7 1712.88      75 1707.29   101.1  1695.3   117.4 1689.52
   133.7 1686.81  149.851686.362   663.8 1681.66   857.3 1682.05   890.1 1679.43
   906.5 1676.85   942.6 1675.18  952.32 1675.95   968.9 1678.89 1010.741678.596
  1037.7 1675.73  1077.1 1677.64 1111.151674.402  1113.2 1674.39  1116.5 1674.43
    1146 1674.88  1152.5 1678.16    11581682.883  1165.6 1688.99  1175.5 1693.08
    1182 1695.11 1192.021695.737  1218.1 1694.48  1233.6 1698.24  1431.3 1706.04
#Mann= 10 ,-1 , 0
       0     .12       0  149.85     .06       0  952.32     .12       0
 1010.74     .06       0 1111.15     .12       0  1116.5    .045       0
    1146     .12       0    1158     .06       0 1192.02    .016       0
  1233.6     .06       0
Bank Sta=1116.5,1146
XS Rating Curve= 0 ,0
Exp/Cntr=0.3,0.1

Type RM Length L Ch R = 1 ,29718.2 ,102.1,103.5,104.9
XS GIS Cut Line= 4
     2051787.437      181849.733      2052000.11      182188.275
     2052169.381      182665.705     2052351.673      182880.549
#Sta/Elev= 30
       0  1685.9   131.1 1682.64   383.4 1678.41   422.7 1676.51   461.9  1675.9
   494.6 1674.46   501.1 1673.73   517.4 1669.97   550.1 1668.97   559.9  1668.8
   576.3 1669.18   592.6 1673.16  632.061673.694  687.181674.149     707 1673.81
  727.45 1675.07   749.5 1677.93  766.241681.065  774.271681.726  854.461682.843
   876.9 1683.32   906.4  1681.7   922.7 1681.96   942.4 1683.64   968.6  1682.9
 1005.881683.282  1024.3 1682.93  1093.1 1686.65  1158.6 1688.16  1188.1 1687.83
#Mann= 10 ,-1 , 0
       0     .06       0   550.1    .045       0   576.3     .06       0
  632.06    .016       0  687.18     .12       0  727.45     .06       0
  766.24     .12       0  774.27     .06       0  854.46    .016       0
 1005.88     .06       0
#XS Ineff= 2 , 0
          478.24 1679.11
Permanent Ineff=
       F       F
Bank Sta=550.1,576.3
XS Rating Curve= 0 ,0
Exp/Cntr=0.3,0.1

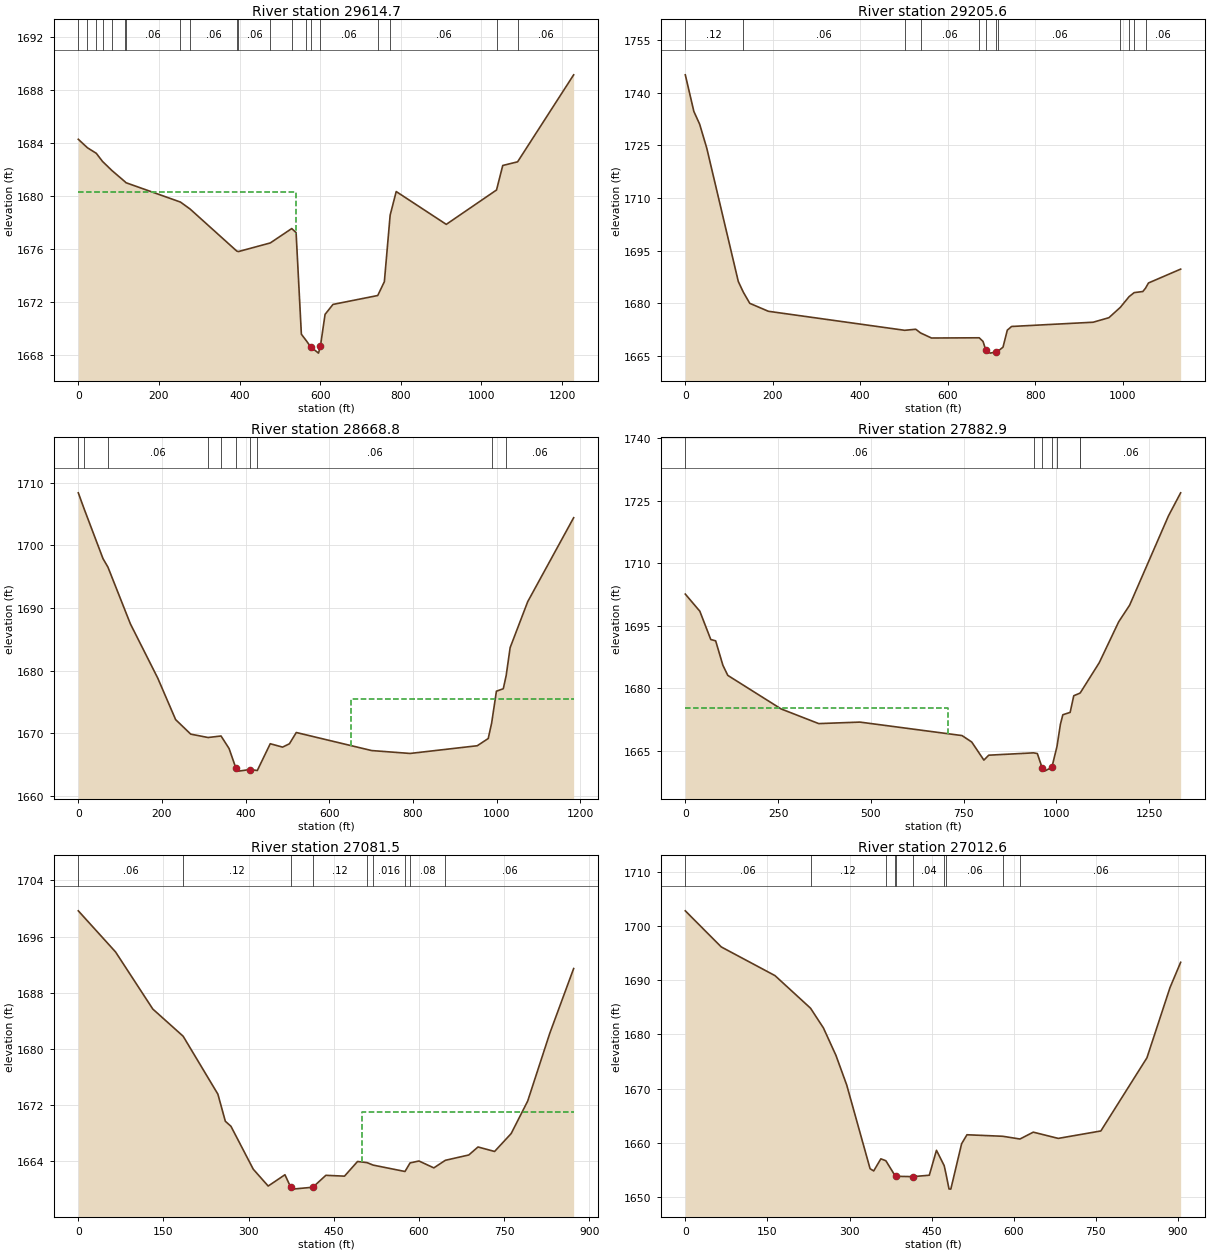
Type RM Length L Ch R = 1 ,29614.7 ,426.5,409.1,390.7
XS GIS Cut Line= 4
     2051709.312      181901.817     2051921.985      182240.358
     2052091.256      182717.789     2052319.989      182945.219
#Sta/Elev= 30
       0 1684.29   22.741683.646   44.691683.228   60.071682.615   83.35 1681.93
  115.59 1681.09  118.231681.008  253.321679.546  277.241679.021  393.22 1675.84
  397.311675.805  476.281676.456   529.51677.543   540.3 1677.24   553.4 1669.56
  566.091669.051   576.3 1668.61   595.9 1668.13  600.62 1668.65   612.2 1671.06
   631.8 1671.81  742.861672.484   759.3 1673.53  773.661678.559   788.7 1680.34
   912.9 1677.86 1037.571680.458    1053 1682.31 1089.831682.586  1228.9 1689.16
#Mann= 20 ,-1 , 0
       0     .06       0   22.74     .12       0   44.69     .06       0
   60.07     .12       0   83.35     .06       0  115.59     .12       0
  118.23     .06       0  253.32     .12       0  277.24     .06       0
  393.22     .12       0  397.31     .06       0  476.28    .016       0
   529.5     .12       0  566.09     .08       0   576.3    .045       0
  600.62     .06       0  742.86     .12       0  773.66     .06       0
 1037.57    .016       0 1089.83     .06       0
#XS Ineff= 2 , 0
          540.53 1680.27
Permanent Ineff=
       F       F
Bank Sta=576.3,600.62
XS Rating Curve= 0 ,0
Exp/Cntr=0.3,0.1

Type RM Length L Ch R = 1 ,29205.6 ,540.6,536.8,533.2
XS GIS Cut Line= 4
     2051290.041      182548.952     2051470.162      182546.782
     2052198.786      182946.579     2052318.578      182967.413
#Sta/Elev= 30
       0 1745.12    19.6 1734.68    32.8 1731.05    49.1 1724.21   121.2  1686.2
  132.611683.173   147.4 1679.97     190  1677.7  501.691672.277     527 1672.58
   538.11671.516     563 1670.08   672.11670.143   680.8 1669.12   687.3 1666.64
   697.1 1665.77   710.2 1666.09  715.991666.401   726.6 1667.48   736.4 1672.32
   746.2 1673.37   932.7 1674.58   968.7 1675.87  994.711678.802 1014.871681.872
 1026.521683.022  1046.4 1683.34 1052.511684.295  1059.2 1685.77  1132.8 1689.72
#Mann= 12 ,-1 , 0
       0     .12       0  132.61     .06       0  501.69    .016       0
   538.1     .06       0   672.1     .12       0   687.3    .045       0
   710.2     .12       0  715.99     .06       0  994.71     .08       0
 1014.87     .06       0 1026.52    .016       0 1052.51     .06       0
Bank Sta=687.3,710.2
XS Rating Curve= 0 ,0
Exp/Cntr=0.3,0.1

Type RM Length L Ch R = 1 ,28668.8 ,772.2,785.9,798.6
XS GIS Cut Line= 3
     2051243.057      183081.996     2052217.016      183433.558
     2052365.453      183438.767
#Sta/Elev= 30
       0 1708.37   13.411705.903      59 1697.88   70.781696.528   124.5 1687.47
     190  1678.8   232.6  1672.2   268.7 1669.88  310.291669.341  341.181669.583
   360.4 1667.58   376.8 1664.43   383.4 1663.98   409.6 1664.23  427.871664.084
   458.8 1668.35   488.2 1667.81   504.6 1668.34     521 1670.14   701.2 1667.26
     793  1666.8   953.6 1668.03   979.8 1669.18  987.941671.635   999.4 1676.73
  1015.8 1677.12 1022.68 1679.21  1032.2 1683.68  1074.2 1691.01    1184  1704.4
#Mann= 10 ,-1 , 0
       0     .06       0   13.41     .12       0   70.78     .06       0
  310.29    .016       0  341.18     .06       0   376.8    .045       0
   409.6     .08       0  427.87     .06       0  987.94    .016       0
 1022.68     .06       0
#XS Ineff= 2 , 0
                          651.89         1675.54
Permanent Ineff=
       F       F
Bank Sta=376.8,409.6
XS Rating Curve= 0 ,0
Exp/Cntr=0.3,0.1

Type RM Length L Ch R = 1 ,27882.9 ,801.8,801.5,800.4
XS GIS Cut Line= 3
     2051108.183      183413.969     2051576.933      183459.108
       2052118.6      184132.719
#Sta/Elev= 30
       0 1702.57    39.2 1698.46    68.7 1691.68    81.8 1691.37   101.4  1685.5
   114.5 1683.09   258.4 1675.04   359.7 1671.53   470.9 1671.89     746 1668.66
   772.1 1667.12   804.9 1662.78     818 1663.96  938.861664.521     949 1664.35
     962 1660.92   968.6 1660.14   988.2 1661.06 1001.991666.078  1011.2 1671.38
  1017.7 1673.65  1037.4 1674.22  1047.2 1678.21 1062.971678.795 1064.87 1678.92
  1115.9 1686.13  1168.3 1695.93  1197.8 1699.92  1302.6 1721.34  1335.3 1726.84
#Mann= 7 ,-1 , 0
       0     .06       0  938.86     .12       0     962    .045       0
   988.2     .12       0 1001.99    .016       0 1062.97     .12       0
 1064.87     .06       0
#XS Ineff= 2 , 0
           709.1 1675.17
Permanent Ineff=
       F       F
Bank Sta=962,988.2
XS Rating Curve= 0 ,0
Exp/Cntr=0.3,0.1

Type RM Length L Ch R = 1 ,27081.5 ,69.6,68.9,69.2
XS GIS Cut Line= 3
     2050910.266      183851.469       2051306.1      184341.053
     2051521.378        184453.9
#Sta/Elev= 30
       0 1699.67    65.6 1693.81   131.2 1685.67  184.711681.789   245.9 1673.53
     259 1669.67   268.9 1668.95   308.2 1662.83   334.5 1660.43     364 1662.04
   373.8 1660.33   377.1 1659.99   413.2 1660.26   436.1 1661.96   468.9 1661.84
   491.9 1663.93  508.471663.773  519.391663.415  575.451662.505  584.441663.724
   600.1    1664   626.3 1663.02   646.6  1664.1   687.9 1664.86   704.1    1666
   733.3 1665.36   762.5 1667.91   791.6 1672.54   830.5  1682.2   872.6 1691.44
#Mann= 9 ,-1 , 0
       0     .06       0  184.71     .12       0   373.8    .045       0
   413.2     .12       0  508.47     .06       0  519.39    .016       0
  575.45     .12       0  584.44     .08       0   646.6     .06       0
#XS Ineff= 2 , 0
                          500.28         1671.01
Permanent Ineff=
       F       F
Bank Sta=373.8,413.2
XS Rating Curve= 0 ,0
Exp/Cntr=0.3,0.1

Type RM Length L Ch R = 1 ,27012.6 ,461.8,429.6,395.7
XS GIS Cut Line= 3
     2050842.558      183884.455      2051267.56      184383.529
     2051484.919      184505.983
#Sta/Elev= 30
       0 1702.77    65.6 1696.13   163.9 1690.84  228.831684.841   252.4  1681.2
   275.3 1676.14     295 1670.67   337.6 1655.29   344.2 1654.88   357.3 1657.11
  366.441656.756  383.661653.934   384.8 1653.89   416.2 1653.83   445.8 1654.09
   458.9 1658.68  473.011655.843  476.011654.474   481.8 1651.56   485.1 1651.53
   504.8 1659.88   514.6 1661.54  580.09 1661.26  611.451660.757   635.8 1662.02
   681.4 1660.87   759.2 1662.24   843.4 1675.71   885.6 1688.65     905 1693.29
#Mann= 10 ,-1 , 0
       0     .06       0  228.83     .12       0  366.44     .04       0
  383.66     .06       0   384.8    .045       0   416.2     .04       0
  473.01     .12       0  476.01     .06       0  580.09    .016       0
  611.45     .06       0
Bank Sta=384.8,416.2
XS Rating Curve= 0 ,0
Exp/Cntr=0.3,0.1

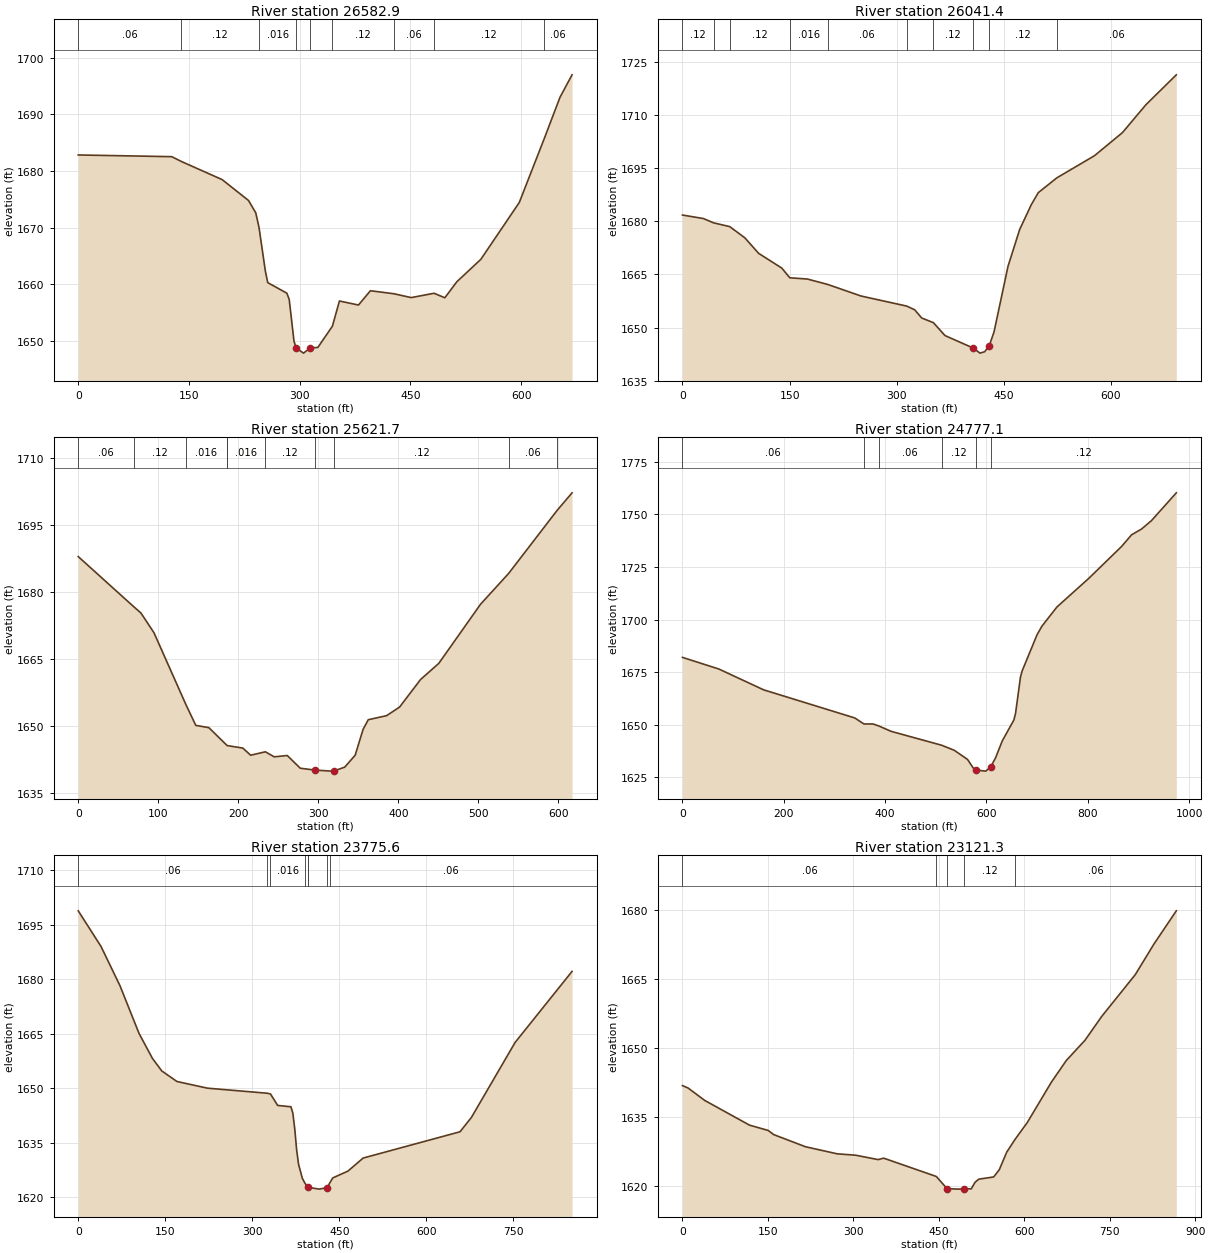
Type RM Length L Ch R = 1 ,26582.9 ,498.7,541.6,583.8
XS GIS Cut Line= 4
     2050858.183      184488.622     2051113.391        184516.4
     2051236.655      184433.067     2051467.558      184559.803
#Sta/Elev= 30
       0 1682.82   126.7 1682.52  139.641681.676     195 1678.47   230.7 1674.79
   240.5 1672.61  244.861670.062   253.5 1662.33   256.7 1660.31   282.6 1658.45
   285.8 1657.34   292.3 1649.95   295.5 1648.75   305.2 1647.88   314.1 1648.78
   324.6 1648.89  344.321652.635   353.8 1657.07   379.6 1656.36   395.8 1658.88
  427.561658.352     451 1657.67  482.021658.436   496.6 1657.64   512.8 1660.46
   545.3 1664.41   597.4 1674.43  631.471685.779   652.6    1693   668.9 1696.95
#Mann= 9 ,-1 , 0
       0     .06       0  139.64     .12       0  244.86    .016       0
   295.5    .045       0   314.1    .016       0  344.32     .12       0
  427.56     .06       0  482.02     .12       0  631.47     .06       0
Bank Sta=295.5,314.1
XS Rating Curve= 0 ,0
Exp/Cntr=0.3,0.1

Type RM Length L Ch R = 1 ,26041.4 ,419.8,419.7,419.2
XS GIS Cut Line= 4
     2050881.078      184529.913      2051007.46      184608.418
     2051122.072      184976.469     2051247.072      185071.955
#Sta/Elev= 30
       0 1681.77    29.1 1680.79   43.631679.566   66.191678.501    87.3 1675.35
   106.7 1670.95   139.1  1666.8  150.291664.058   174.9 1663.71  203.231662.195
     250 1658.92  314.091656.073   325.2 1655.03     335 1652.72  351.461651.385
   367.7 1647.75   406.9 1644.26   416.7  1642.8   423.2 1643.19   429.7 1644.95
   436.3 1648.76   455.9  1667.3   472.2 1677.67   488.5 1684.69   498.3 1688.08
  524.281692.263   576.9  1698.5   616.2 1705.04     649 1712.89   691.6 1721.34
#Mann= 10 ,-1 , 0
       0     .12       0   43.63     .06       0   66.19     .12       0
  150.29    .016       0  203.23     .06       0  314.09    .016       0
  351.46     .12       0   406.9    .045       0   429.7     .12       0
  524.28     .06       0
Bank Sta=406.9,429.7
XS Rating Curve= 0 ,0
Exp/Cntr=0.3,0.1

Type RM Length L Ch R = 1 ,25621.7 ,843.2,844.6,844.3
XS GIS Cut Line= 2
     2050590.822      184690.011     2050781.794      185276.817
#Sta/Elev= 30
       0  1687.9   69.561676.646    78.4 1675.26    94.7 1670.83  134.391654.828
   146.9  1650.1   163.2 1649.59     1861645.591  186.251645.571   205.7 1645.01
   215.5 1643.41   233.91644.182   244.9 1643.05   261.2 1643.35   277.5  1640.5
     296 1640.08   316.7 1639.85     320 1639.92     333 1640.74   346.1 1643.42
   355.9 1649.17   362.4 1651.36   385.3 1652.27   401.6  1654.2   427.7 1660.35
   450.6 1663.99   502.8 1677.24  537.89 1684.13  598.251698.205   617.1 1702.18
#Mann= 10 ,-1 , 0
       0     .06       0   69.56     .12       0  134.39    .016       0
     186     .12       0  186.25    .016       0   233.9     .12       0
     296    .045       0     320     .12       0  537.89     .06       0
  598.25     .12       0
Bank Sta=296,320
XS Rating Curve= 0 ,0
Exp/Cntr=0.3,0.1

Type RM Length L Ch R = 1 ,24777.1 ,1006.7,1001.5,994.4
XS GIS Cut Line= 3
     2049960.614      184700.775     2049849.828      185097.621
     2050015.301      185635.671
#Sta/Elev= 30
       0 1682.08    71.9 1676.54   160.2 1666.66   340.1  1653.3   358.31650.425
     376 1650.45  387.391649.503     412 1646.92  511.591640.332   536.4 1637.94
   562.6 1633.61   575.7 1628.94   578.9 1628.55   598.6 1628.02   608.4 1629.98
   618.2  1634.4   631.3 1642.37   654.2 1652.31   657.5 1655.39   667.3 1672.78
   670.6 1675.66     700 1692.85   709.8 1696.97   739.3 1706.05   801.5  1719.5
   866.9  1734.8   886.6 1740.34   906.2 1743.07   925.8 1747.06   974.9 1760.29
#Mann= 6 ,-1 , 0
       0     .06       0   358.3    .016       0  387.39     .06       0
  511.59     .12       0   578.9    .045       0   608.4     .12       0
Bank Sta=578.9,608.4
XS Rating Curve= 0 ,0
Exp/Cntr=0.3,0.1

Type RM Length L Ch R = 1 ,23775.6 ,660,654.4,648.4
XS GIS Cut Line= 2
     2048757.489      185094.004     2049213.218      185812.754
#Sta/Elev= 30
       0 1698.79    39.3 1688.98      72 1678.17   104.7 1665.09   127.7 1658.24
     144 1654.73   170.2 1651.83   222.6    1650  325.91  1648.6  331.321648.402
   343.7 1645.25   366.6 1644.88   369.9 1643.09   373.2 1638.71   376.4 1633.02
   379.7 1629.05   386.2 1625.21  390.641623.867  395.861622.758   396.1 1622.71
   415.7 1622.22   428.8 1622.66  433.431623.905   438.6  1625.3   464.8 1627.18
     491 1630.77   657.9    1638   677.6 1641.95   752.8 1662.56     851 1682.13
#Mann= 8 ,-1 , 0
       0     .06       0  325.91     .12       0  331.32    .016       0
  390.64     .12       0  395.86     .08       0   396.1    .045       0
   428.8     .08       0  433.43     .06       0
Bank Sta=396.1,428.8
XS Rating Curve= 0 ,0
Exp/Cntr=0.3,0.1

Type RM Length L Ch R = 1 ,23121.3 ,381.5,393.1,404
XS GIS Cut Line= 3
     2048302.953      185511.683     2048328.995      185722.621
     2048806.968      186169.525
#Sta/Elev= 30
       0 1641.83     9.8  1641.3    39.2 1638.59   117.7 1633.23   150.4 1632.08
   160.2 1631.17   215.8 1628.54   271.4    1627   304.2 1626.69   343.4 1625.74
   353.2 1626.05  445.531622.074   464.5 1619.42   484.1 1619.32   493.9 1619.38
     507 1619.38   513.5  1620.8   520.1 1621.48   546.3 1621.97   556.1 1623.53
   569.2 1627.36  583.931630.152   605.2 1633.78   647.7 1642.59   673.9  1647.3
   706.6 1651.68     736 1656.87   794.9 1665.95   827.6 1672.59   866.9 1679.82
#Mann= 5 ,-1 , 0
       0     .06       0  445.53     .08       0   464.5    .045       0
   493.9     .12       0  583.93     .06       0
Bank Sta=464.5,493.9
XS Rating Curve= 0 ,0
Exp/Cntr=0.3,0.1

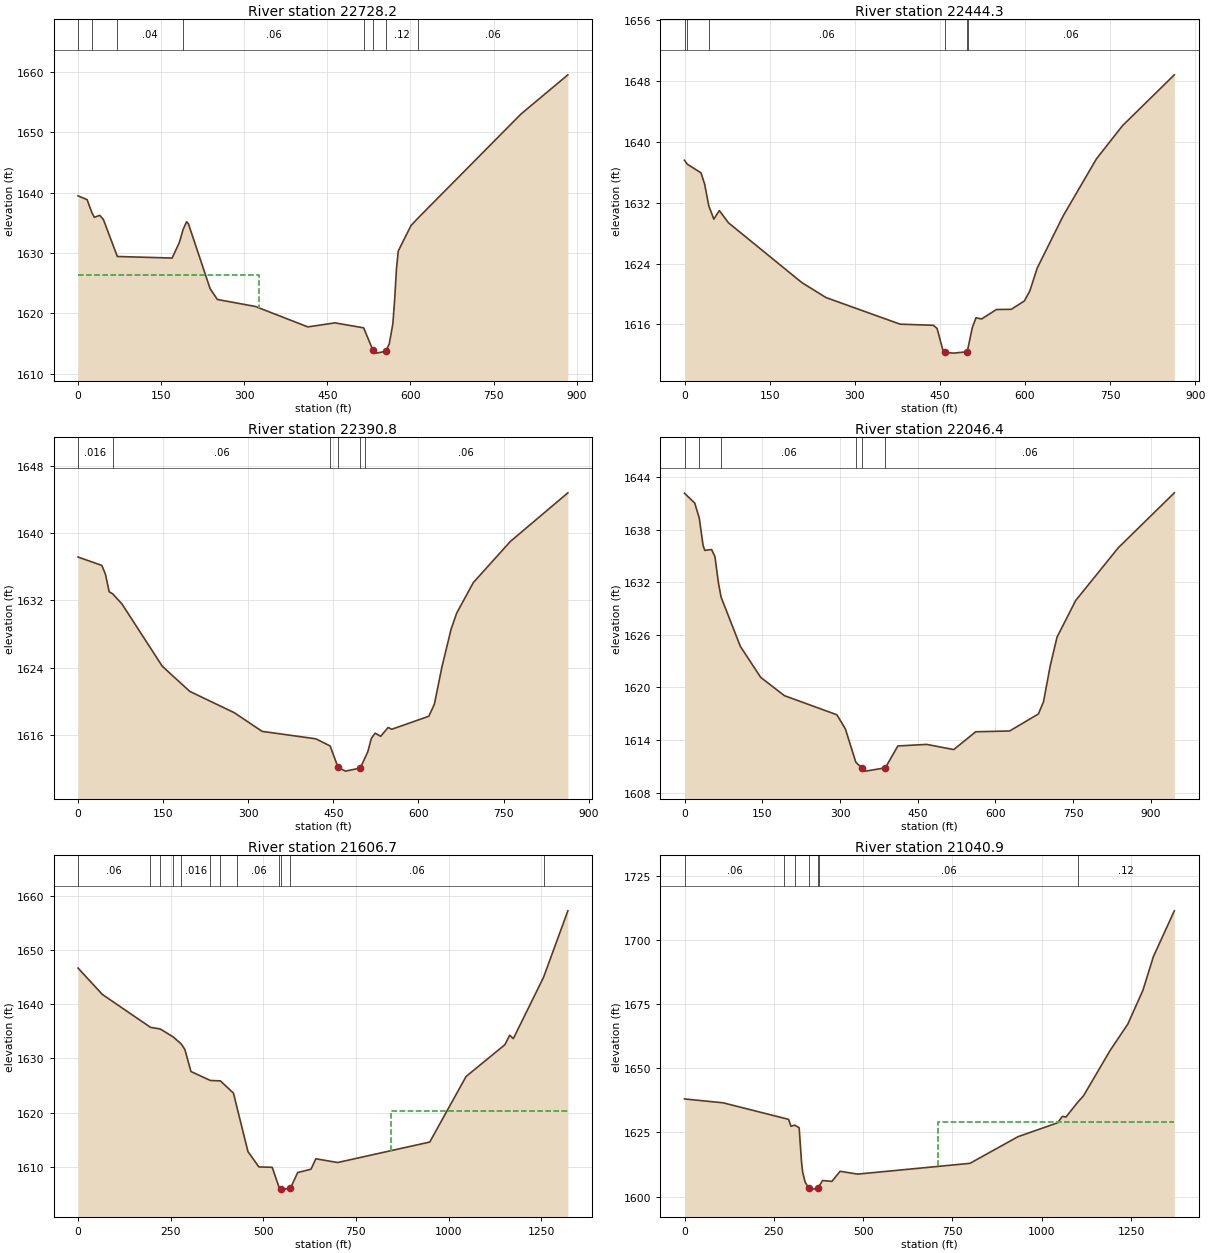
Type RM Length L Ch R = 1 ,22728.2 ,287.6,283.8,280.5
XS GIS Cut Line= 3
     2048042.536      185597.621     2048245.661      186235.642
     2048370.661      186410.121
#Sta/Elev= 30
       0 1639.48    16.3 1638.86   24.981636.704    29.4 1635.92    39.2 1636.24
    45.7 1635.57   70.981629.419   169.8 1629.16   182.9 1631.74  189.781633.922
     196 1635.19   199.2 1634.86   238.4 1624.09   251.5 1622.29   320.1 1621.13
   414.8 1617.74   463.8 1618.41  515.611617.584   532.4 1613.85   538.9 1613.39
   555.3  1613.7   561.8 1614.92   568.3 1618.27   571.6 1622.35   574.8  1627.4
   578.1 1630.34     601 1634.54  613.431635.763   799.7 1653.06   884.2 1659.55
#Mann= 8 ,-1 , 0
       0    .016       0   24.98     .06       0   70.98     .04       0
  189.78     .06       0  515.61     .12       0   532.4    .045       0
   555.3     .12       0  613.43     .06       0
#XS Ineff= 2 , 0
           327.3 1626.43
Permanent Ineff=
       F       F
Bank Sta=532.4,555.3
XS Rating Curve= 0 ,0
Exp/Cntr=0.3,0.1

Type RM Length L Ch R = 1 ,22444.3 ,53.5,53.5,53.5
XS GIS Cut Line= 3
     2047775.718      185719.004      2047801.76      185914.317
     2048109.051      186505.462
#Sta/Elev= 30
       0  1637.6     4.7 1637.09    29.1 1635.94    35.5 1634.46   42.811631.605
    51.7 1629.85    61.4 1630.98    77.5 1629.37   206.8 1621.51   249.3 1619.54
   379.9 1616.04   438.7 1615.89   445.2 1615.47     455 1612.72   458.3 1612.33
   474.6 1612.23   497.5 1612.41  498.971612.642   507.3  1615.6   513.8 1616.88
   523.6 1616.72   549.8 1617.97   575.9 1617.99   598.8 1619.08   608.5 1620.38
   621.6 1623.41   667.3 1630.27   726.1 1637.79   771.8 1642.13   863.3 1648.83
#Mann= 6 ,-1 , 0
       0     .06       0     4.7    .016       0   42.81     .06       0
   458.3    .045       0   497.5     .08       0  498.97     .06       0
Bank Sta=458.3,497.5
XS Rating Curve= 0 ,0
Exp/Cntr=0.3,0.1

Type RM Length L Ch R = 1 ,22390.8 ,352.2,344.4,336.5
XS GIS Cut Line= 3
     2047726.239      185739.837      2047752.28       185935.15
     2048059.572      186526.296
#Sta/Elev= 30
       0 1637.17      42 1636.17    48.4  1635.1    54.9 1633.03   60.961632.792
    77.5 1631.57   148.6 1624.15     197 1621.16   275.4 1618.62   324.4  1616.4
   419.1 1615.51  444.371614.654   458.3  1612.1   471.4 1611.66   497.5 1612.03
  504.881613.112   510.6 1613.95   517.1 1615.59   523.6 1616.18   533.4 1615.81
   546.5 1616.86     553 1616.65   618.3  1618.2   628.1 1619.65   641.2 1624.03
   657.5 1628.58   667.3 1630.48   696.7 1634.13     762 1639.03   863.3 1644.82
#Mann= 6 ,-1 , 0
       0    .016       0   60.96     .06       0  444.37     .08       0
   458.3    .045       0   497.5     .08       0  504.88     .06       0
Bank Sta=458.3,497.5
XS Rating Curve= 0 ,0
Exp/Cntr=0.3,0.1

Type RM Length L Ch R = 1 ,22046.4 ,441.8,439.7,437.5
XS GIS Cut Line= 3
     2047292.536      186071.579     2047821.182      186558.558
     2048029.516        186647.1
#Sta/Elev= 30
       0 1642.14    19.6 1641.04   28.511639.316    35.9 1636.17    39.2 1635.62
    52.3 1635.72    58.8  1634.9    65.3 1631.98   70.581630.294   107.8 1624.67
     147 1621.14   192.8 1619.05     294 1616.87   310.4 1615.26  330.621611.445
     343 1610.77   349.6 1610.44   387.6 1610.82   411.6 1613.31   467.2 1613.49
   519.5  1612.9   561.9 1614.93   627.3 1615.02   682.8 1616.96   692.6 1618.33
   705.7 1622.47   718.8 1625.73   754.8 1629.91   836.9 1635.92   945.1 1642.19
#Mann= 6 ,-1 , 0
       0     .06       0   28.51    .016       0   70.58     .06       0
  330.62     .08       0     343    .045       0   387.6     .06       0
Bank Sta=343,387.6
XS Rating Curve= 0 ,0
Exp/Cntr=0.3,0.1

Type RM Length L Ch R = 1 ,21606.7 ,579.4,565.8,551.7
XS GIS Cut Line= 4
      2047063.37      186225.225     2047209.203      186608.038
     2047701.391      186930.954     2048024.307      186954.392
#Sta/Elev= 30
       0 1646.64    65.5 1641.79  195.551635.729  221.881635.426  256.731633.973
  278.511632.666   288.4 1631.64   304.8 1627.59  357.371625.935  384.331625.862
   419.5 1623.61  430.231620.644   458.7 1612.84   488.1 1610.02   524.1 1609.95
  543.75 1606.03     547    1606   553.5 1605.93   573.2 1606.08   592.8 1608.98
   628.8  1609.6   641.8 1611.52   700.7 1610.83   949.3  1614.6  1047.4 1626.68
    1152 1632.52  1165.1 1634.27  1174.9 1633.65 1256.351644.921  1322.1 1657.18
#Mann= 12 ,-1 , 0
       0     .06       0  195.55     .08       0  221.88     .06       0
  256.73     .08       0  278.51    .016       0  357.37     .06       0
  384.33     .12       0  430.23     .06       0  543.75     .08       0
     547    .045       0   573.2     .06       0 1256.35     .12       0
#XS Ineff= 2 , 0
                          843.64         1620.29
Permanent Ineff=
       F       F
Bank Sta=547,573.2
XS Rating Curve= 0 ,0
Exp/Cntr=0.3,0.1

Type RM Length L Ch R = 1 ,21040.9 ,420.9,422.2,423.3
XS GIS Cut Line= 3
     2046765.735      187125.688     2047881.187      187177.771
     2048111.221      187286.278
#Sta/Elev= 30
       0 1638.09   108.1 1636.58   278.91630.569   291.4 1630.11     298 1627.42
  308.47 1627.88   320.9 1626.86   327.5 1613.63   330.7 1609.52   337.3 1605.81
   347.1 1603.38   360.2 1602.91   373.3 1603.42  377.181604.142   386.4 1606.27
   412.6 1605.94   435.5 1609.87   484.6 1608.77     799 1612.97   933.3 1623.36
  1044.6  1628.8  1057.7 1631.31  1067.6 1631.01 1100.011636.718  1116.7 1639.29
  1191.7 1657.11  1240.6 1667.24    1283 1680.44  1312.3 1693.59    1371 1711.47
#Mann= 7 ,-1 , 0
       0     .06       0   278.9    .016       0  308.47     .12       0
   347.1    .045       0   373.3     .12       0  377.18     .06       0
 1100.01     .12       0
#XS Ineff= 2 , 0
                          710.68         1629.14
Permanent Ineff=
       F       F
Bank Sta=347.1,373.3
XS Rating Curve= 0 ,0
Exp/Cntr=0.3,0.1

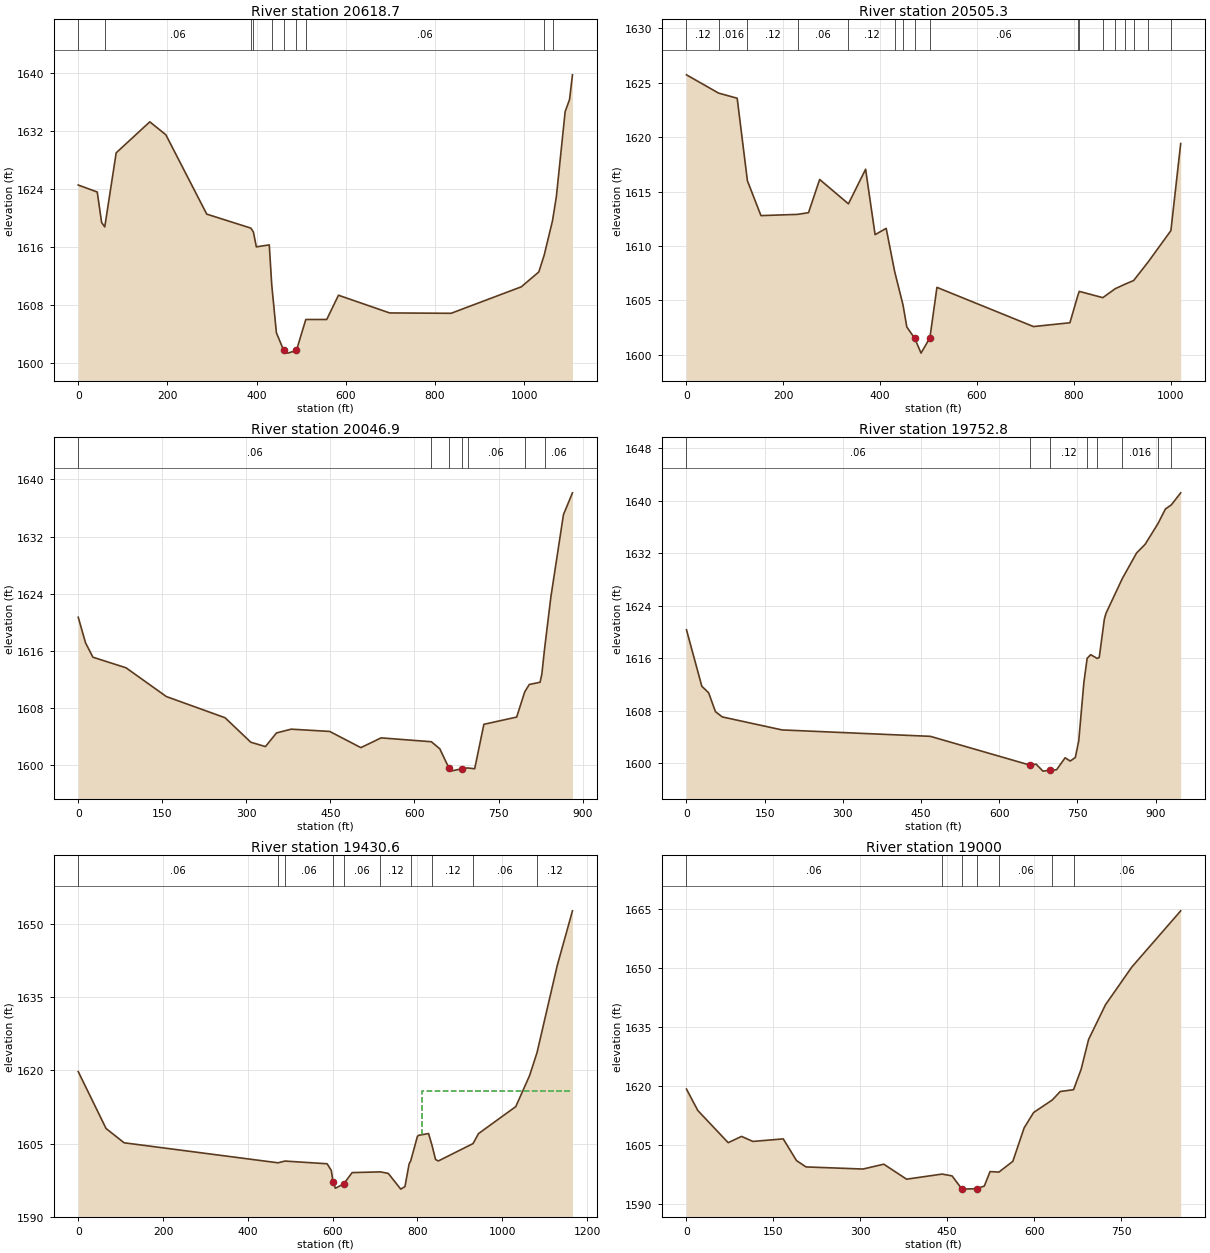
Type RM Length L Ch R = 1 ,20618.7 ,112.7,113.3,114.1
XS GIS Cut Line= 4
     2046653.756      187512.841     2047057.402      187557.112
     2047175.349      187568.975     2047576.391      187993.454
#Sta/Elev= 30
       0  1624.5    42.6 1623.54    52.4 1619.34   59.471618.728    85.1 1628.94
   160.5 1633.21   196.5 1631.43   288.2 1620.49  387.081618.563   392.91618.024
   399.5 1615.98   428.5 1616.25  434.05 1610.73   444.5 1604.13   460.5 1601.77
   470.1 1601.33   489.4  1601.7  510.431605.963   557.4 1605.97   583.7 1609.31
   698.5 1606.87   836.3 1606.82   993.8 1610.47  1033.1 1612.52 1045.171614.839
 1063.891619.601  1072.5 1622.92  1092.2 1634.62    1102 1636.28  1108.6 1639.69
#Mann= 10 ,-1 , 0
       0     .12       0   59.47     .06       0  387.08     .08       0
   392.9    .016       0  434.05     .12       0   460.5    .045       0
   489.4     .12       0  510.43     .06       0 1045.17     .12       0
 1063.89     .06       0
Bank Sta=460.5,489.4
XS Rating Curve= 0 ,0
Exp/Cntr=0.3,0.1

Type RM Length L Ch R = 1 ,20505.3 ,465.5,458.4,451.5
XS GIS Cut Line= 3
     2046653.756      187614.403     2047211.807      187688.767
      2047500.11      188044.091
#Sta/Elev= 30
       0 1625.72   66.211624.043   104.7 1623.57  125.811615.992   153.8 1612.79
  229.321612.903     252 1613.06     275 1616.11  334.411613.874   369.9 1617.05
   389.5 1611.04   412.4 1611.62  429.781607.678  447.141604.586     455 1602.56
   471.3 1601.52   484.4 1600.16   502.7 1601.57   517.2  1606.2   716.6  1602.6
   791.8 1602.95  808.281605.463  811.181605.832  859.711605.255  885.311606.075
  906.591606.511  923.351606.825  953.471608.536 1000.351611.412  1020.6 1619.41
#Mann= 17 ,-1 , 0
       0     .12       0   66.21    .016       0  125.81     .12       0
  229.32     .06       0  334.41     .12       0  429.78     .06       0
  447.14     .12       0   471.3    .045       0   502.7     .06       0
  808.28     .12       0  811.18     .06       0  859.71     .08       0
  885.31     .06       0  906.59    .016       0  923.35     .08       0
  953.47    .016       0 1000.35     .12       0
Bank Sta=471.3,502.7
XS Rating Curve= 0 ,0
Exp/Cntr=0.3,0.1

Type RM Length L Ch R = 1 ,20046.9 ,294.5,294.1,289.8
XS GIS Cut Line= 3
     2046677.194      188145.653     2047427.194      188023.258
     2047528.756      188090.966
#Sta/Elev= 30
       0 1620.69    13.1 1617.09    26.2 1615.09    85.2 1613.61   157.2 1609.58
     262 1606.61   307.9 1603.18   334.1 1602.57   353.8 1604.48     380 1605.01
   448.8 1604.69   504.4 1602.42   540.5 1603.79  630.241603.246   645.3 1602.25
   661.7 1599.54   664.9 1599.13   684.9 1599.47  695.071599.576   707.5 1599.46
   723.9 1605.69   782.4  1606.7  796.751610.222   804.9 1611.27   824.2 1611.58
   827.4 1612.75  832.251616.286   843.4 1623.49   865.9 1635.06     882 1638.12
#Mann= 7 ,-1 , 0
       0     .06       0  630.24     .12       0   661.7    .045       0
   684.9     .12       0  695.07     .06       0  796.75    .016       0
  832.25     .06       0
Bank Sta=661.7,684.9
XS Rating Curve= 0 ,0
Exp/Cntr=0.3,0.1

Type RM Length L Ch R = 1 ,19752.8 ,325,322.1,319.1
XS GIS Cut Line= 3
     2046726.673      188502.424     2047515.735      188286.278
     2047619.902      188208.153
#Sta/Elev= 30
       0 1620.31    29.4 1611.71    42.5 1610.71    55.6 1607.83    68.7 1607.03
   183.3 1605.05     468 1604.07   658.9 1599.69   670.9 1599.83     684 1598.77
     697  1598.9   710.1 1598.98   726.5  1600.8   736.3 1600.31   746.1 1600.85
   752.7  1603.4   762.5 1612.27  768.781615.959   775.6 1616.52  788.171615.935
     792  1616.1   801.8 1621.94     805 1622.83  836.281628.122   863.7 1632.02
     880 1633.33  904.491636.465     919 1638.72  930.371639.349   948.3 1641.18
#Mann= 8 ,-1 , 0
       0     .06       0   658.9    .045       0     697     .12       0
  768.78    .016       0  788.17     .12       0  836.28    .016       0
  904.49     .12       0  930.37    .016       0
Bank Sta=658.9,697
XS Rating Curve= 0 ,0
Exp/Cntr=0.3,0.1

Type RM Length L Ch R = 1 ,19430.6 ,431.6,430.6,428.5
XS GIS Cut Line= 3
     2046872.506      188859.195     2047690.214      188528.466
     2047935.006      188671.695
#Sta/Elev= 30
       0 1619.76    65.6  1608.1   108.2 1605.17  471.181601.067  487.541601.424
     587 1600.87   596.8 1599.51   601.2 1597.07   606.6 1595.85   626.3 1596.76
     646 1599.06  712.851599.207   731.2  1598.9   760.7 1595.67   770.6 1596.19
   780.4 1600.84  784.121601.448   800.1 1606.51   803.4 1606.71   826.3 1607.07
  834.861604.518   842.7 1601.75   849.3 1601.44   931.31605.016     944 1607.05
    1032 1612.59  1064.6 1618.96 1082.091623.655  1129.8 1641.52  1165.7 1652.73
#Mann= 10 ,-1 , 0
       0     .06       0  471.18     .12       0  487.54     .06       0
   601.2    .045       0   626.3     .06       0  712.85     .12       0
  784.12    .016       0  834.86     .12       0   931.3     .06       0
 1082.09     .12       0
#XS Ineff= 2 , 0
                          809.95         1615.83
Permanent Ineff=
       F       F
Bank Sta=601.2,626.3
XS Rating Curve= 0 ,0
Exp/Cntr=0.3,0.1

Type RM Length L Ch R = 1 ,19000   ,337.3,341.2,343.7
XS GIS Cut Line= 3
     2047153.756      189195.133     2047778.756      188924.299
     2047950.631      188929.508
#Sta/Elev= 30
       0 1619.18    19.6 1613.73      72 1605.55      95 1607.15   114.6 1605.87
     167 1606.52   189.9    1601   206.3 1599.39   304.6 1598.85   340.6 1600.08
   379.9 1596.27  441.26 1597.57   458.5  1597.1   474.8 1593.88   478.1 1593.74
     501 1593.86   514.1 1594.52     524  1598.2  539.341598.076   563.3 1600.81
   582.9 1609.34   599.3 1613.24  631.541616.422   645.1 1618.57  668.131619.023
   681.2 1624.21   694.1  1631.8   723.3 1640.64   768.8 1650.24   853.1 1664.52
#Mann= 7 ,-1 , 0
       0     .06       0  441.26     .12       0   474.8    .045       0
     501     .12       0  539.34     .06       0  631.54    .016       0
  668.13     .06       0
Bank Sta=474.8,501
XS Rating Curve= 0 ,0
Exp/Cntr=0.3,0.1