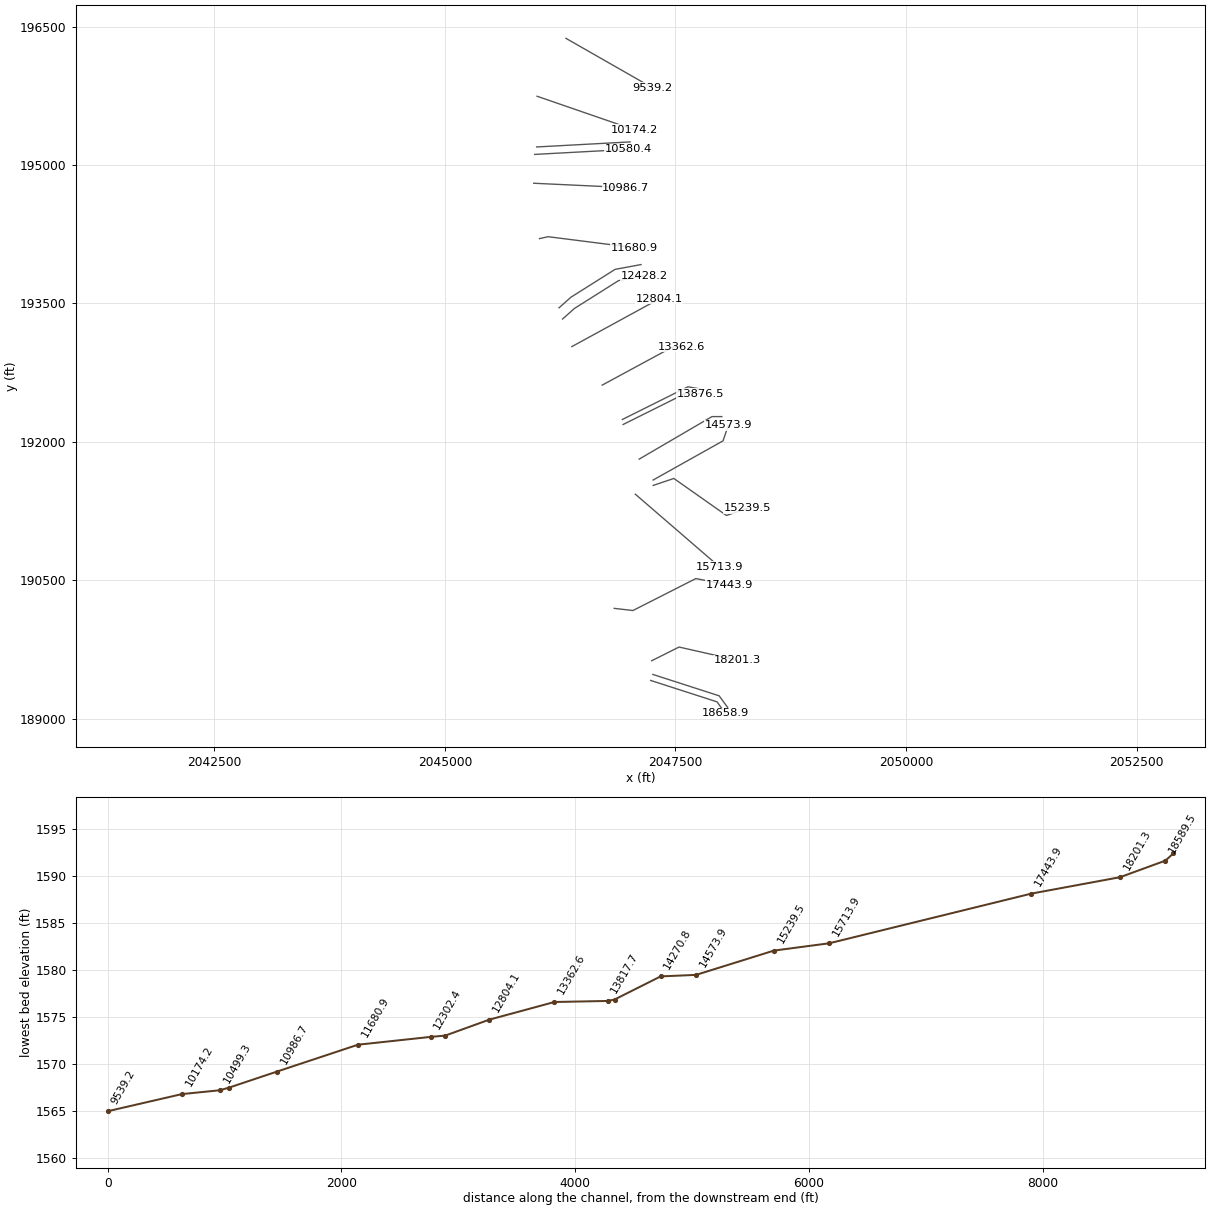
HEC-RAS study HNSCK.prj: HNSCK

--- HNSCK.g01 (geometry) --- (continued)

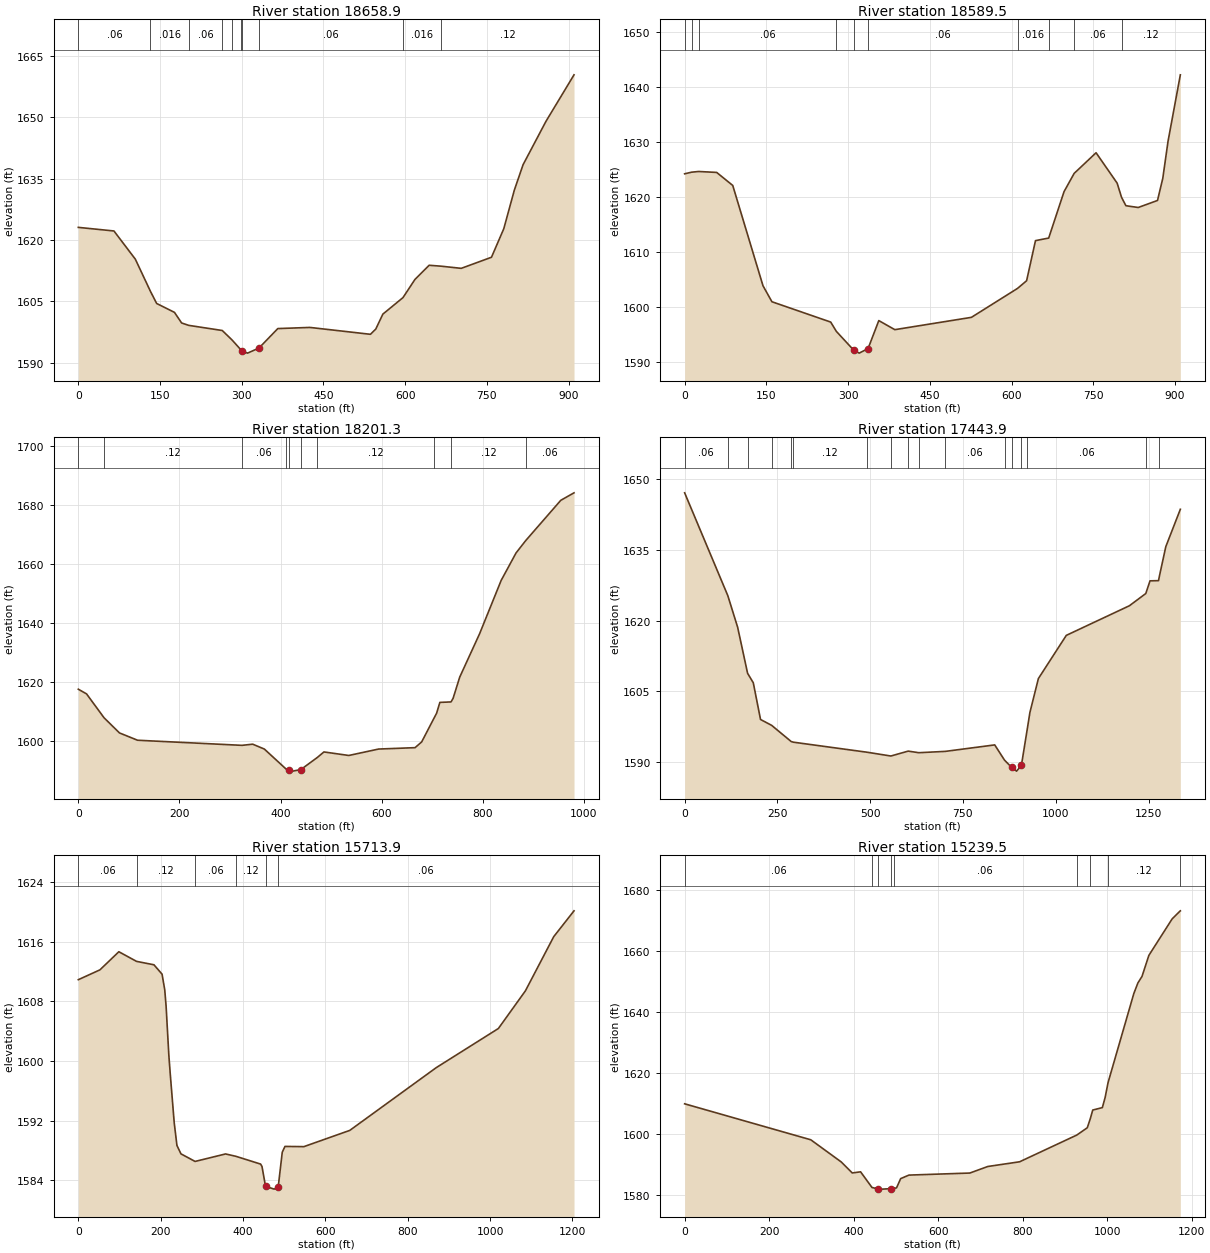
Type RM Length L Ch R = 1 ,18658.9 ,69.3,69.3,69.3
XS GIS Cut Line= 3
     2047231.881      189413.883     2047950.631      189182.112
     2048041.777      189057.112
#Sta/Elev= 30
       0  1623.1    65.4 1622.22   104.6 1615.34  132.381607.476   143.8  1604.5
   176.5 1602.33   189.6 1599.74  202.561599.155  264.16  1597.9   281.81595.638
  299.431593.033   300.8  1592.9   310.6 1592.37   331.6 1593.61   366.2 1598.37
     425 1598.65   536.2 1596.97     546 1598.25     559  1601.9  595.981605.942
   617.9 1610.38     644 1613.84  665.921613.616   702.9 1613.09   758.4  1615.8
     781 1622.78   800.3 1632.18   816.4 1638.42   858.3 1648.99   909.9 1660.38
#Mann= 10 ,-1 , 0
       0     .06       0  132.38    .016       0  202.56     .06       0
  264.16    .016       0   281.8     .08       0  299.43     .06       0
   300.8    .045       0   331.6     .06       0  595.98    .016       0
  665.92     .12       0
Bank Sta=300.8,331.6
XS Rating Curve= 0 ,0
Exp/Cntr=0.3,0.1

Type RM Length L Ch R = 1 ,18589.5 ,385.9,388.2,389.9
XS GIS Cut Line= 3
     2047255.319      189478.987     2047974.069      189247.216
     2048065.214      189122.216
#Sta/Elev= 30
       0 1624.23   12.731624.524   25.66 1624.65    58.8 1624.48    88.3 1622.11
   143.8 1603.86   160.2 1600.95   268.1 1597.25  278.511595.552   310.6 1592.11
   320.4  1591.6   336.7 1592.43   356.4 1597.52   385.8 1595.87   526.4 1598.11
  611.011603.375   627.7 1604.77     644 1612.07  668.251612.539   696.4 1620.98
  715.011624.308   755.2 1628.06   793.9 1622.53  801.981619.948     810 1618.42
   832.6  1618.1     868 1619.38   877.7 1623.42   887.3 1630.14   909.9 1642.24
#Mann= 10 ,-1 , 0
       0     .06       0   12.73     .08       0   25.66     .06       0
  278.51     .08       0   310.6    .045       0   336.7     .06       0
  611.01    .016       0  668.25     .12       0  715.01     .06       0
  801.98     .12       0
Bank Sta=310.6,336.7
XS Rating Curve= 0 ,0
Exp/Cntr=0.3,0.1

Type RM Length L Ch R = 1 ,18201.3 ,741.4,757.4,773
XS GIS Cut Line= 3
     2047242.298      189627.424     2047539.173      189775.862
     2048171.985      189632.633
#Sta/Elev= 30
       0 1617.63    16.3 1616.04   50.931607.937    81.4  1602.8   117.2 1600.32
  323.821598.585     345 1598.98     368 1597.33  411.29 1590.51   417.2 1590.06
   423.7 1589.84     440 1590.34  472.851594.475   485.9 1596.35   535.1 1595.15
   594.1 1597.33   666.2  1597.8   679.3 1599.75  702.741607.489   708.8 1609.47
   715.3 1613.16  737.391613.318   741.5 1614.56   754.6 1621.75     794 1636.49
   836.6 1654.56     866 1663.86  885.371668.103   954.5 1681.72   980.7 1684.26
#Mann= 10 ,-1 , 0
       0     .06       0   50.93     .12       0  323.82     .06       0
  411.29     .08       0   417.2    .045       0     440     .06       0
  472.85     .12       0  702.74    .016       0  737.39     .12       0
  885.37     .06       0
Bank Sta=417.2,440
XS Rating Curve= 0 ,0
Exp/Cntr=0.3,0.1

Type RM Length L Ch R = 1 ,17443.9 ,1754.2,1730,1702.1
XS GIS Cut Line= 4
     2046836.048      190195.133     2047039.173      190171.695
     2047721.464      190518.049     2048080.839      190447.737
#Sta/Elev= 30
       0  1647.1   116.31625.308   142.8 1618.61  169.621608.843     185 1606.82
   204.5 1599.05  234.421597.807  287.071594.376  292.941594.236  492.361592.099
  555.711591.301  602.231592.341  631.111592.005  702.531592.286   835.6 1593.66
  862.121590.416   881.4 1588.88   894.4  1588.1   907.5 1589.32  923.321597.032
   930.4 1600.53   953.3 1607.73  1028.5 1616.88  1198.5 1623.16 1242.691625.753
  1254.1 1628.44    1277 1628.48 1279.341629.416  1296.6 1635.68  1335.8 1643.61
#Mann= 17 ,-1 , 0
       0     .06       0   116.3     .12       0  169.62     .06       0
  234.42     .12       0  287.07     .06       0  292.94     .12       0
  492.36     .06       0  555.71     .08       0  602.23     .06       0
  631.11     .08       0  702.53     .06       0  862.12     .12       0
   881.4    .045       0   907.5     .12       0  923.32     .06       0
 1242.69    .016       0 1279.34     .06       0
Bank Sta=881.4,907.5
XS Rating Curve= 0 ,0
Exp/Cntr=0.3,0.1

Type RM Length L Ch R = 1 ,15713.9 ,471.6,474.4,477.3
XS GIS Cut Line= 2
     2047065.214      191432.112     2047976.673      190645.653
#Sta/Elev= 30
       0 1610.92    52.5 1612.24    98.4 1614.67  141.461613.377   183.7 1612.92
   203.4 1611.66   209.9 1609.56   213.2 1607.35   219.8 1600.83   223.1 1598.39
   232.9 1591.72   239.5 1588.68   249.3 1587.55  283.631586.536   357.6 1587.54
  382.491587.226   442.8 1586.18   446.1 1585.85  454.68  1583.2   475.6 1582.82
   485.5 1583.12   495.3 1587.77   501.9 1588.55   547.8 1588.52   659.3  1590.7
   869.3 1599.12  1020.2 1604.37  1085.8 1609.42  1154.6 1616.69  1203.9 1620.16
#Mann= 6 ,-1 , 0
       0     .06       0  141.46     .12       0  283.63     .06       0
  382.49     .12       0  454.68    .045       0   485.5     .06       0
Bank Sta=454.68,485.5
XS Rating Curve= 0 ,0
Exp/Cntr=0.3,0.1

Type RM Length L Ch R = 1 ,15239.5 ,640.6,665.6,690
XS GIS Cut Line= 4
     2047258.682      191527.308     2047482.641      191602.829
     2048052.953      191201.788     2048279.516      191279.913
#Sta/Elev= 30
       0 1609.94   298.5 1598.18   370.6 1590.93   396.7 1587.33   416.4  1587.7
  443.381582.582   458.3 1582.08   468.8 1582.04   488.4 1582.21  494.741582.239
   501.5 1582.46   511.3 1585.48   530.9 1586.63     675  1587.3   717.5 1589.44
   792.8 1590.98  928.081599.715     953 1602.12  960.071605.072   965.9  1607.9
   988.6  1608.7   995.1 1611.96 1002.221616.932  1063.1    1646  1072.8 1649.48
  1082.5 1651.61  1098.7 1658.48  1153.8 1670.41 1172.821673.018  1173.2 1673.05
#Mann= 9 ,-1 , 0
       0     .06       0  443.38     .08       0   458.3    .045       0
   488.4     .08       0  494.74     .06       0  928.08     .08       0
  960.07    .016       0 1002.22     .12       0 1172.82     .06       0
Bank Sta=458.3,488.4
XS Rating Curve= 0 ,0
Exp/Cntr=0.3,0.1

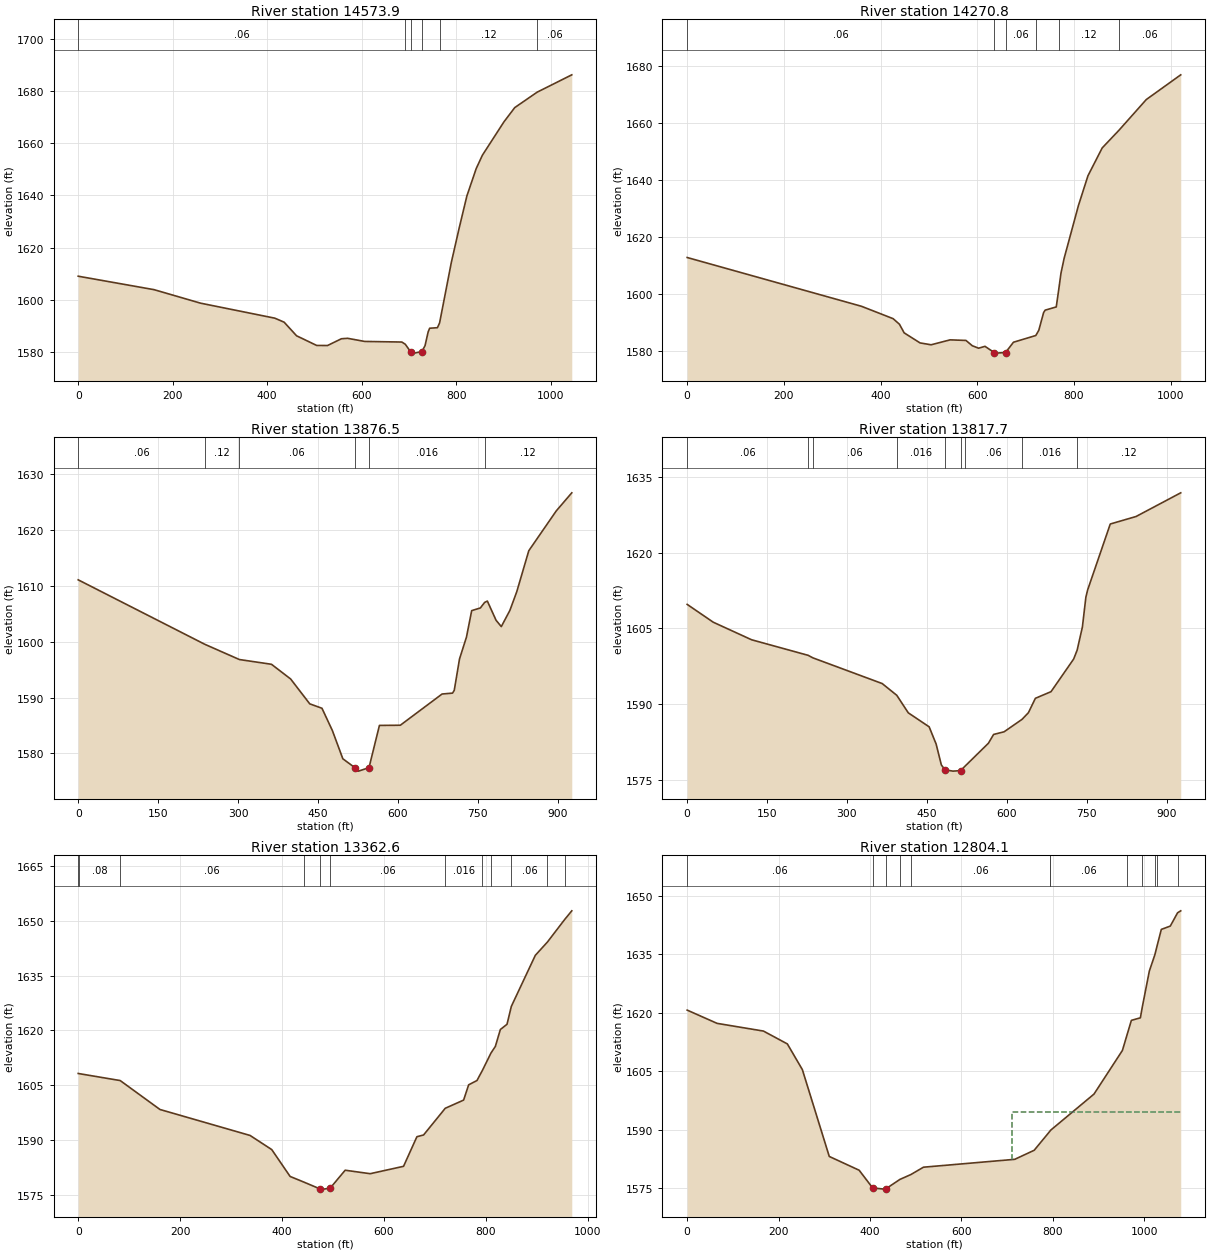
Type RM Length L Ch R = 1 ,14573.9 ,303.8,303.1,301
XS GIS Cut Line= 3
     2047257.923      191585.758     2048015.735      192010.237
     2048073.027      192176.903
#Sta/Elev= 30
       0    1609   160.6 1603.83   258.9 1598.65   416.3 1592.88   435.9 1591.34
   462.2 1586.12   504.8 1582.41   527.7 1582.38   557.2 1584.98   570.3 1585.15
   606.4 1583.95     685 1583.72  692.32 1582.87   704.7 1579.72   711.3 1579.46
   727.5 1580.07   734.2 1582.34   740.8 1587.64     744 1589.02   760.4 1589.23
     7651591.059   789.9 1614.35   806.3 1627.39   822.7 1639.79   842.4 1650.29
   855.5 1655.44   901.2 1668.28   924.1 1673.76  971.631679.694  1044.8 1686.34
#Mann= 6 ,-1 , 0
       0     .06       0  692.32     .12       0   704.7    .045       0
   727.5    .016       0     765     .12       0  971.63     .06       0
Bank Sta=704.7,727.5
XS Rating Curve= 0 ,0
Exp/Cntr=0.3,0.1

Type RM Length L Ch R = 1 ,14270.8 ,394.9,394.3,394.9
XS GIS Cut Line= 3
     2047106.881       191812.32     2047895.944      192273.258
     2048002.714      192273.258
#Sta/Elev= 30
       0 1612.89   360.3 1595.76   425.8 1591.41   438.9 1589.46   448.7 1586.42
   481.5 1582.89   504.4 1582.23   543.7 1583.96   576.5 1583.76   589.6 1581.89
   602.7 1581.03   615.8 1581.69   635.4 1579.45   638.7  1579.3   658.4 1579.52
   674.7 1583.13  720.891585.487   727.1 1587.32     737 1593.51   740.2 1594.39
   763.2 1595.53  768.341601.655     773 1607.42   779.5 1612.61     809 1631.11
   828.7 1641.58   858.2 1651.38   892.9 1657.59   949.4 1668.38  1020.6 1677.06
#Mann= 6 ,-1 , 0
       0     .06       0   635.4    .045       0   658.4     .06       0
  720.89    .016       0  768.34     .12       0   892.9     .06       0
Bank Sta=635.4,658.4
XS Rating Curve= 0 ,0
Exp/Cntr=0.3,0.1

Type RM Length L Ch R = 1 ,13876.5 ,58.4,58.8,57.4
XS GIS Cut Line= 3
     2046932.402       192187.32     2047643.339      192541.487
     2047773.548      192518.049
#Sta/Elev= 30
       0 1611.07  237.511599.543  302.591596.808   362.8 1595.96   398.8 1593.33
   434.7 1588.88   457.6 1588.09   477.2 1584.09   496.8 1579.05   519.7 1577.44
   526.2 1576.84   545.9 1577.46   565.5 1585.02   604.7 1585.05   683.1 1590.64
   702.8  1590.8     706 1591.31   715.8  1596.9   728.9 1600.83   738.7 1605.56
     755 1606.04  762.931607.021   768.1 1607.27   784.5 1603.83   794.3  1602.7
   810.4  1605.6   823.3 1608.94   845.9 1616.28   897.5 1623.41   926.6 1626.64
#Mann= 6 ,-1 , 0
       0     .06       0  237.51     .12       0  302.59     .06       0
   519.7    .045       0   545.9    .016       0  762.93     .12       0
Bank Sta=519.7,545.9
XS Rating Curve= 0 ,0
Exp/Cntr=0.3,0.1

Type RM Length L Ch R = 1 ,13817.7 ,454.2,455.1,456.5
XS GIS Cut Line= 3
     2046924.589      192242.008     2047635.527      192596.174
     2047765.735      192572.737
#Sta/Elev= 30
       0 1609.78      49 1606.24   120.9 1602.76  227.171599.669  235.981599.171
   366.1 1594.07  393.551591.735   415.1 1588.26   454.3 1585.48   467.4 1582.06
   477.2 1577.92     484 1576.95     499 1576.69   513.2 1576.79  522.381577.749
   565.5 1582.22   575.3 1583.97   594.9 1584.49  628.541586.952   640.6 1588.28
   653.7 1591.14   683.1 1592.46   725.6 1598.94  732.171600.711     742 1605.31
   748.5  1611.2   751.8 1612.64   794.3 1625.73   842.7 1627.22   926.6 1631.92
#Mann= 9 ,-1 , 0
       0     .06       0  227.17     .12       0  235.98     .06       0
  393.55    .016       0     484    .045       0   513.2     .08       0
  522.38     .06       0  628.54    .016       0  732.17     .12       0
Bank Sta=484,513.2
XS Rating Curve= 0 ,0
Exp/Cntr=0.3,0.1

Type RM Length L Ch R = 1 ,13362.6 ,557.6,558.5,558.5
XS GIS Cut Line= 3
     2046705.839      192614.403     2047466.256      193025.862
     2047570.423      193028.466
#Sta/Elev= 30
       0 1608.21    1.291608.175   82.381606.272   160.5 1598.36   337.3 1591.26
   379.9 1587.39   415.9 1580.05  443.37 1578.48   474.6 1576.64   481.4 1576.58
   494.5 1576.84     524 1581.75   573.1  1580.8   638.6 1582.82   664.8 1590.91
   677.9 1591.39  720.451598.691   756.5 1600.93   766.4 1605.11   782.7 1606.28
  793.451609.072  810.061613.765   818.8 1615.61   828.6 1620.23   841.7 1621.67
  850.131626.547   897.2 1640.51  920.921644.142  954.651650.279   968.8 1652.69
#Mann= 12 ,-1 , 0
       0     .06       0    1.29     .08       0   82.38     .06       0
  443.37     .08       0   474.6    .045       0   494.5     .06       0
  720.45    .016       0  793.45     .06       0  810.06    .016       0
  850.13     .06       0  920.92    .016       0  954.65     .06       0
Bank Sta=474.6,494.5
XS Rating Curve= 0 ,0
Exp/Cntr=0.3,0.1

Type RM Length L Ch R = 1 ,12804.1 ,373.5,375.9,376.4
XS GIS Cut Line= 2
     2046376.738      193031.649     2047324.654       193549.01
#Sta/Elev= 30
       0 1620.66    65.4 1617.26   166.9 1615.28   219.2 1611.98     252 1605.39
   310.9 1583.09   376.3 1579.55   405.8 1575.01   431.5  1574.7   435.2 1574.81
   465.4 1577.19  489.461578.445     517 1580.33   716.7 1582.35   759.2 1584.67
  794.381589.669  794.821589.782   890.1  1599.1   952.3 1610.31  962.161614.202
   971.9 1618.03   991.6 1618.68  995.811621.463  1011.2 1630.68 1023.33 1634.89
 1028.381637.244  1037.4 1641.38    1057 1642.23 1072.991645.642  1079.9 1646.15
#Mann= 12 ,-1 , 0
       0     .06       0   405.8    .045       0   435.2     .06       0
   465.4     .12       0  489.46     .06       0  794.38     .12       0
  794.82     .06       0  962.16    .016       0  995.81     .12       0
 1023.33     .06       0 1028.38    .016       0 1072.99     .06       0
#XS Ineff= 2 , 0
                          710.23         1594.57
Permanent Ineff=
       F       F
Bank Sta=405.8,435.2
XS Rating Curve= 0 ,0
Exp/Cntr=0.3,0.1

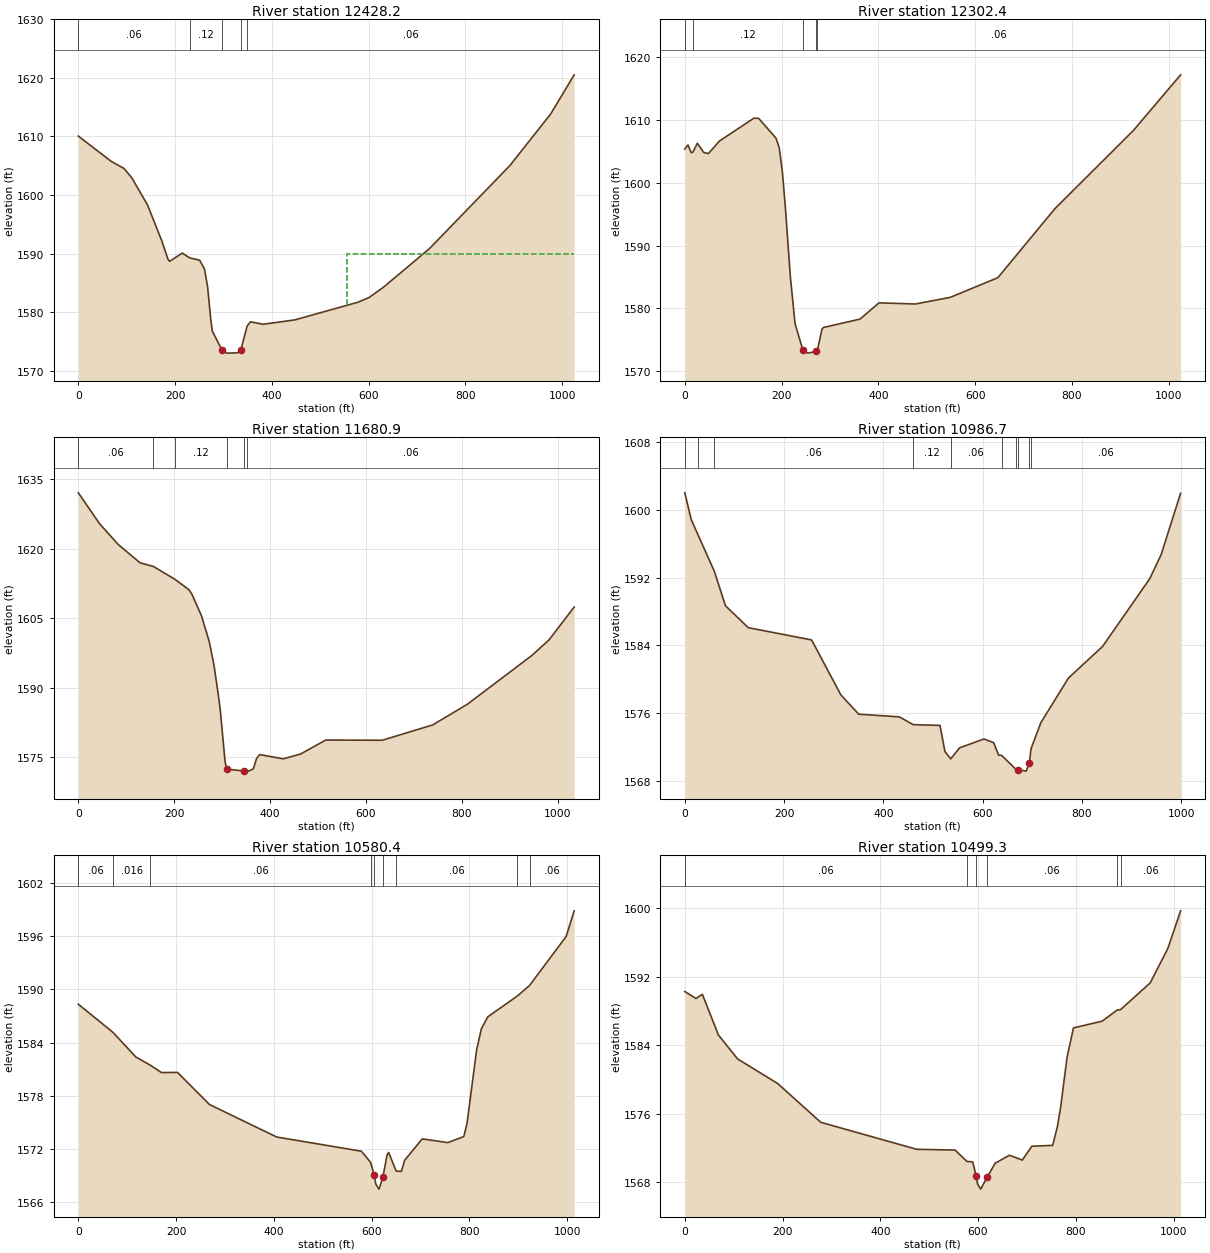
Type RM Length L Ch R = 1 ,12428.2 ,125.8,125.8,125.8
XS GIS Cut Line= 4
     2046276.043       193330.26     2046404.516      193444.843
     2046883.682      193746.927     2047164.932       193799.01
#Sta/Elev= 30
       0 1610.07    68.2 1605.74    94.2 1604.55   110.4 1602.96   142.9 1598.33
   172.2 1592.24   185.2 1589.05   188.5 1588.68   214.7 1590.09  230.351589.261
   250.7 1588.88   260.6  1587.4   267.1 1584.37   273.6  1578.8   276.9 1576.75
   296.6 1573.58   306.4 1573.01   329.3 1573.06   335.9 1573.55  348.731577.612
   355.5 1578.36   381.7 1577.94   447.2 1578.68   578.2 1581.71   601.1 1582.52
   630.5 1584.26   725.5 1590.85   891.4    1605   975.9 1613.82  1024.6 1620.53
#Mann= 5 ,-1 , 0
       0     .06       0  230.35     .12       0   296.6    .045       0
   335.9     .12       0  348.73     .06       0
#XS Ineff= 2 , 0
                          555.57            1590
Permanent Ineff=
       F       F
Bank Sta=296.6,335.9
XS Rating Curve= 0 ,0
Exp/Cntr=0.3,0.1

Type RM Length L Ch R = 1 ,12302.4 ,636.7,621.5,605.9
XS GIS Cut Line= 4
     2046237.849      193451.788     2046366.321      193566.371
     2046845.488      193868.454     2047126.738      193920.538
#Sta/Elev= 30
       0 1605.38     6.5 1606.04      13 1604.84   16.521604.873      26 1606.31
      39 1604.86    48.7 1604.66    71.5 1606.66   142.9 1610.32   152.7 1610.28
   188.5 1607.12   195.1 1605.61   201.6 1601.82   208.2 1595.71     218 1585.17
   227.8 1577.58   244.2 1573.29     254 1572.87   271.4 1573.13  273.931573.287
   283.5 1576.69   286.7 1576.96     362 1578.29   401.3 1580.88   476.6  1580.7
   548.7 1581.76   646.9 1584.89   764.6 1595.87   927.1 1608.36  1024.6 1617.22
#Mann= 5 ,-1 , 0
       0     .04       0   16.52     .12       0   244.2    .045       0
   271.4     .12       0  273.93     .06       0
Bank Sta=244.2,271.4
XS Rating Curve= 0 ,0
Exp/Cntr=0.3,0.1

Type RM Length L Ch R = 1 ,11680.9 ,694.8,694.2,695.6
XS GIS Cut Line= 3
     2046026.043      194201.788     2046119.793      194222.621
     2047050.349      194104.565
#Sta/Elev= 30
       0 1632.06    44.8 1625.33    83.2 1620.92   128.8 1616.96  156.731616.175
  201.951613.372   230.5 1611.18   237.1 1610.15   256.8 1605.56   273.1 1599.95
     283 1594.84   292.8 1587.83   296.1 1585.12   305.9 1574.21   309.2 1572.48
   345.3 1572.06  350.82 1572.05   355.1 1572.04     365 1572.53   371.5 1574.71
   378.1 1575.61   427.3 1574.69   463.4 1575.72   515.8 1578.74   633.9  1578.7
   738.9    1582     811 1586.44   945.5 1596.96   981.6 1600.34    1034 1607.43
#Mann= 6 ,-1 , 0
       0     .06       0  156.73    .016       0  201.95     .12       0
   309.2    .045       0   345.3     .12       0  350.82     .06       0
Bank Sta=309.2,345.3
XS Rating Curve= 0 ,0
Exp/Cntr=0.3,0.1

Type RM Length L Ch R = 1 ,10986.7 ,400.3,406.3,408.3
XS GIS Cut Line= 2
     2045963.652      194801.903     2046961.048      194755.028
#Sta/Elev= 30
       0    1602    13.1 1598.83   26.431597.071   59.441592.751    81.8 1588.69
   127.7  1586.1   255.4 1584.65   314.3 1578.17   350.3 1575.89   432.1 1575.58
  459.911574.661     514 1574.57   523.8 1571.49  535.591570.629   553.3 1571.92
   602.4 1572.97     622 1572.54   631.8 1571.07  637.981571.036  667.551569.354
   670.2 1569.34   687.5 1569.18     694 1570.15  697.121571.795     717 1574.89
   772.6 1580.16   841.4 1583.89   936.3 1591.87   959.2  1594.7   998.5 1601.95
#Mann= 10 ,-1 , 0
       0     .06       0   26.43    .016       0   59.44     .06       0
  459.91     .12       0  535.59     .06       0  637.98     .12       0
  667.55     .08       0   670.2    .045       0     694     .08       0
  697.12     .06       0
Bank Sta=670.2,694
XS Rating Curve= 0 ,0
Exp/Cntr=0.3,0.1

Type RM Length L Ch R = 1 ,10580.4 ,81.1,81.1,80.9
XS GIS Cut Line= 2
     2045974.069      195114.403     2046987.089      195169.091
#Sta/Elev= 30
       0 1588.32   70.641585.161   117.8 1582.37  146.961581.463   170.2 1580.62
   202.9 1580.64   268.4 1577.02   405.8 1573.36   579.2 1571.76  598.061570.496
   605.4 1569.08   608.7 1568.05   615.2 1567.49   623.1 1568.82   631.6 1571.33
   634.9 1571.62  650.391569.512   661.1 1569.49   667.6 1570.73   703.6 1573.15
     756 1572.73   788.7 1573.41   795.2 1574.85   814.9 1583.16   824.7 1585.56
   837.8  1586.9  898.17 1589.24  923.181590.427   998.1 1595.95  1014.5 1598.84
#Mann= 9 ,-1 , 0
       0     .06       0   70.64    .016       0  146.96     .06       0
  598.06    .016       0   605.4    .045       0   623.1    .016       0
  650.39     .06       0  898.17    .016       0  923.18     .06       0
Bank Sta=605.4,623.1
XS Rating Curve= 0 ,0
Exp/Cntr=0.3,0.1

Type RM Length L Ch R = 1 ,10499.3 ,331.4,325.2,316.5
XS GIS Cut Line= 2
     2045994.902      195195.133     2047007.923       195249.82
#Sta/Elev= 30
       0 1590.27    22.9 1589.46      36 1589.94    68.7  1585.2     108  1582.4
   189.8 1579.54   278.2    1575   474.5 1571.85   553.1 1571.76   577.31570.433
   589.1 1570.38   596.1 1568.75   598.9 1567.81   605.4  1567.2   618.5 1568.56
   634.9 1570.22   664.3 1571.16   690.5 1570.59   710.2 1572.21   752.7 1572.31
   762.5 1574.53     769 1576.75   782.1 1582.58   795.2 1586.02   854.1 1586.81
   884.6 1588.11  891.591588.155   952.3 1591.28   988.3 1595.29  1014.5 1599.69
#Mann= 6 ,-1 , 0
       0     .06       0   577.3     .08       0   596.1    .045       0
   618.5     .06       0   884.6    .016       0  891.59     .06       0
Bank Sta=596.1,618.5
XS Rating Curve= 0 ,0
Exp/Cntr=0.3,0.1

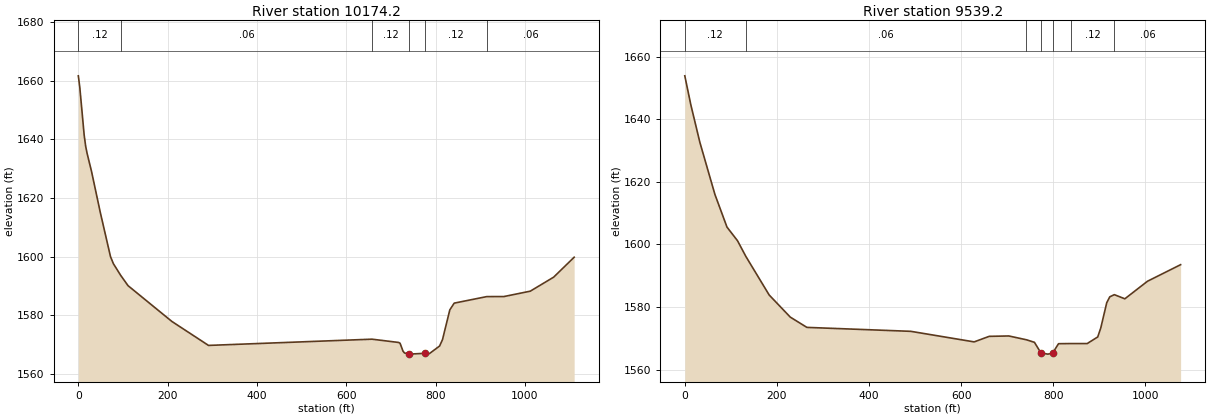
Type RM Length L Ch R = 1 ,10174.2 ,640.4,635,629.3
XS GIS Cut Line= 2
      2046000.11      195744.612     2047049.589      195382.633
#Sta/Elev= 30
       0 1661.71     3.3 1657.75    13.1 1641.47    16.4 1637.74    19.6 1635.28
    29.5 1629.14    49.1 1615.18      72 1600.06    78.6 1597.61   94.88 1593.65
   111.3 1590.14   209.6 1577.92   291.5 1569.76  657.491571.886   717.2 1570.77
   720.4  1570.5     727  1567.8   730.3 1567.19   740.1 1566.79   776.1 1567.07
     786 1566.95   808.9 1569.56   815.4 1571.73   831.8 1581.89   841.6 1584.18
  914.411586.408     953 1586.43  1011.9 1588.26  1064.3 1593.04  1110.2 1599.84
#Mann= 6 ,-1 , 0
       0     .12       0   94.88     .06       0  657.49     .12       0
   740.1    .045       0   776.1     .12       0  914.41     .06       0
Bank Sta=740.1,776.1
XS Rating Curve= 0 ,0
Exp/Cntr=0.3,0.1

Type RM Length L Ch R = 1 ,9539.2  ,1059,1058.7,1057.1
XS GIS Cut Line= 2
      2046312.61      196372.216     2047247.506      195838.362
#Sta/Elev= 30
       0 1653.85    13.1  1644.6    32.7 1632.62    65.4 1615.97    91.6 1605.54
   114.5 1601.18  132.471596.203   183.2 1583.86   229.1 1576.78   265.1 1573.51
   490.8 1572.25   628.3 1568.88     661 1570.65   703.5 1570.77  741.821569.551
   759.2 1568.74   773.3 1565.34   788.3 1564.97   798.4 1565.24   811.5  1568.3
   837.61568.344   873.7 1568.34   896.6 1570.45   903.2 1573.32   916.2  1581.4
   922.8 1583.27  932.63 1583.96   955.5 1582.64  1004.6 1588.24  1076.6 1593.54
#Mann= 7 ,-1 , 0
       0     .12       0  132.47     .06       0  741.82     .12       0
   773.3    .045       0   798.4     .06       0   837.6     .12       0
  932.63     .06       0
Bank Sta=773.3,798.4
XS Rating Curve= 0 ,0
Exp/Cntr=0.3,0.1