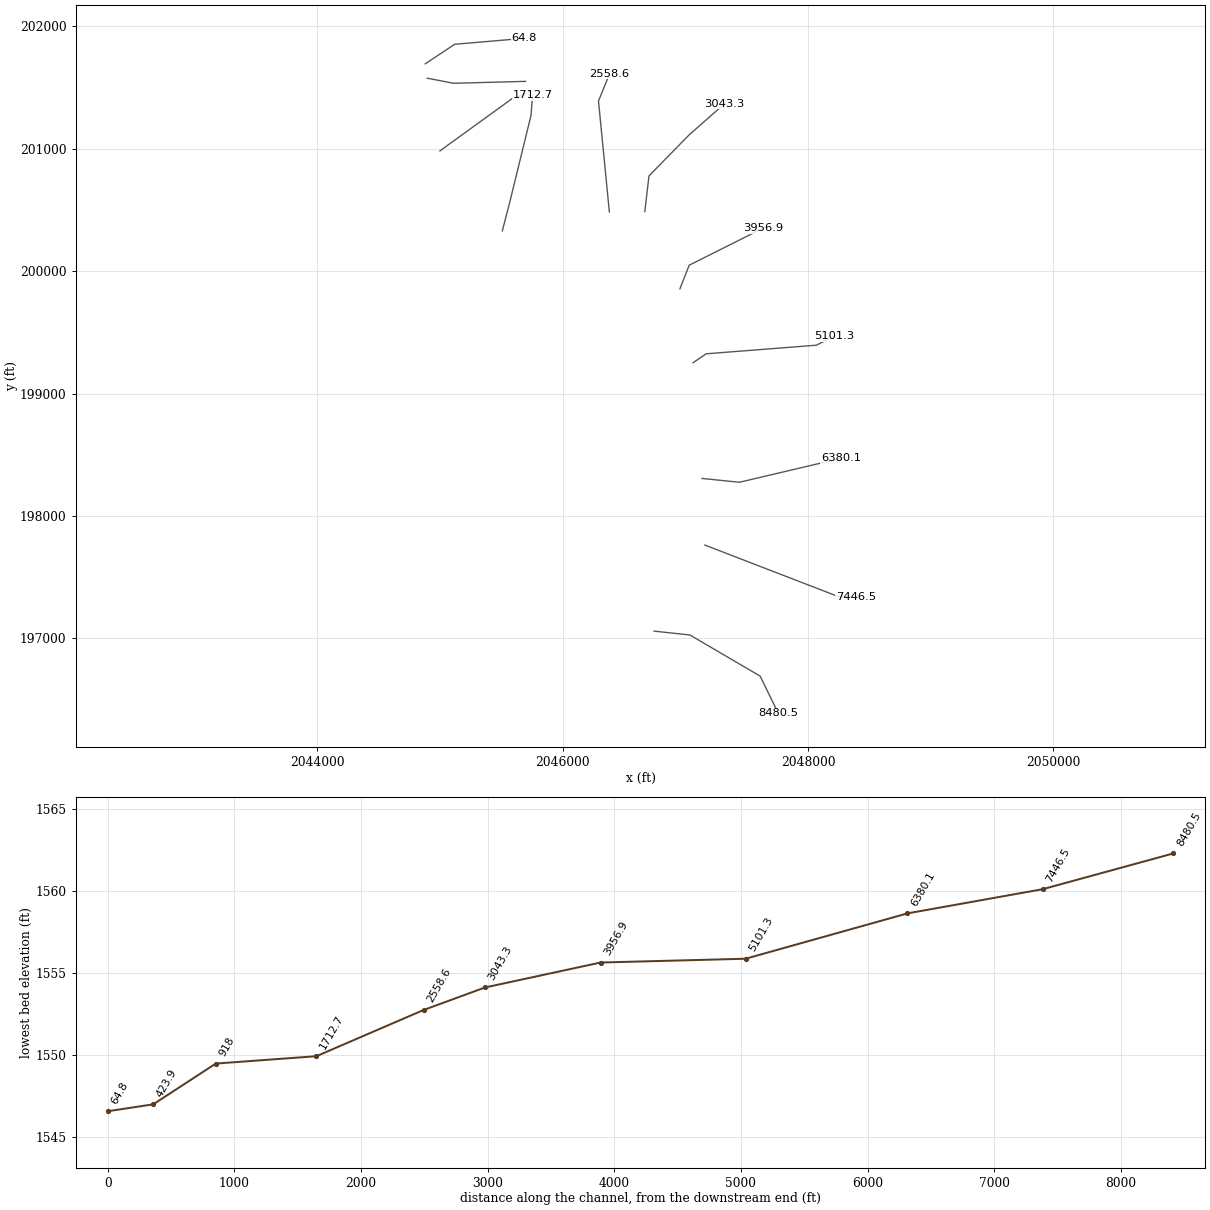
HEC-RAS study HNSCK.prj: HNSCK

--- HNSCK.g01 (geometry) --- (continued)

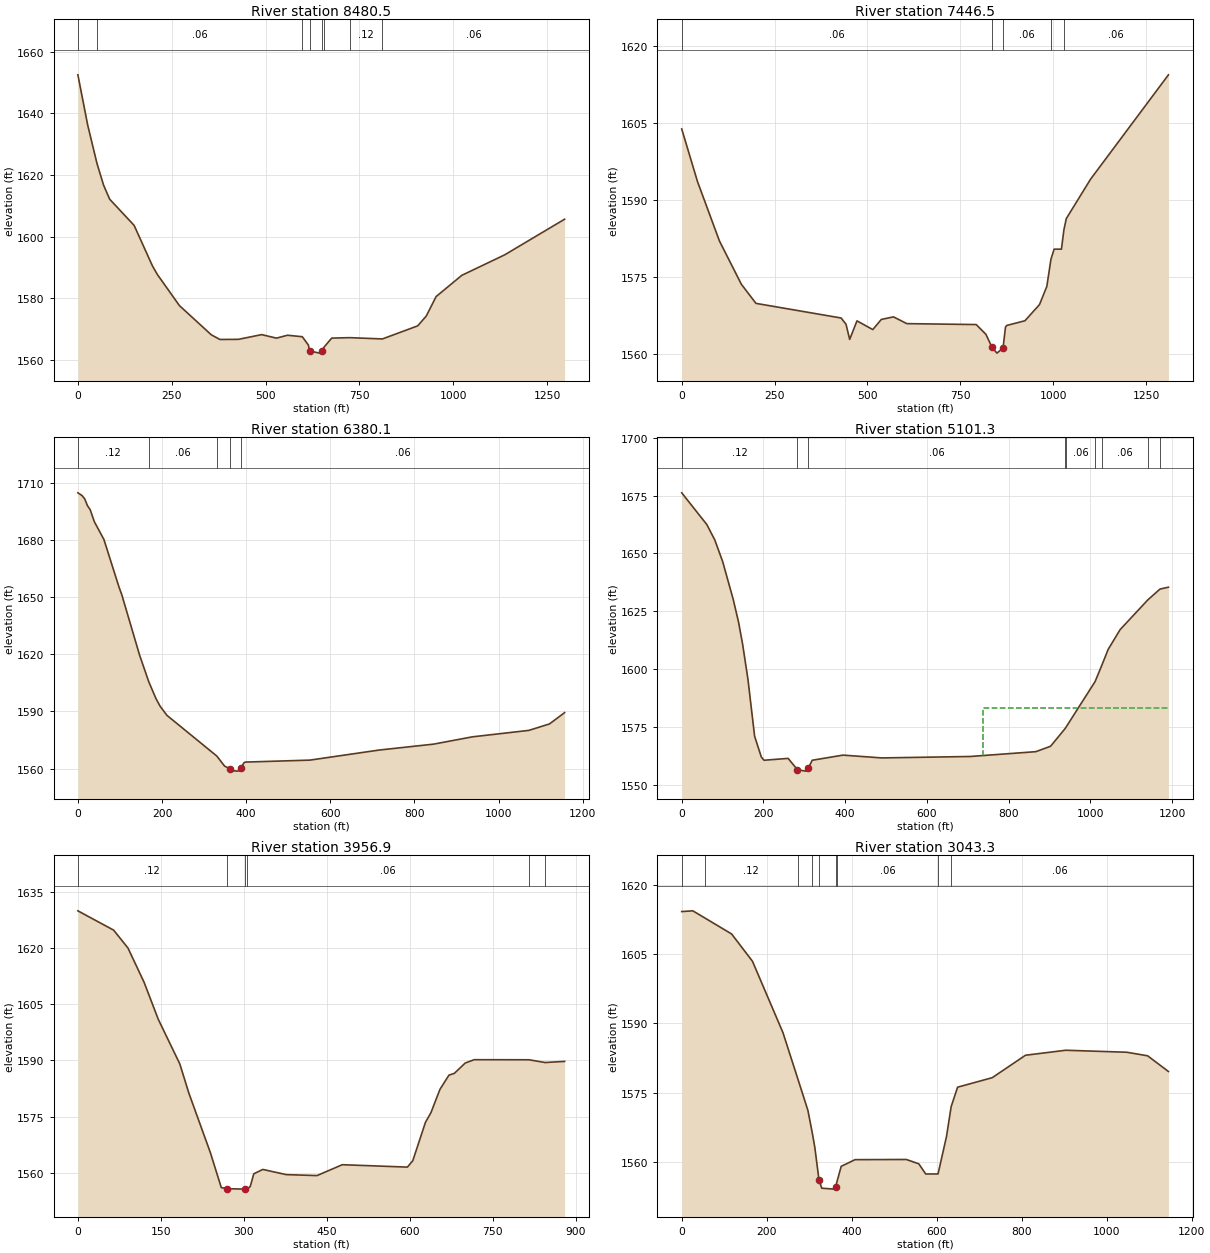
Type RM Length L Ch R = 1 ,8480.5  ,1029.9,1034,1036.9
XS GIS Cut Line= 4
     2046744.902      197059.716     2047036.569      197028.466
     2047609.485      196692.528     2047757.923      196387.841
#Sta/Elev= 30
       0 1652.52    26.1 1636.27   51.011623.728    68.4 1616.78    84.7 1612.19
   149.9 1603.69   198.8 1590.52   211.8 1587.77   270.5 1577.69   355.5 1568.21
   378.4 1566.71   427.5 1566.75   489.6 1568.28   528.9 1567.14   558.3 1568.08
  597.741567.603     614 1564.89   617.2 1563.02   643.4 1562.28     650 1563.08
  654.321564.019   676.1 1567.15  724.311567.298  811.22 1566.88   905.1 1571.12
     928 1574.31   954.2 1580.62  1022.7 1587.51  1136.7 1594.14  1296.4  1605.7
#Mann= 8 ,-1 , 0
       0     .12       0   51.01     .06       0  597.74     .12       0
   617.2    .045       0     650     .12       0  654.32     .06       0
  724.31     .12       0  811.22     .06       0
Bank Sta=617.2,650
XS Rating Curve= 0 ,0
Exp/Cntr=0.3,0.1

Type RM Length L Ch R = 1 ,7446.5  ,1051.5,1066.3,1078.5
XS GIS Cut Line= 3
     2047158.964      197762.841      2048250.11      197340.966
     2048390.735      197340.966
#Sta/Elev= 30
       0 1603.89    42.6 1593.58   101.6    1582   160.6 1573.55   199.9 1569.82
   429.3 1566.96   442.4 1565.74   452.2 1562.78   471.9  1566.4   514.5  1564.7
   537.4 1566.68   570.2 1567.18   606.2 1565.86     793 1565.68   819.2 1563.76
   835.6 1561.21   848.7  1560.1   865.1 1561.07   871.7 1565.15   874.9  1565.5
   924.1 1566.42   963.4 1569.59   983.1 1573.14  994.151578.433  1002.7 1580.41
  1022.4 1580.41 1029.06 1584.19  1035.5 1586.38    1101 1594.09  1310.5 1614.46
#Mann= 5 ,-1 , 0
       0     .06       0   835.6    .045       0   865.1     .06       0
  994.15    .016       0 1029.06     .06       0
Bank Sta=835.6,865.1
XS Rating Curve= 0 ,0
Exp/Cntr=0.3,0.1

Type RM Length L Ch R = 1 ,6380.1  ,1288.3,1278.9,1273.9
XS GIS Cut Line= 3
     2047135.527      198307.112     2047440.214      198275.862
     2048268.339      198471.174
#Sta/Elev= 30
       0 1704.98     9.8 1703.57    16.3 1701.79    22.8 1698.22    29.3 1696.12
    39.1 1689.81    61.9 1680.45    97.8 1655.41   104.3 1651.49   146.6 1619.71
  168.431605.697   185.7 1596.76   195.5 1592.78   211.8 1587.95  330.281566.568
   348.8 1561.27   361.9 1559.82   365.2 1558.95   378.3 1558.63   384.8 1558.92
   388.1 1560.27   394.6 1562.97   397.9 1563.38   551.7 1564.42   715.4 1569.69
   846.2 1572.84   937.9 1576.66    1072 1580.05  1121.1 1583.44  1157.1 1589.38
#Mann= 5 ,-1 , 0
       0     .12       0  168.43     .06       0  330.28     .12       0
   361.9    .045       0   388.1     .06       0
Bank Sta=361.9,388.1
XS Rating Curve= 0 ,0
Exp/Cntr=0.3,0.1

Type RM Length L Ch R = 1 ,5101.3  ,1127.8,1144.4,1150.9
XS GIS Cut Line= 4
      2047062.61      199252.424     2047169.381      199325.341
     2048067.819      199395.653     2048211.048       199468.57
#Sta/Elev= 30
       0  1676.2    61.4  1662.5    80.8 1655.89   100.2 1646.49   126.1 1630.09
   139.1 1620.28     149 1610.78   162.1 1595.58   178.4 1570.97   194.8 1561.98
   201.4 1560.57   260.4 1561.38   283.3 1556.49     303 1555.87   309.5 1557.04
   319.4 1560.57   394.7 1562.79   489.8 1561.58     706  1562.2   866.6 1564.28
   902.7 1566.62  937.711574.137  939.961574.713 1011.771594.609 1028.671601.851
  1043.6 1608.46  1073.1 1617.09 1140.97 1629.95 1170.621634.592  1191.2  1635.4
#Mann= 9 ,-1 , 0
       0     .12       0   283.3    .045       0   309.5     .06       0
  937.71     .12       0  939.96     .06       0 1011.77     .12       0
 1028.67     .06       0 1140.97     .12       0 1170.62    .016       0
#XS Ineff= 2 , 0
                          738.04         1583.17
Permanent Ineff=
       F       F
Bank Sta=283.3,309.5
XS Rating Curve= 0 ,0
Exp/Cntr=0.3,0.1

Type RM Length L Ch R = 1 ,3956.9  ,906,913.6,920.2
XS GIS Cut Line= 3
     2046955.839      199856.591      2047031.36      200049.299
     2047632.923      200351.383
#Sta/Elev= 30
       0 1629.95    64.7 1624.79    90.6 1620.02   119.7 1610.88   145.5 1600.95
   184.3 1589.09   200.5 1581.36   239.7 1565.34   259.3 1556.06   269.1 1555.76
   301.7 1555.64  305.671555.646   311.6  1556.3   318.1 1559.73   334.4  1560.9
   376.9 1559.51   432.4 1559.26   478.2 1562.16   595.8 1561.52   605.6 1563.22
   628.5 1573.48   638.3 1576.01   654.7 1582.27     671 1586.07   680.8 1586.56
   700.4 1589.31   716.7  1590.2  815.841590.178  844.871589.445   880.1 1589.75
#Mann= 6 ,-1 , 0
       0     .12       0   269.1    .045       0   301.7     .08       0
  305.67     .06       0  815.84    .016       0  844.87     .06       0
Bank Sta=269.1,301.7
XS Rating Curve= 0 ,0
Exp/Cntr=0.3,0.1

Type RM Length L Ch R = 1 ,3043.3  ,464,484.7,503.6
XS GIS Cut Line= 4
     2046669.381      200486.799     2046703.235      200778.466
      2047031.36      201114.403     2047317.819      201367.008
#Sta/Elev= 30
       0 1614.22    26.1 1614.38    54.61612.822   117.4 1609.37   166.4 1603.47
   238.2 1588.01  272.461578.203   296.9 1571.17  307.531566.137   313.2 1563.13
     323 1556.12   329.5 1554.32   358.8 1554.12   362.1 1554.57  364.891555.576
   375.2 1559.05   407.8  1560.5   528.4 1560.54   557.8  1559.6   574.1  1557.4
  603.061557.406     623 1565.51  633.971571.984   649.1 1576.19   730.6 1578.25
   808.9 1583.11   903.6 1584.19  1047.2 1583.76  1096.2 1582.99  1145.2 1579.59
#Mann= 9 ,-1 , 0
       0     .06       0    54.6     .12       0  272.46     .06       0
  307.53     .08       0     323    .045       0   362.1     .08       0
  364.89     .06       0  603.06     .04       0  633.97     .06       0
Bank Sta=323,362.1
XS Rating Curve= 0 ,0
Exp/Cntr=0.3,0.1

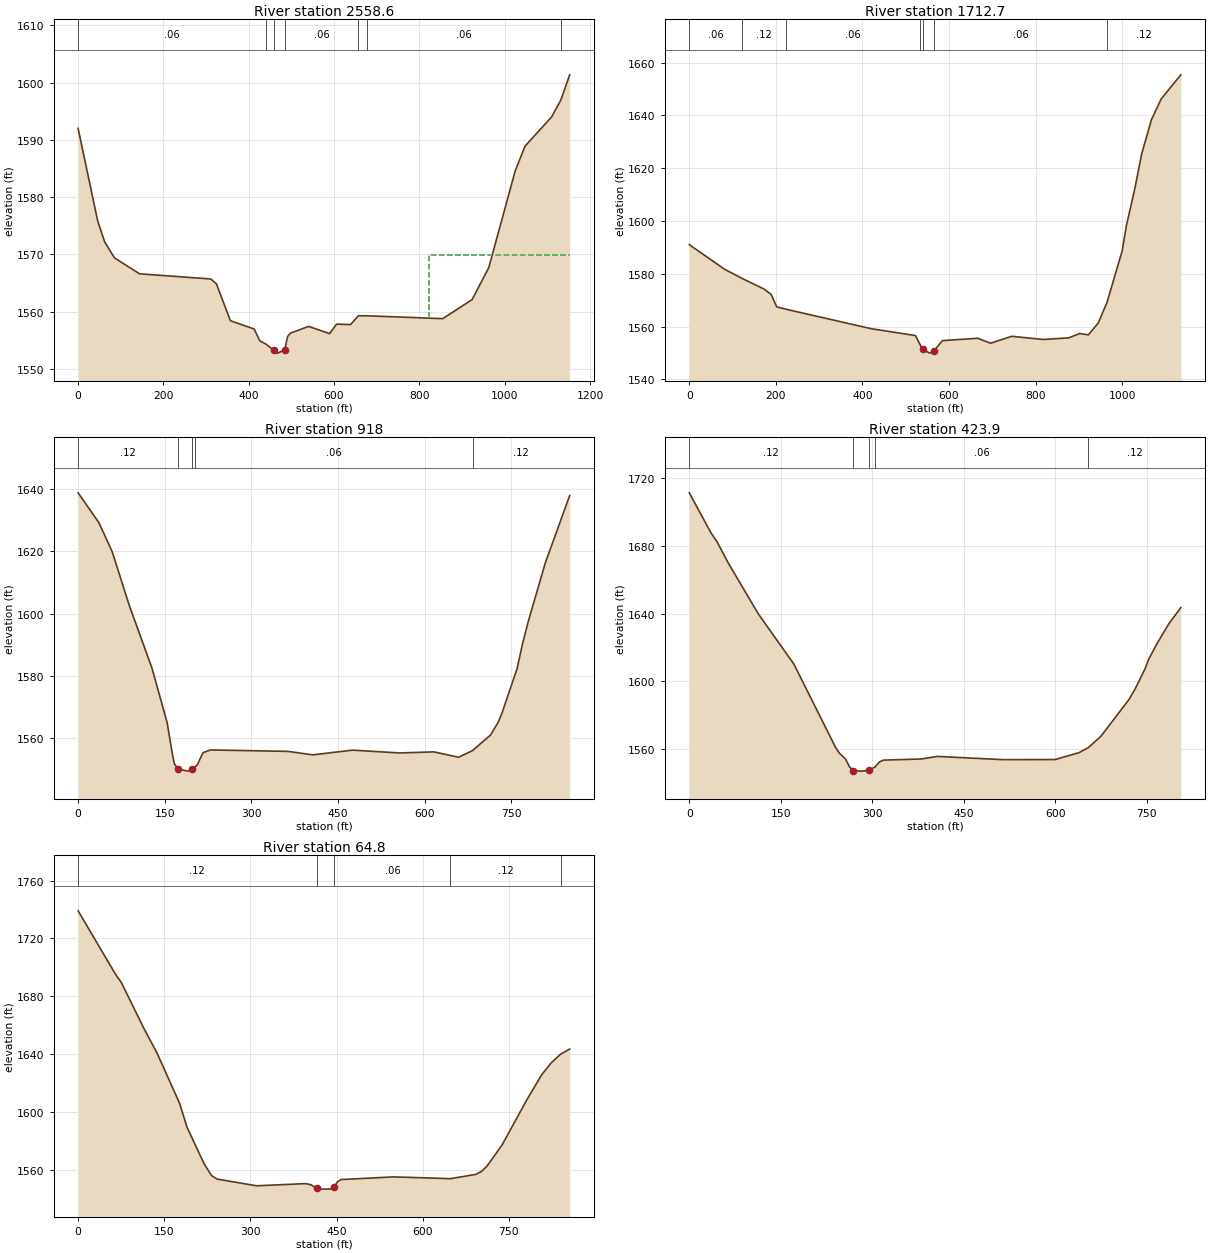
Type RM Length L Ch R = 1 ,2558.6  ,852.5,845.9,837
XS GIS Cut Line= 3
     2046380.319      200484.195     2046291.777      201390.445
     2046382.923      201614.403
#Sta/Elev= 30
       0    1592    45.9 1575.83    62.2 1572.19    85.2 1569.39   144.1  1566.6
   311.2  1565.7   324.3 1564.84     357 1558.41   412.7 1556.96   425.8 1554.91
  440.551554.315   458.6 1553.24   468.4 1552.75   484.3 1553.34   491.3 1555.68
   497.9 1556.24   540.4 1557.42   589.6 1556.16     606 1557.82   638.7 1557.73
  656.771559.267  676.861559.274   854.9 1558.77   923.6 1562.09   962.8 1567.69
  1024.9 1584.62  1047.8  1588.9  1109.9 1593.99 1131.591596.923  1152.4 1601.36
#Mann= 7 ,-1 , 0
       0     .06       0  440.55     .12       0   458.6    .045       0
   484.3     .06       0  656.77     .12       0  676.86     .06       0
 1131.59     .12       0
#XS Ineff= 2 , 0
                          822.16         1569.93
Permanent Ineff=
       F       F
Bank Sta=458.6,484.3
XS Rating Curve= 0 ,0
Exp/Cntr=0.3,0.1

Type RM Length L Ch R = 1 ,1712.7  ,810.5,794.7,778.3
XS GIS Cut Line= 4
     2045507.923      200329.681     2045570.423      200572.737
      2045741.43       201272.39      2045754.45      201436.452
#Sta/Elev= 30
       0 1591.04    81.5 1581.73  122.941578.178   172.7 1574.22     189 1572.21
   202.1 1567.48  224.031566.551   421.2 1559.17   522.7 1556.59  533.761553.022
   539.1 1551.38   555.4 1549.94   565.2 1550.78   584.9 1554.69   666.7 1555.56
   696.2  1553.7   745.3 1556.32   817.3 1555.11   876.3 1555.71   902.5 1557.38
   922.1 1556.86     945 1561.35  965.351569.223  1000.2 1588.65  1009.9 1598.19
  1029.3 1612.13  1045.4 1625.48    1068 1638.45  1090.6 1646.32  1135.8  1655.4
#Mann= 7 ,-1 , 0
       0     .06       0  122.94     .12       0  224.03     .06       0
  533.76     .08       0   539.1    .045       0   565.2     .06       0
  965.35     .12       0
Bank Sta=539.1,565.2
XS Rating Curve= 0 ,0
Exp/Cntr=0.3,0.1

Type RM Length L Ch R = 1 ,918     ,508,494.1,479.2
XS GIS Cut Line= 3
     2044999.242      200983.327     2045587.784       201410.41
     2045704.971      201449.473
#Sta/Elev= 30
       0 1638.78      36  1629.2      59 1619.89    88.4 1602.73   127.8 1582.55
     154  1565.1   163.8  1554.3     167 1551.68   173.6 1550.13     190 1549.49
   196.5 1550.02  202.111550.746   206.4 1551.57   216.2 1555.42   229.3 1556.29
   363.6 1555.82   406.2 1554.71     475 1556.22   556.8 1555.32   615.8 1555.67
   658.4 1553.94  682.741556.099   714.1 1561.14   727.2 1565.25   733.7  1568.2
   759.7 1582.38   769.4 1590.54   779.2  1597.6   808.4 1616.21   850.7 1637.89
#Mann= 5 ,-1 , 0
       0     .12       0   173.6    .045       0   196.5     .12       0
  202.11     .06       0  682.74     .12       0
Bank Sta=173.6,196.5
XS Rating Curve= 0 ,0
Exp/Cntr=0.3,0.1

Type RM Length L Ch R = 1 ,423.9   ,358,359.1,360.1
XS GIS Cut Line= 3
     2044895.075      201577.077     2045111.221       201535.41
     2045697.159      201551.035
#Sta/Elev= 30
       0 1711.22    35.6 1687.57    45.3 1682.49    64.7 1669.32   113.3 1639.76
   171.6 1610.15   239.8 1561.12   246.3 1557.57   256.2 1554.17   262.7 1549.64
   269.2 1547.21   282.3 1547.01   294.5 1547.42  304.891549.543   311.8 1552.38
   318.4 1553.51   380.6 1554.17   406.8 1555.69   514.8 1553.78     600 1553.84
   639.3 1557.92  654.451560.849   675.3 1567.61   721.1 1589.18     731 1595.27
   747.3 1607.16   753.9 1613.24     767 1622.12   786.6 1633.94   806.3 1643.51
#Mann= 5 ,-1 , 0
       0     .12       0   269.2    .045       0   294.5     .12       0
  304.89     .06       0  654.45     .12       0
Bank Sta=269.2,294.5
XS Rating Curve= 0 ,0
Exp/Cntr=0.3,0.1

Type RM Length L Ch R = 1 ,64.8    ,64.3,64.8,65.4
XS GIS Cut Line= 3
      2044879.45      201694.265     2045119.034      201853.987
     2045685.006      201902.598
#Sta/Elev= 30
       0 1739.11    65.4 1695.04    75.3 1689.49   114.5 1657.83   137.4 1640.74
   176.7 1605.98   189.8  1589.3   219.2  1564.3   232.3 1555.99   242.1 1553.52
   310.8  1548.9   395.7 1550.39   405.5 1549.64   415.3 1547.11   421.8 1546.59
   441.4 1546.66   446.4 1548.31   451.2 1551.48   457.7 1553.21   549.1 1555.06
  648.391553.834   692.8 1556.81   702.6 1558.85   712.4 1562.71   738.5 1577.24
   780.9 1608.02     807 1625.53   823.4 1633.76  840.311639.972     856  1643.5
#Mann= 5 ,-1 , 0
       0     .12       0   415.3    .045       0   446.4     .06       0
  648.39     .12       0  840.31     .06       0
Bank Sta=415.3,446.4
XS Rating Curve= 0 ,0
Exp/Cntr=0.3,0.1
Stream Node=HNSCK           ,Main            , 0 , 0 ,Upstream end
Stream Node=HNSCK           ,Main            , 0 , 1 ,Downstream end

Chan Stop Cuts=-1
Use User Specified Reach Order=0
Composite Channel Slope=5